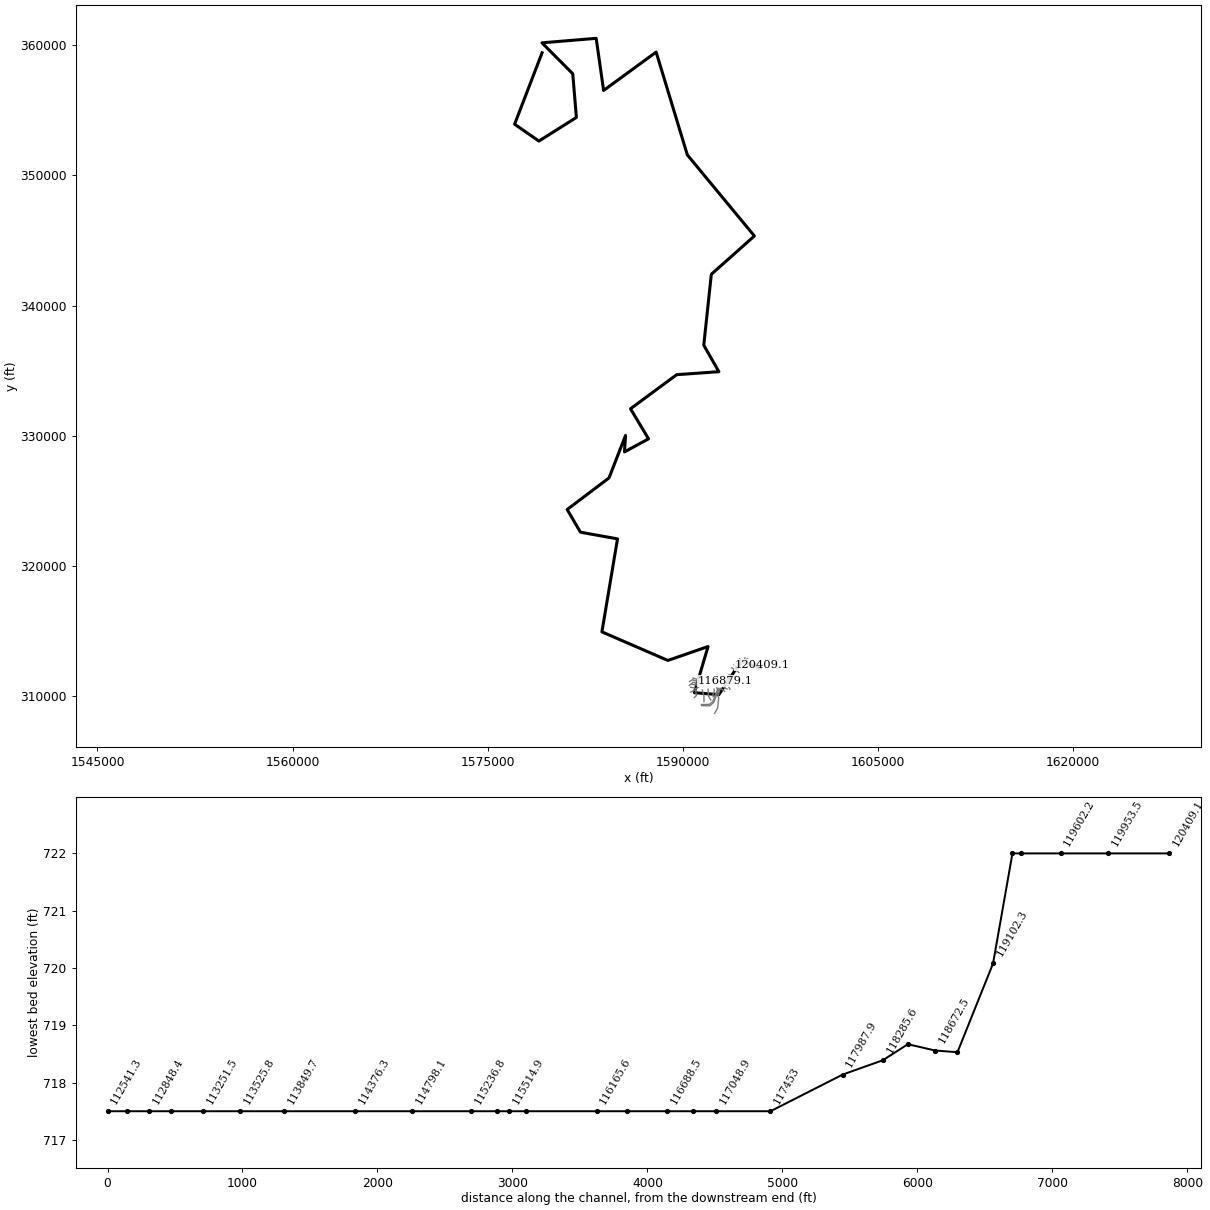
--- MDISLCRK_C.prj (project) ---

Proj Title=MDISLCRK_C
Current Plan=p01
Default Exp/Contr=0,0
English Units
Geom File=g01
Flow File=f01
Plan File=p01
BEGIN DESCRIPTION:
Main Reach was combined with the Jug Reach at River Station 19269.3 and the Weir across the main reach (just d/s of XS19269.3) was coded as Lateral Weir (18950) in order to correctly model the impact of the flow diversion thru the Jug Reach. Known WS bounday condition was used at downstream extents and the WSEL are obtained from the AE model Lettered cross section U.
END DESCRIPTION:
DSS Export Rating Curves= 0
DSS Export Rating Curve Sorted= 0
DSS Export Volume Flow Curves= 0
DXF OffsetX= 0
DXF OffsetY= 0
DXF ScaleX= 0
DXF ScaleY= 0

--- MDISLCRK_C.p01 (plan) ---

Plan Title=Floodplain
Program Version=4.10
Short Identifier=Floodplain
Geom File=g01
Flow File=f01
Subcritical Flow
K Sum by GR= 0
Std Step Tol= 0.01
Critical Tol= 0.01
Num of Std Step Trials= 20
Max Error Tol= 0.3
Flow Tol Ratio= 0.001
Split Flow NTrial= 30
Split Flow Tol= 0.02
Split Flow Ratio= 0.02
Log Output Level= 0
Friction Slope Method= 1
Unsteady Friction Slope Method= 2
Unsteady Bridges Friction Slope Method= 1
Parabolic Critical Depth
Global Vel Dist= 0 , 0 , 0
Global Log Level= 0
CheckData=True
Encroach Param=-1 ,0,0, 0
Optimized Weir=MDISLCRK_C      ,Main            ,18950
Run HTab= 0
Run UNet= 0
Run PostProcess= 0
Run WQNet= 0
UNET Theta= 0
UNET Theta Warmup= 0
UNET ZTol= 0
UNET ZSATol= 0
UNET MxIter= 0
UNET MaxInSteps= 0
UNET DtIC= 0
UNET DtMin= 0
UNET MaxCRTS= 0
UNET WFStab= 0
UNET SFStab= 0
UNET WFX= 1
UNET SFX= 1
UNET DSS MLevel= 1
UNET DZMax Abort= 0
UNET Convert EG Bridges= 0
UNET Use Existing IB Tables= 0
UNET Froude Reduction=False
UNET Froude Limit= 0
UNET Froude Power= 0
UNET Time Slicing=0,0, 5
UNET Junction Losses=0
Write IC File= 0
Write IC File at Sim End=0
Echo Input=False
Echo Parameters=False
Echo Output=False
Write Detailed= 0
WQ AD Non Conservative
WQ ULTIMATE=-1
WQ Max Comp Step=1HOUR
WQ Output Interval=15MIN
WQ Output Selected Increments= 0
WQ Output face flow=0
WQ Output face velocity=0
WQ Output face area=0
WQ Output face dispersion=0
WQ Output cell volume=0
WQ Output cell surface area=0
WQ Output cell continuity=0
WQ Output cumulative cell continuity=0
WQ Output face conc=0
WQ Output face dconc_dx=0
WQ Output face courant=0
WQ Output face peclet=0
WQ Output face adv mass=0
WQ Output face disp mass=0
WQ Output cell mass=0
WQ Output cell source sink temp=0
WQ Output cell source sink nsm=0
WQ Output MaxMinRange=-1
WQ Daily Max Min Mean=-1
WQ Daily Range=0
WQ Daily Time=0
WQ Create Restart=0
WQ Fixed Restart=0
WQ System Summary=0
WQ Use Fixed Temperature=0
Sorting and Armoring Iterations= 10
XS Update Threshold= 0.02
Hydraulics Update Threshold= 0.02
Energy Slope Method= 1
Volume Change Method= 0
XS Weighting Method= 0
Number of US Weighted Cross Sections= 1
Number of DS Weighted Cross Sections= 1
Upstream XS Weight=0.25
Main XS Weight=0.5
Downstream XS Weight=0.25
Number of DS XS's Weighted with US Boundary= 1
Upstream Boundary Weight= 1
Weight of XSs Associated with US Boundary= 0
Number of US XS's Weighted with DS Boundary= 1
Downstream Boundary Weight= 0.5
Weight of XSs Associated with DS Boundary= 0.5
Sediment Output Level= 4
Mass or Volume Output= 0
Output Increment Type= 1
Profile and TS Output Increment= 10
XS Output Flag= 0
XS Output Increment= 10
Disregard all LS=0
Disregard all Conn=0
Disregard all Breaches=0
Disregard all Pumps=0

--- MDISLCRK_C.f01 (steady flow) ---

Flow Title=NFF Regression Equation
Program Version=4.10
Number of Profiles= 1
Profile Names=P100yr
River Rch & RM=MDISLCRK_C,Main            ,120409.1
15167.28
River Rch & RM=MDISLCRK_C,Main            ,115236.8
17752.42
River Rch & RM=MDISLCRK_C,Main            ,105374.1
19574.98
River Rch & RM=MDISLCRK_C,Main            ,55119.5
26196.14
River Rch & RM=MDISLCRK_C,Main            ,48693.7
28804.23
Boundary for River Rch & Prof#=MDISLCRK_C,Main            , 1
Up Type= 0
Dn Type= 1
Dn Known WS=692.4
DSS Import GetInterval= 0
DSS Import GetPeak= 0
DSS Import FillOption= 0

--- MDISLCRK_C.g01 (geometry) ---

Geom Title=USGS 10m DEM
Program Version=4.10

River Reach=MDISLCRK_C      ,Main
Reach XY= 30
     1595971.132      312130.733     1594487.867      312663.171
      1592768.48      310089.796     1590888.264      310236.532
     1591941.355      313788.448     1588851.813      312718.268
     1583780.633      314914.449     1584980.215      322064.655
     1582130.957      322575.849     1581110.299      324320.531
     1584327.788      326749.446     1585597.473      330019.917
     1585515.007      328748.216     1587365.355      329752.711
     1585979.417      332064.188     1589529.764      334685.716
     1592772.628      334915.544     1591610.927      336953.077
     1592190.789       342402.73     1595501.553      345347.174
     1590347.039      351581.549     1587949.601       359485.69
     1583911.932      356533.828     1583340.094      360541.619
     1579173.427      360196.133     1581539.946      357819.103
     1581818.592      354458.426     1578937.082      352644.624
     1577069.894      353938.895     1579182.018       359434.12

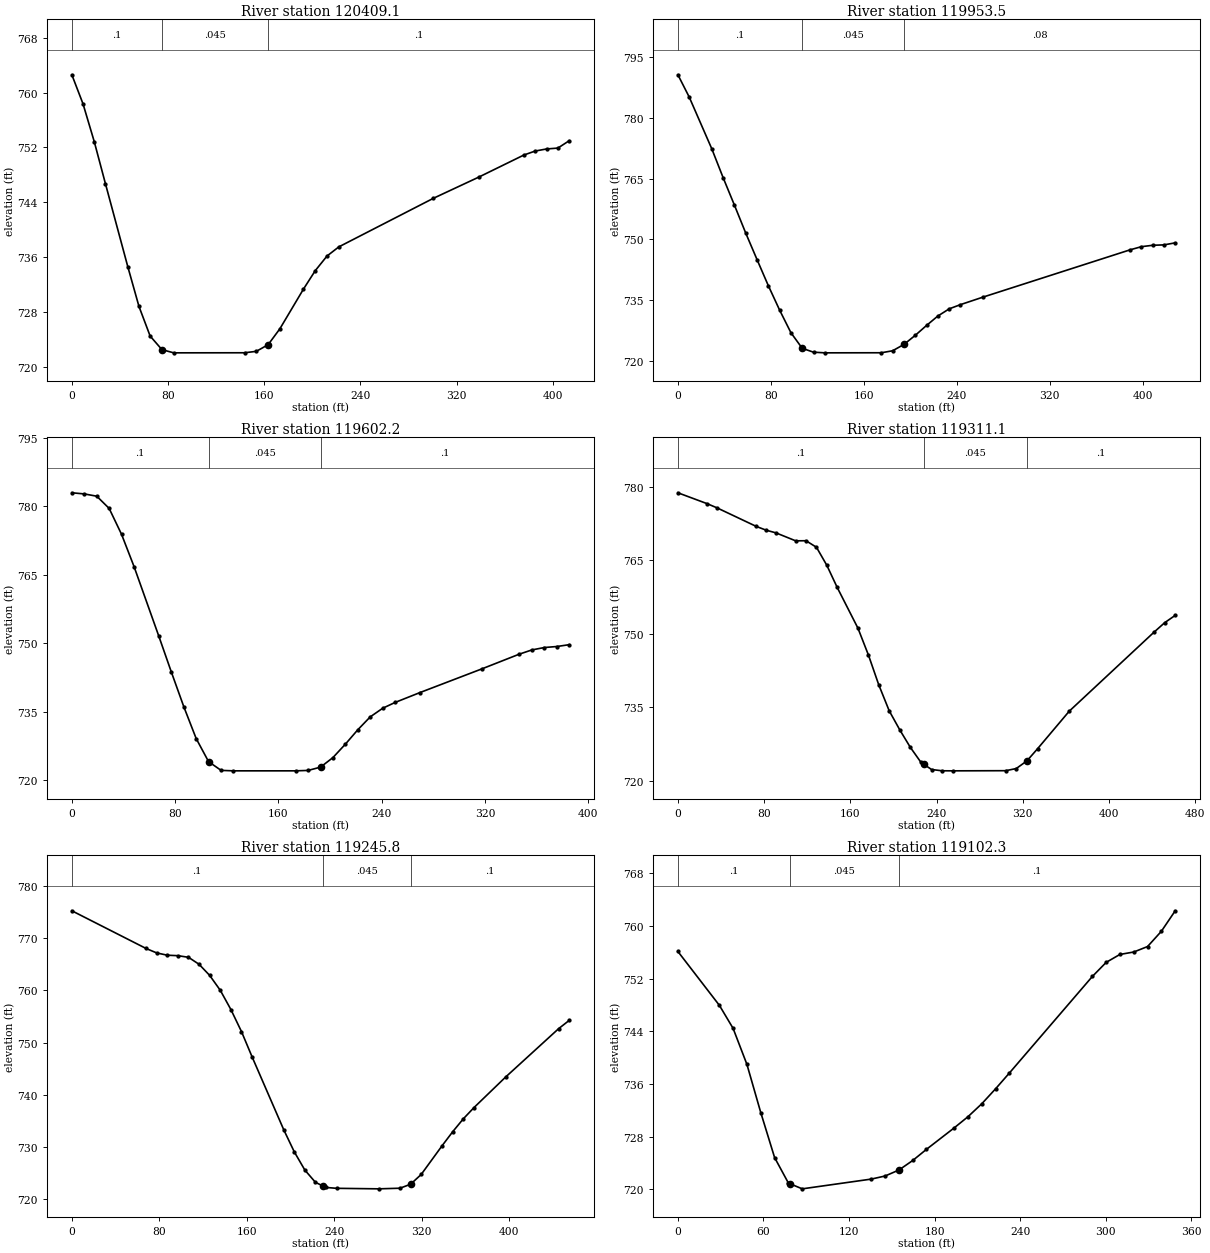
Type RM Length L Ch R = 1 ,120409.1,454.3,455.6,456.8
XS GIS Cut Line= 4
     1595893.286      312028.063     1595903.702      312092.299
     1596033.911       312288.48     1596115.525      312366.612
#Sta/Elev= 24
       0  762.59     9.3  758.34    18.6  752.85    27.9  746.71    46.5  734.59
    55.8  728.78    65.1  724.45    74.9  722.47    84.7     722   143.6  722.01
   153.4  722.22   163.2  723.19     173  725.52   192.6  731.31   202.4     734
   212.2  736.14     222  737.47   300.5  744.55   338.2  747.64   375.9  750.88
   385.3  751.46   394.7  751.76   404.1  751.89   413.5  752.96
#Mann= 3 , 0 , 0
       0      .1       0    74.9    .045       0   163.2      .1       0
Bank Sta=74.9,163.2
XS Rating Curve= 0 ,0
Exp/Cntr=0.3,0.1

Type RM Length L Ch R = 1 ,119953.5,352.4,351.2,350
XS GIS Cut Line= 2
     1595444.952      312199.512     1595661.966      312568.435
#Sta/Elev= 27
       0  790.69     9.7  785.21    29.2  772.38    38.9  765.29    48.6  758.52
    58.4  751.57    68.1  745.04    77.8  738.61    87.6  732.52    97.3  726.96
     107  723.12   116.7  722.16   126.5     722   175.1  722.02   184.8  722.51
   194.6  724.09   204.3  726.33     214  728.77   223.7  731.09   233.5  732.87
   243.2  733.91   262.6  735.77   389.1  747.44   398.8  748.22   408.6  748.57
   418.3  748.67     428  749.17
#Mann= 3 , 0 , 0
       0      .1       0     107    .045       0   194.6     .08       0
Bank Sta=107,194.6
XS Rating Curve= 0 ,0
Exp/Cntr=0.3,0.1

Type RM Length L Ch R = 1 ,119602.2,284.1,291.2,297.9
XS GIS Cut Line= 2
     1595136.792      312383.973     1595349.466      312705.154
#Sta/Elev= 29
       0  782.97     9.6  782.72    19.3  782.22    28.9  779.54    38.5  773.86
    48.2  766.77    67.4   751.5      77  743.72    86.7  736.07    96.3  729.08
   105.9  724.02   115.6   722.1   125.2     722   173.3     722     183  722.09
   192.6  722.81   202.2   724.9   211.9  727.86   221.5  731.01   231.1  733.83
   240.8  735.73   250.4     737   269.6  739.16   317.8  744.38   346.7   747.6
   356.3  748.51     366  749.04   375.6  749.26   385.2  749.66
#Mann= 3 , 0 , 0
       0      .1       0   105.9    .045       0   192.6      .1       0
Bank Sta=105.9,192.6
XS Rating Curve= 0 ,0
Exp/Cntr=0.3,0.1

Type RM Length L Ch R = 1 ,119311.1,63.5,65.3,67.3
XS GIS Cut Line= 4
     1595041.306      312403.505     1594964.466      312481.188
     1594940.161      312564.522     1595013.077       312819.73
#Sta/Elev= 30
       0  778.82    27.3  776.58    36.4  775.73    72.8  771.94      82  771.17
    91.1  770.62   109.3     769   118.9  769.02   128.6  767.68   138.2     764
   147.8  759.49   167.1  751.14   176.8  745.67   186.4  739.57   196.1  734.26
   205.9  730.37   215.7   726.8   225.6  723.72     228723.3649   235.4  722.27
   245.2  722.01     255     722   304.2  722.03     314  722.47   323.9  724.04
   333.7   726.5   363.2   734.2   441.8  750.33   451.7  752.27   461.5  753.77
#Mann= 3 , 0 , 0
       0      .1       0     228    .045       0   323.9      .1       0
Bank Sta=228,323.9
XS Rating Curve= 0 ,0
Exp/Cntr=0.3,0.1

Type RM Length L Ch R = 1 ,119245.8,139.8,143.5,147.2
XS GIS Cut Line= 3
     1594761.358      312442.567     1594881.133      312555.841
     1594936.688      312840.563
#Sta/Elev= 30
       0  775.26    67.9  768.04    77.6  767.19    87.3  766.75      97  766.66
   106.7  766.35   116.4  765.01   126.1  762.88   135.8  760.03   145.5  756.35
   155.2  752.12   164.8  747.33   193.9   733.3   203.5  729.09   213.2  725.59
   222.9  723.24   229.4722.5833   232.5  722.27   242.2   722.1   280.9     722
   300.2  722.12   309.9  722.88   319.6  724.75   338.9   730.3   348.6  732.98
   358.2  735.42   367.9  737.56   396.9  743.42   445.3  752.67     455  754.26
#Mann= 3 , 0 , 0
       0      .1       0   229.4    .045       0   309.9      .1       0
Bank Sta=229.4,309.9
XS Rating Curve= 0 ,0
Exp/Cntr=0.3,0.1

Type RM Length L Ch R = 1 ,119102.3,248.4,263.9,279.6
XS GIS Cut Line= 2
     1594759.605      312562.786     1594770.039      312911.317
#Sta/Elev= 26
       0  756.11    29.1  747.93    38.7  744.44    48.4  738.97    58.1  731.66
    67.8  724.83    77.5  720.95    78.6720.8513    87.2  720.08   135.6  721.56
   145.3  722.03     155  722.94   164.7  724.39   174.3  726.08   193.7  729.33
   203.4  731.03   213.1     733   222.8  735.28   232.5  737.68   290.6  752.32
   300.3  754.46   309.9  755.66   319.6  756.03   329.3  756.86     339  759.18
   348.7  762.29
#Mann= 3 , 0 , 0
       0      .1       0    78.6    .045       0     155      .1       0
Bank Sta=78.6,155
XS Rating Curve= 0 ,0
Exp/Cntr=0.3,0.1

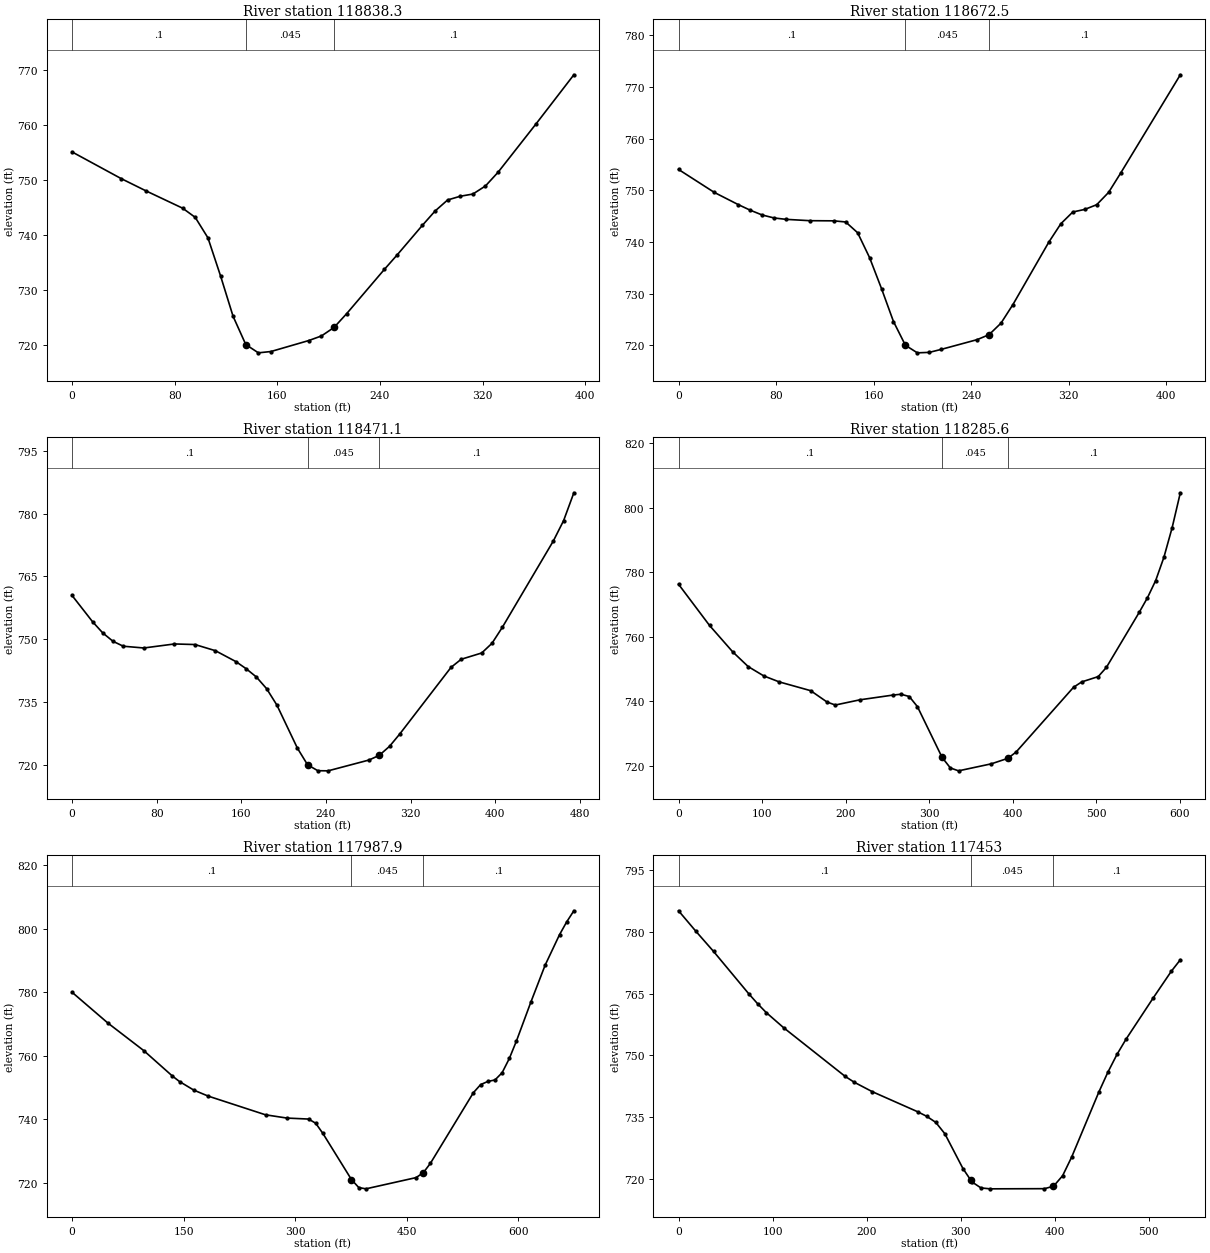
Type RM Length L Ch R = 1 ,118838.3,161.8,165.8,169.6
XS GIS Cut Line= 3
     1594594.674      312524.591     1594554.744       312600.98
     1594370.733      312844.043
#Sta/Elev= 26
       0  755.12    38.3  750.26    57.5  748.04    86.2  744.87      96   743.2
   105.9  739.47   115.7  732.56   125.5  725.18   135.4  720.04   145.2  718.53
     155  718.77   184.5  720.77   194.4  721.61   204.2  723.16     214  725.66
   243.5  733.75   253.4  736.37     273  741.74   282.9  744.35   292.7  746.37
   302.6  747.05   312.4  747.45   322.2  748.92     332  751.41   361.6  760.22
   391.1  769.17
#Mann= 3 , 0 , 0
       0      .1       0   135.4    .045       0   204.2      .1       0
Bank Sta=135.4,204.2
XS Rating Curve= 0 ,0
Exp/Cntr=0.3,0.1

Type RM Length L Ch R = 1 ,118672.5,198.7,201.4,204.2
XS GIS Cut Line= 3
     1594544.327      312455.147     1594455.786      312496.813
     1594223.164      312707.324
#Sta/Elev= 30
       0  754.03    29.4  749.58    48.9  747.24    58.7  746.16    68.5  745.23
    78.3  744.65    88.1  744.38   107.7  744.12   127.3  744.09   137.1  743.87
   146.9  741.79   156.7  736.98   166.5  730.98   176.3  724.62   186.1  720.02
   195.9  718.56   205.7  718.65   215.5  719.23   244.9  721.11   254.7  722.07
   264.5   724.3   274.3   727.9   303.7  739.96   313.6  743.53   323.4   745.8
   333.2   746.3     343  747.21   352.8   749.6   362.6   753.3   411.6  772.34
#Mann= 3 , 0 , 0
       0      .1       0   186.1    .045       0   254.7      .1       0
Bank Sta=186.1,254.7
XS Rating Curve= 0 ,0
Exp/Cntr=0.3,0.1

Type RM Length L Ch R = 1 ,118471.1,184.4,185.5,186.7
XS GIS Cut Line= 2
     1594452.313      312271.119     1594064.744      312544.564
#Sta/Elev= 30
       0  760.46    19.4   754.2      29  751.54    38.7  749.54    48.4  748.37
    67.8  747.95    96.8  748.91   116.2  748.77   135.5   747.3   154.9   744.7
   164.6     743   174.2  741.04   183.9  738.25   193.6  734.34     213  724.07
   222.6  720.11   232.3   718.7     242  718.67   280.7  721.25   290.4  722.37
   300.1  724.52   309.8  727.47   358.2  743.33   367.8  745.26   387.2  746.76
   396.9  749.06   406.6  752.84     455   773.5   464.6   778.3   474.3  784.94
#Mann= 3 , 0 , 0
       0      .1       0   222.6    .045       0   290.4      .1       0
Bank Sta=222.6,290.4
XS Rating Curve= 0 ,0
Exp/Cntr=0.3,0.1

Type RM Length L Ch R = 1 ,118285.6,297.2,297.6,298
XS GIS Cut Line= 3
     1594464.049      312134.407     1594316.897      312153.063
     1593934.536      312394.824
#Sta/Elev= 30
       0  776.31    37.1  763.52    64.9  755.31    83.4  750.75     102  747.86
   120.5     746   158.2  743.27   177.8  739.74   187.7  738.82   217.2  740.44
   256.5   741.9   266.3  742.17   276.2  741.46     286  738.31   315.5  722.56
   325.4  719.29   335.2  718.39   374.5  720.57   394.2  722.27     404   724.2
   472.9  744.34   482.7     746   502.4  747.64   512.2   750.5   551.5  767.59
   561.4  772.14   571.2  777.46     581  784.64   590.9  793.87   600.7   804.7
#Mann= 3 , 0 , 0
       0      .1       0   315.5    .045       0   394.2      .1       0
Bank Sta=315.5,394.2
XS Rating Curve= 0 ,0
Exp/Cntr=0.3,0.1

Type RM Length L Ch R = 1 ,117987.9,532.4,534.9,537.4
XS GIS Cut Line= 3
      1594318.65      311787.185     1594141.549      311920.424
     1593754.414      312156.109
#Sta/Elev= 30
       0  780.06    48.2  770.36    96.4  761.69   134.9  753.68   144.5  751.94
   163.8  749.23   183.1  747.35   260.2  741.46   289.1  740.43   318.1  740.12
   327.7   738.8   337.3  735.61   375.8721.0558   385.6  718.55   395.2  718.14
   462.7  721.68   472.4  723.22     482  726.19   539.8  748.44   549.5  750.97
   559.1  751.96   568.8  752.44   578.4  754.71   588.1   759.2   597.7  764.73
     617  776.92   636.3  788.62   655.6  798.19   665.2  802.21   674.9  805.73
#Mann= 3 , 0 , 0
       0      .1       0   375.8    .045       0   472.4      .1       0
Bank Sta=375.8,472.4
XS Rating Curve= 0 ,0
Exp/Cntr=0.3,0.1

Type RM Length L Ch R = 1 ,117453  ,404.9,404.1,403.2
XS GIS Cut Line= 3
     1594059.952      311486.397     1593882.869      311479.452
     1593559.952      311630.494
#Sta/Elev= 30
       0  785.19    18.6  780.16    37.3  775.28    74.6  765.01      84  762.59
    93.3  760.41   111.9   756.7   177.2  744.88   186.8  743.46   206.1  741.15
   254.3  736.27   263.9  735.16   273.6  733.68   283.2  730.93   302.5  722.44
   310.8719.6215   312.1  719.18   321.7  717.72   331.4   717.5   389.2  717.54
   398.8  718.13   408.5  720.69   418.1  725.22     447  741.04   456.6  745.87
   466.3  750.21   475.9  753.91   504.8  763.95   524.1  770.46   533.7  773.26
#Mann= 3 , 0 , 0
       0      .1       0   310.8    .045       0   398.8      .1       0
Bank Sta=310.8,398.8
XS Rating Curve= 0 ,0
Exp/Cntr=0.3,0.1

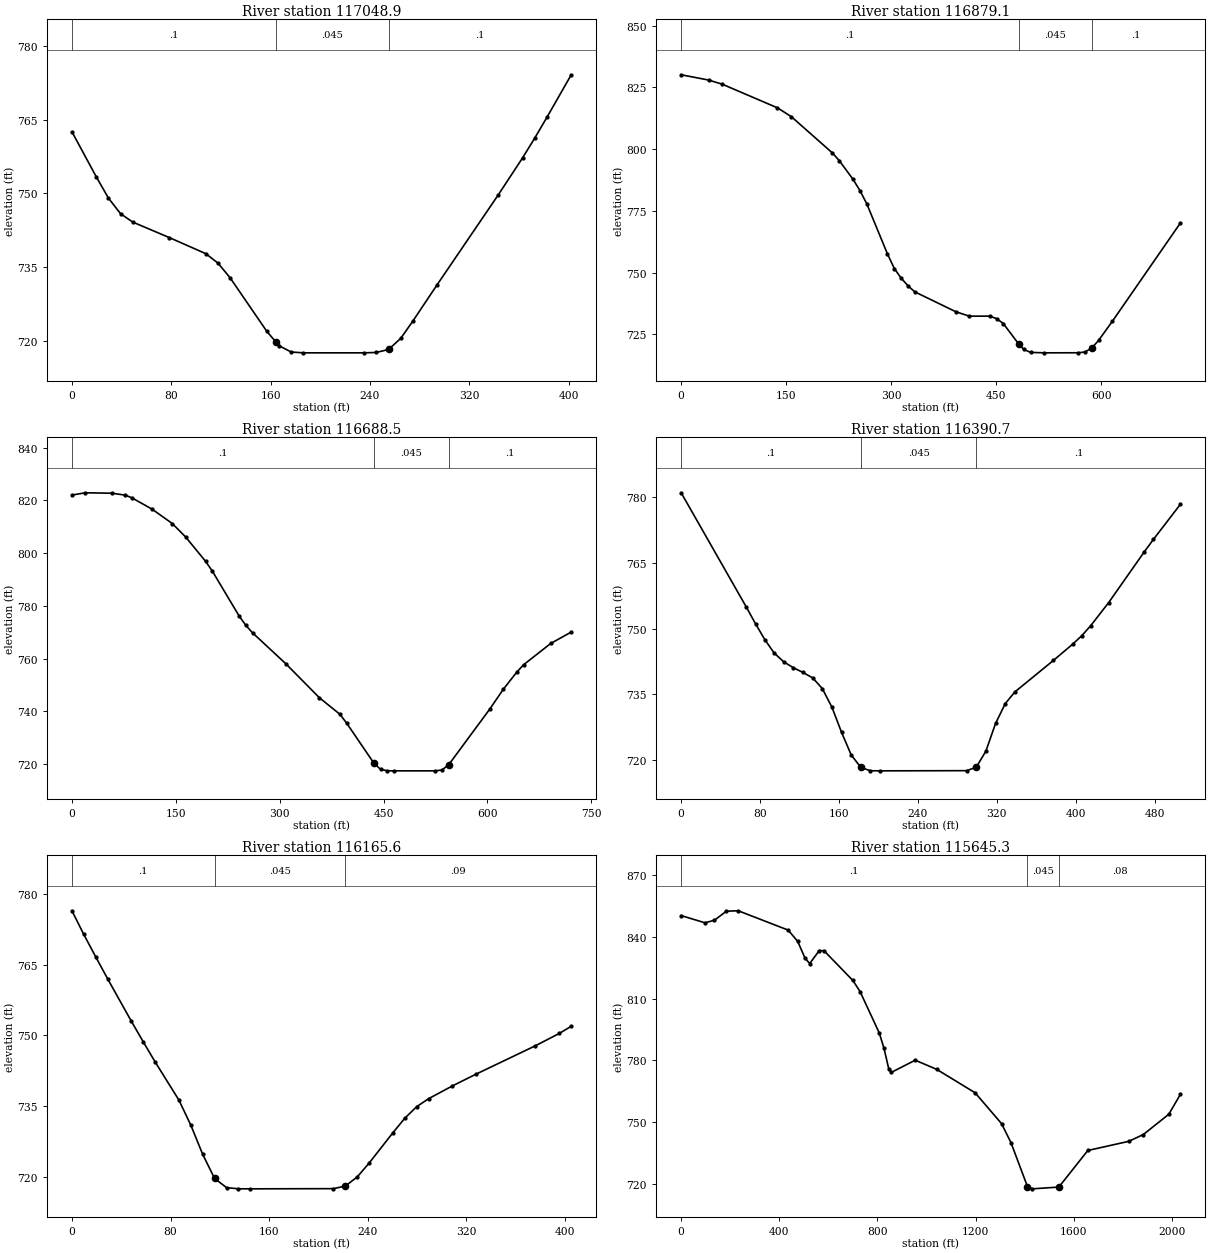
Type RM Length L Ch R = 1 ,117048.9,171.1,169.8,168.6
XS GIS Cut Line= 2
     1593716.202      311102.716     1593358.563      311286.744
#Sta/Elev= 25
       0  762.54    19.6  753.37    29.4  749.03    39.2  745.84      49  744.14
    78.5  740.98   107.9   737.7   117.7  735.77   127.5  732.76     157  721.87
   164.2719.7321   166.8  718.96   176.6  717.67   186.4   717.5   235.4   717.5
   245.2  717.58   255.1  718.19   264.9  720.46   274.7     724   294.3  731.42
   343.4  749.68     363  757.23   372.8  761.26   382.6  765.48   402.2  774.16
#Mann= 3 , 0 , 0
       0      .1       0   164.2    .045       0   255.1      .1       0
Bank Sta=164.2,255.1
XS Rating Curve= 0 ,0
Exp/Cntr=0.3,0.1

Type RM Length L Ch R = 1 ,116879.1,190.7,190.6,190.4
XS GIS Cut Line= 3
       1593947.4      310944.852     1593643.286      310934.313
     1593290.855      311140.911
#Sta/Elev= 30
       0  830.13    39.3  827.99    58.9  826.29   137.4  816.75   157.1  813.21
     216  798.45   225.8  795.32   245.4  787.77   255.2  783.25     265  777.86
   294.5  757.58   304.3  751.66     314  747.79   323.8  744.66   333.5  742.21
   391.8  734.19   411.3  732.36   440.5  732.36   450.2  731.37   459.9  729.37
   482.2  720.96   489.1  718.89   498.8  717.69   518.3   717.5   566.9  717.53
   576.6  717.86   586.4  719.48   596.1  722.61   615.6  730.28   712.8  770.12
#Mann= 3 , 0 , 0
       0      .1       0   482.2    .045       0   586.4      .1       0
Bank Sta=482.2,586.4
XS Rating Curve= 0 ,0
Exp/Cntr=0.3,0.1

Type RM Length L Ch R = 1 ,116688.5,299.7,297.8,296
XS GIS Cut Line= 3
      1593626.22      310506.484     1593457.522      310821.466
     1593145.022       311007.23
#Sta/Elev= 30
       0  822.05    19.3  822.92    57.9  822.75    77.3  822.01    86.9  820.96
   115.9  816.67   144.9  811.26   164.2  806.15   193.1  796.89   202.8  793.18
   241.4   776.2   251.1  772.64   260.7  769.85     309  758.05   357.3  745.21
   386.8  738.97   396.6  735.61   435.9  720.44   445.7  718.04   455.6  717.51
   465.4   717.5   524.4   717.5   534.2  717.81     544  719.82     603  740.81
   622.6  748.35   642.2   754.9   652.1  757.72   691.4  765.81   720.9  770.11
#Mann= 3 , 0 , 0
       0      .1       0   435.9    .045       0     544      .1       0
Bank Sta=435.9,544
XS Rating Curve= 0 ,0
Exp/Cntr=0.3,0.1

Type RM Length L Ch R = 1 ,116390.7,224.6,225.1,225.6
XS GIS Cut Line= 4
     1593403.702      310526.327     1593311.688      310547.161
     1593065.161      310722.508     1592983.563      310795.424
#Sta/Elev= 30
       0  781.05      66  754.96    75.5  751.07    84.9  747.46    94.3  744.42
   104.1   742.4   113.9  741.05   123.6  739.98   133.4  738.74   143.1  736.31
   152.9  732.04   162.7  726.27   172.4  721.15   182.2  718.27   191.9  717.52
   201.7   717.5   289.5  717.54   299.3  718.34     309     722   318.8  728.32
   328.6  732.85   338.3  735.52   377.4  742.72   396.9  746.43     406  748.33
   415.1  750.62   433.4  755.92   469.8  767.61   478.9   770.4   506.3  778.43
#Mann= 3 , 0 , 0
       0      .1       0   182.2    .045       0   299.3      .1       0
Bank Sta=182.2,299.3
XS Rating Curve= 0 ,0
Exp/Cntr=0.3,0.1

Type RM Length L Ch R = 1 ,116165.6,551.3,520.4,484.4
XS GIS Cut Line= 2
     1593223.147      310342.299     1592888.077       310569.73
#Sta/Elev= 27
       0  776.41     9.6   771.4    19.3  766.64    28.9  762.02    48.2     753
    57.8  748.66    67.5  744.38    86.8  736.29    96.4  731.01   106.1  724.79
   115.7   719.7   125.4  717.76     135  717.51   144.6   717.5   212.1  717.54
   221.8  718.09   231.4  720.02     241  722.94   260.3  729.37     270  732.46
   279.6   734.9   289.3   736.6   308.5  739.29   327.8   741.8     376  747.82
   395.3  750.42     405  751.94
#Mann= 3 , 0 , 0
       0      .1       0   115.7    .045       0   221.8     .09       0
Bank Sta=115.7,221.8
XS Rating Curve= 0 ,0
Exp/Cntr=0.3,0.1

Type RM Length L Ch R = 1 ,115645.3,129,130.3,136.6
XS GIS Cut Line= 6
     1592440.282      308648.845     1592679.589      309070.487
     1592761.341      309887.438     1592691.897      309953.411
     1592830.786      310415.216     1592790.855      310561.049
#Sta/Elev= 30
       0  850.34      97  846.84   135.8  848.09   184.2  852.48   232.7  852.68
   436.3  843.28   475.1  837.78   504.4  829.76   523.9  827.01     563  833.36
   582.6  833.22   699.8   818.8   729.2   813.4   807.4  793.29   826.9  785.78
   846.5  775.64   856.2  774.09     954  780.04    1042  775.56  1198.3  764.18
  1305.8  749.22  1344.2  739.99  1411.5   718.6  1431.2   717.5  1539.4  718.36
  1657.5  736.14  1824.8  740.61  1883.9  743.91  1987.8  753.78  2035.1  763.47
#Mann= 3 , 0 , 0
       0      .1       0  1411.5    .045       0  1539.4     .08       0
Bank Sta=1411.5,1539.4
XS Rating Curve= 0 ,0
Exp/Cntr=0.3,0.1

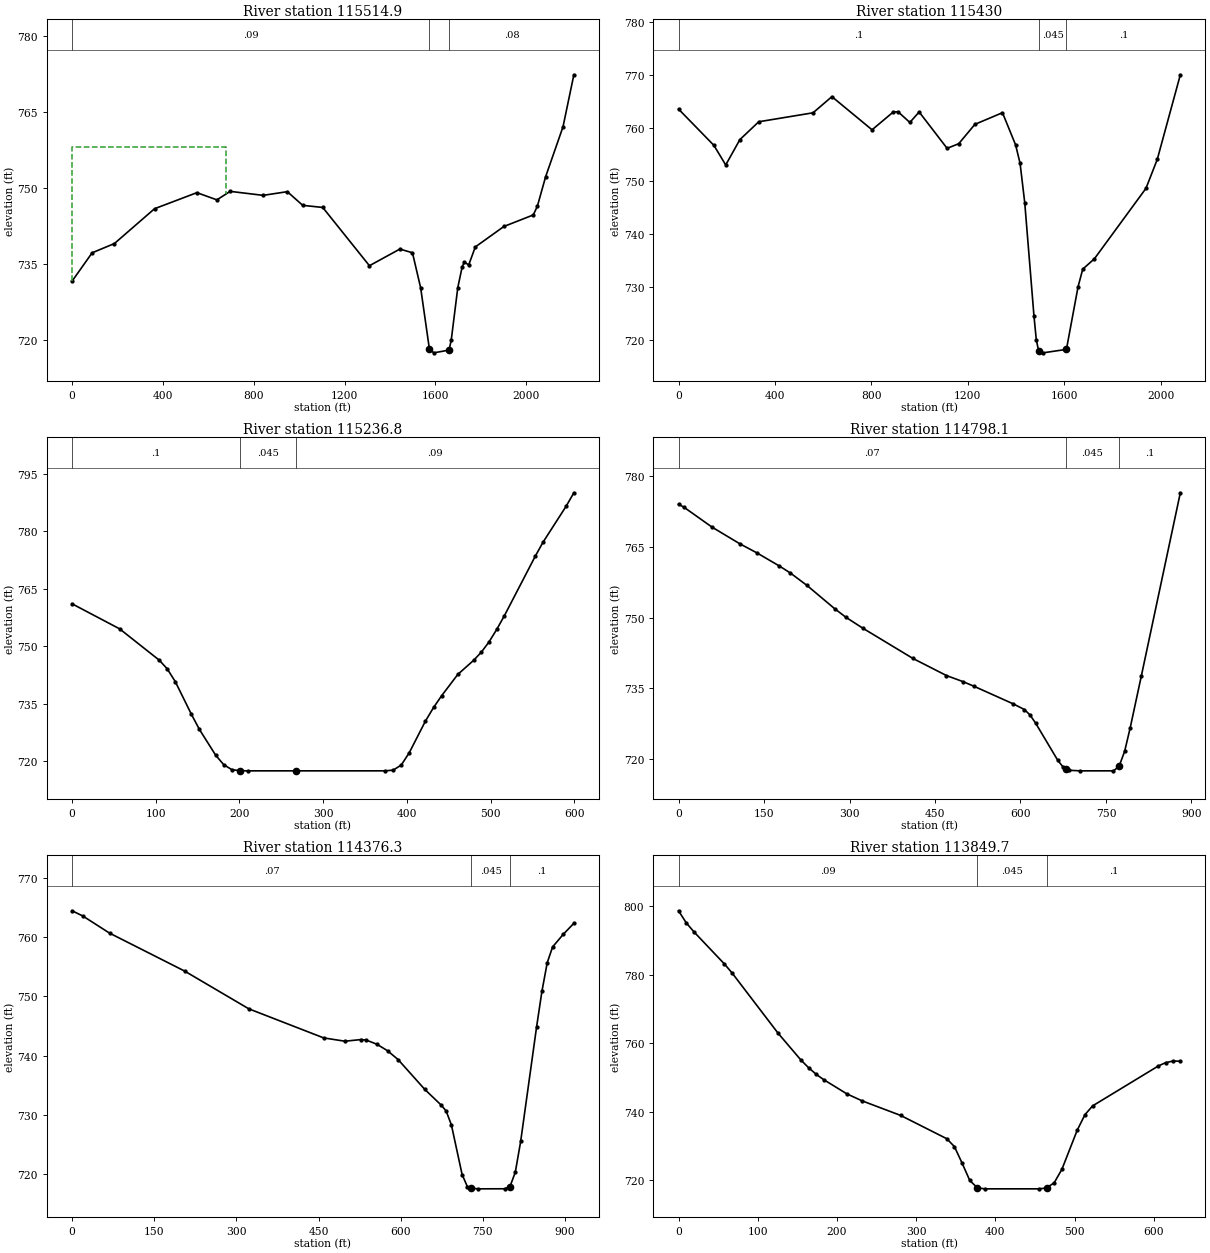
Type RM Length L Ch R = 1 ,115514.9,85,85,85
XS GIS Cut Line= 6
      1591440.71      309244.321     1592078.418      309230.646
     1592364.849      309476.678     1592728.355       310413.48
     1592738.772       310475.98     1592690.161      310590.563
#Sta/Elev= 30
       0  731.66    88.3  737.26   186.4  739.09   363.1  745.97   549.5  749.14
   637.8  747.72     696   749.4   841.2  748.61   947.7  749.34  1015.4  746.64
  1103.7  746.22  1309.2  734.71  1443.2     738  1498.7  737.27  1534.9  730.31
  1573.4  718.22  1592.6   717.5  1659.8  718.04  1669.5  720.04  1698.3   730.4
  1717.5  734.47  1727.1  735.44  1746.3  734.86  1775.4  738.42  1901.2  742.46
  2030.6  744.74  2048.7  746.47  2084.9  752.28  2161.5  762.15  2209.3  772.43
#Mann= 3 , 0 , 0
       0     .09       0  1573.4    .045       0  1659.8     .08       0
#XS Ineff= 2 , 0
          675.82  758.12
Permanent Ineff=
       F       F
Bank Sta=1573.4,1659.8
XS Rating Curve= 0 ,0
Exp/Cntr=0.3,0.1

Type RM Length L Ch R = 1 ,115430  ,193.2,193.1,193.2
XS GIS Cut Line= 6
     1591426.821       309333.21     1592033.765      309334.599
     1592307.905      309556.554     1592643.286      310427.369
     1592653.702      310489.869     1592605.091      310604.452
#Sta/Elev= 30
       0  763.52   146.8  756.67   195.8  752.97   254.5  757.76   332.8  761.13
     558  762.82   636.3  765.87   802.9  759.61   891.1  762.98   910.7  763.02
   959.7     761   998.3  762.98  1114.3  756.11  1162.6  756.99  1229.6  760.64
    1344  762.84  1398.5  756.76  1417.1  753.26  1436.4  745.84  1474.8  724.39
  1484.4  719.94    1494  717.87    1512   717.5  1609.3  718.15  1657.6  729.97
    1677   733.3  1725.4  735.26  1939.4  748.56  1986.2  754.02  2081.9     770
#Mann= 3 , 0 , 0
       0      .1       0    1494    .045       0  1609.3      .1       0
Bank Sta=1494,1609.3
XS Rating Curve= 0 ,0
Exp/Cntr=0.3,0.1

Type RM Length L Ch R = 1 ,115236.8,430.6,438.8,446.8
XS GIS Cut Line= 4
     1592341.202      309941.258     1592304.744      310048.897
     1592422.799      310385.702     1592398.494      310512.438
#Sta/Elev= 30
       0  761.08    56.8  754.55   104.2  746.37   113.6  744.14   123.3  740.79
   142.6  732.25   152.2  728.29   171.5  721.61   181.2  719.11   190.8  717.82
   200.5  717.53   210.1   717.5     268   717.5   374.1   717.5   383.7  717.68
   393.4  719.02     403  722.26   422.3   730.5     432  734.04   441.6   737.1
   460.9  742.65   479.8  746.33     489  748.45   498.2  751.13   507.4  754.38
   516.6  757.98   553.5  773.51   562.7  777.13   590.4  786.55   599.6  790.05
#Mann= 3 , 0 , 0
       0      .1       0   200.5    .045       0     268     .09       0
Bank Sta=200.5,268
XS Rating Curve= 0 ,0
Exp/Cntr=0.3,0.1

Type RM Length L Ch R = 1 ,114798.1,416.6,421.8,426.9
XS GIS Cut Line= 3
       1592148.5      309676.246     1591957.522       310007.23
     1591948.841      310505.494
#Sta/Elev= 30
       0  774.09     9.8  773.41    58.8  769.21   107.8  765.66   137.2  763.77
   176.4     761     196   759.5   225.4  756.84   274.4  751.86     294  750.06
   323.3  747.77   411.4  741.34   470.1  737.72   499.4  736.42   518.9  735.42
   587.3  731.71   606.9  730.51   616.6  729.37   626.4  727.66   665.5  719.72
   675.3  718.23   679.6717.9596     685  717.62   704.6   717.5   763.2   717.5
     773  718.45   782.8  721.64   792.5  726.61   812.1  737.64   880.5   776.5
#Mann= 3 , 0 , 0
       0     .07       0   679.6    .045       0     773      .1       0
Bank Sta=679.6,773
XS Rating Curve= 0 ,0
Exp/Cntr=0.3,0.1

Type RM Length L Ch R = 1 ,114376.3,528.7,526.5,524.5
XS GIS Cut Line= 3
     1591632.875      309551.246     1591620.716      309981.188
     1591499.188      310451.674
#Sta/Elev= 30
       0  764.44    19.6  763.56    68.4  760.67   205.3  754.27   322.6  747.89
   459.3  742.98   498.1  742.42   527.3   742.7     537  742.61   556.5  741.91
   575.9  740.81   595.3  739.31   643.9  734.28   673.1   731.7   682.8  730.66
   692.5  728.27     712  719.92   721.7  717.85   728.5717.6116   741.1   717.5
   789.7  717.51   799.4  717.89   809.1   720.3   818.9  725.51     848  744.86
   857.7  750.84   867.4  755.68   877.2  758.34   896.6  760.46     916  762.33
#Mann= 3 , 0 , 0
       0     .07       0   728.5    .045       0   799.4      .1       0
Bank Sta=728.5,799.4
XS Rating Curve= 0 ,0
Exp/Cntr=0.3,0.1

Type RM Length L Ch R = 1 ,113849.7,351.9,324,295.8
XS GIS Cut Line= 4
     1590878.824      309864.122     1591049.536      310021.119
     1591002.661      310317.994     1591044.327      310410.008
#Sta/Elev= 30
       0  798.63     9.7  795.13    19.3  792.52      58  783.09    67.6  780.49
   125.6  762.93   154.6  755.06   164.3  752.82     174  750.88   183.6  749.31
   212.6   745.2   231.9  743.16   280.4  738.92   338.6  732.13   348.3  729.82
     358     725   367.7  719.94   377.4  717.77     387   717.5   454.9   717.5
   464.6  717.74   474.3  719.29     484   723.2   503.4  734.65   513.1  739.14
   522.8  741.71   605.9  753.37   615.1  754.33   624.3  754.78   633.5  754.75
#Mann= 3 , 0 , 0
       0     .09       0   377.4    .045       0   464.6      .1       0
Bank Sta=377.4,464.6
XS Rating Curve= 0 ,0
Exp/Cntr=0.3,0.1

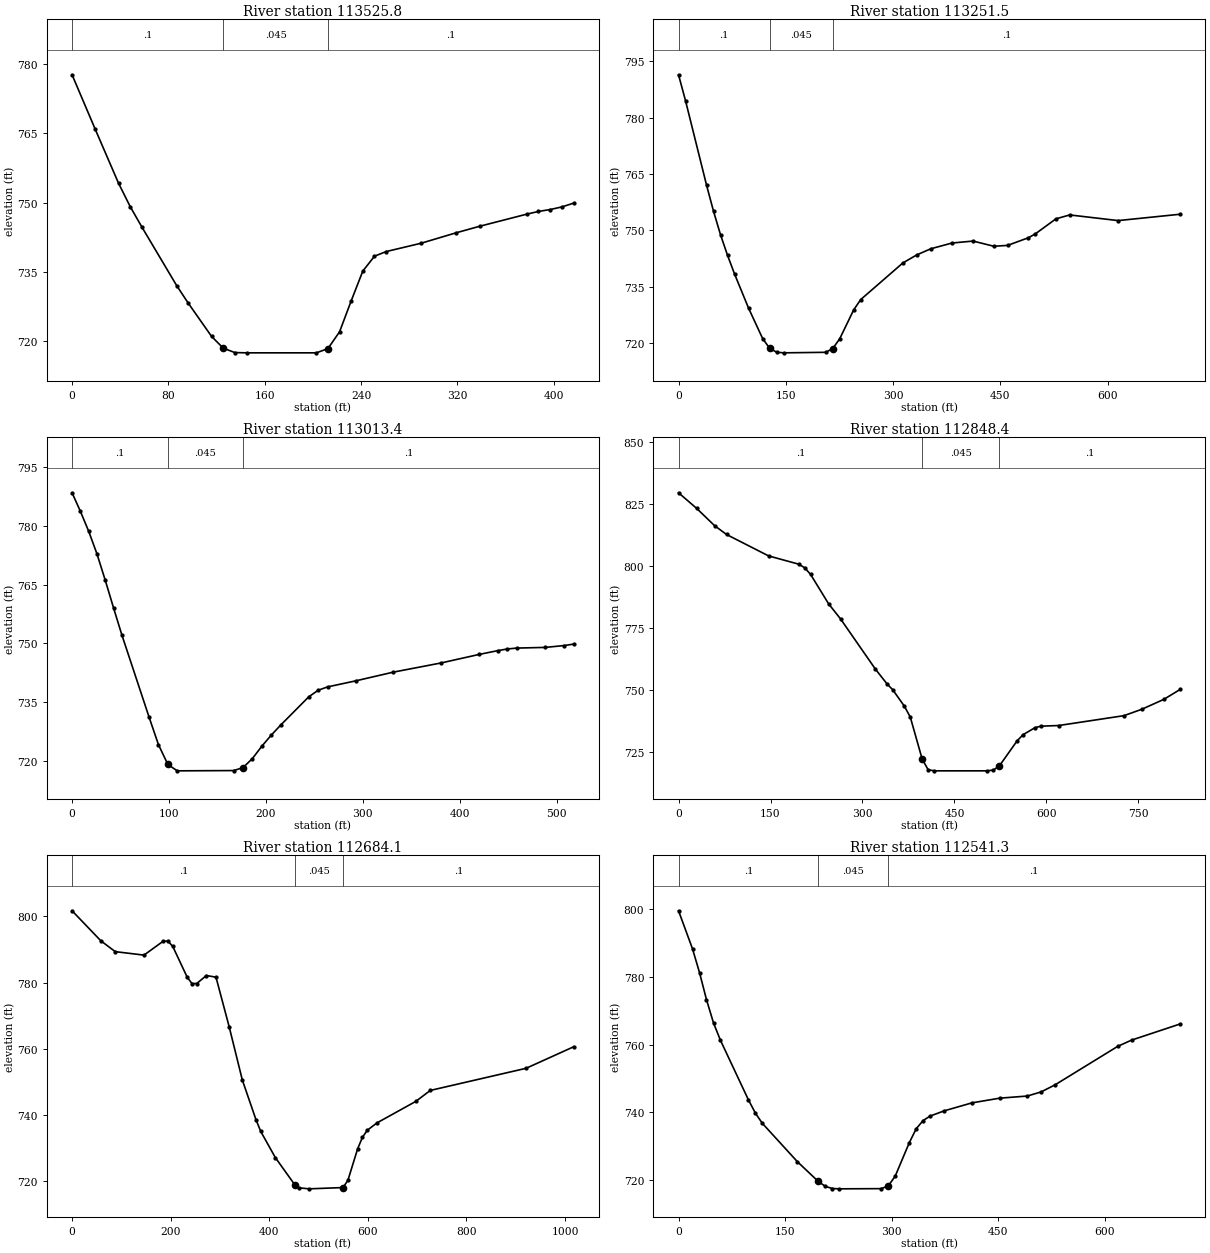
Type RM Length L Ch R = 1 ,113525.8,289,274.3,259.6
XS GIS Cut Line= 3
     1590610.299      310285.008     1590882.869      310430.841
     1590990.508      310430.841
#Sta/Elev= 26
       0   777.7    19.3  765.87    38.6  754.22    48.3  749.15      58  744.73
    86.9  732.05    96.6  728.22   115.9  721.05   125.6  718.51   135.2  717.56
   144.9   717.5   202.9   717.5   212.5  718.41   222.2  722.06   231.8  728.72
   241.5   735.2   251.2  738.42   260.8  739.42   289.8  741.22   318.9  743.48
   338.5   744.9   377.6  747.52   387.4  748.11   397.2  748.53     407   749.1
   416.8  749.93
#Mann= 3 , 0 , 0
       0      .1       0   125.6    .045       0   212.5      .1       0
Bank Sta=125.6,212.5
XS Rating Curve= 0 ,0
Exp/Cntr=0.3,0.1

Type RM Length L Ch R = 1 ,113251.5,238.5,238.1,237.8
XS GIS Cut Line= 4
     1590594.674      310654.799     1590914.119      310604.452
     1590955.786      310526.327     1591210.994       310663.48
#Sta/Elev= 30
       0  791.36     9.8  784.45    39.2  762.02      49  755.06    58.8  748.81
    68.6  743.36    78.4  738.41      98  729.34   117.6   721.3   127.4  718.71
   137.2  717.67     147   717.5   205.8  717.64   215.6  718.62   225.4  721.24
     245  728.93   254.8  731.66   313.6  741.36   333.2  743.52   352.9  745.15
   382.4  746.67   411.9  747.19   440.9  745.81   460.2  746.04   489.2  748.07
   498.8  749.08   527.8   753.1   547.1  754.13   614.7  752.63   701.7  754.32
#Mann= 3 , 0 , 0
       0      .1       0   127.4    .045       0   215.6      .1       0
Bank Sta=127.4,215.6
XS Rating Curve= 0 ,0
Exp/Cntr=0.3,0.1

Type RM Length L Ch R = 1 ,113013.4,166.1,165,163.8
XS GIS Cut Line= 4
     1590693.633      310895.685      1590748.32      310870.945
     1591006.133      310826.674     1591201.445      310842.299
#Sta/Elev= 30
       0  788.46     8.6  783.72    17.2   778.6    25.7  772.85    34.3  766.08
    42.9  758.99    51.4  752.15    79.4  731.23    89.1  724.19    98.8  719.13
   108.5   717.5   166.6  717.57   176.3  718.31     186  720.63   195.7  723.77
   205.4  726.59     215  729.13   244.1  736.38   253.8  738.06   263.5  738.92
   292.5  740.46   331.4  742.69   380.4  745.02   419.6  747.19   439.2  748.18
     449   748.6   458.8  748.83   488.2     749   507.8  749.48   517.6  749.85
#Mann= 3 , 0 , 0
       0      .1       0    98.8    .045       0   176.3      .1       0
Bank Sta=98.8,176.3
XS Rating Curve= 0 ,0
Exp/Cntr=0.3,0.1

Type RM Length L Ch R = 1 ,112848.4,165.3,164.3,163.3
XS GIS Cut Line= 5
     1590499.622      310799.331     1590712.495       310956.11
     1590776.966      311037.612      1591154.57      310951.674
      1591217.07      310945.164
#Sta/Elev= 30
       0  829.62    29.4  823.36    58.8  816.36    78.3   812.8   146.9  804.16
   195.8  800.85   205.6  799.41   215.4  796.69   244.8  784.83   264.4  778.71
   321.1  758.51     340  752.57   349.4  750.18   368.3  743.58     378  739.17
   397.3  722.28     407  717.99   416.7   717.5   503.8   717.5   513.5  717.82
   523.2  719.47   552.2  729.59   561.9  732.07   581.3   734.9     591  735.51
     620  735.77   726.5  739.75   755.6  742.33   791.5  746.32   818.4  750.37
#Mann= 3 , 0 , 0
       0      .1       0   397.3    .045       0   523.2      .1       0
Bank Sta=397.3,523.2
XS Rating Curve= 0 ,0
Exp/Cntr=0.3,0.1

Type RM Length L Ch R = 1 ,112684.1,144.2,142.9,141.4
XS GIS Cut Line= 5
     1590510.039      311094.904     1590761.341      311243.341
     1590816.029      311197.768      1591185.82      311097.508
     1591414.987      310951.674
#Sta/Elev= 30
       0  801.73    58.4  792.63    87.6  789.35   145.9   788.3   184.8  792.51
   194.6  792.54   204.3  790.91   233.5  781.61   243.2  779.68     253   779.7
   272.4  782.12   291.9  781.62   318.6  766.63   345.3  750.49   372.9   738.5
   382.7  734.89   412.2  726.99   451.5  718.78   461.3  717.79   480.9   717.5
   549.7  717.89   559.5  720.09   579.2  729.61     589  733.12   598.8  735.25
   618.5  737.48   697.1  743.98   726.6  747.31   920.8  754.01  1017.8  760.56
#Mann= 3 , 0 , 0
       0      .1       0   451.5    .045       0   549.7      .1       0
Bank Sta=451.5,549.7
XS Rating Curve= 0 ,0
Exp/Cntr=0.3,0.1

Type RM Length L Ch R = 1 ,112541.3,388.1,387.9,387.6
XS GIS Cut Line= 4
     1590771.758      311372.247     1591153.268      311242.039
     1591260.039      311236.831     1591454.049      311209.487
#Sta/Elev= 30
       0  799.45    19.7  788.21    29.5  781.24    39.3  773.28    49.2  766.39
      59  761.26    98.3  743.74   108.2  739.78     118  736.78   167.2   725.5
   196.6  719.68   206.5  718.23   216.3   717.6   226.1   717.5   285.1  717.56
     295  718.35   304.8  721.24   324.5  731.04   334.3   735.2   344.1  737.64
     354  738.95   373.6  740.48   412.8  742.84   451.7  744.22   490.6  744.85
     510  746.06   529.6  748.14   617.8  759.49   637.4  761.34   705.9  766.11
#Mann= 3 , 0 , 0
       0      .1       0   196.6    .045       0     295      .1       0
Bank Sta=196.6,295
XS Rating Curve= 0 ,0
Exp/Cntr=0.3,0.1