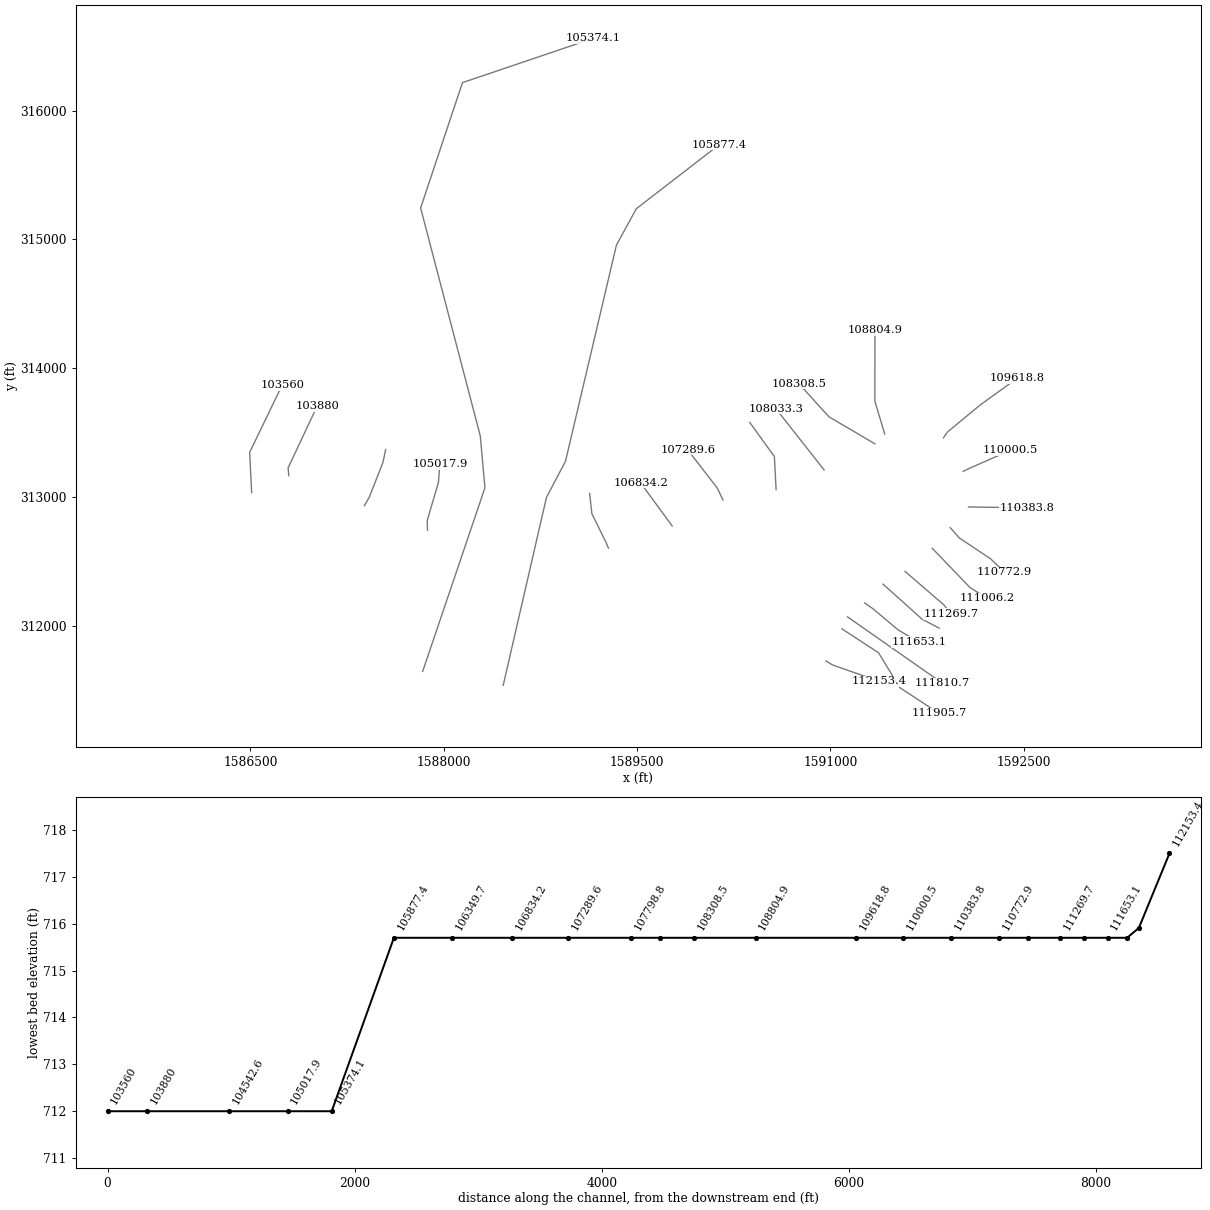
HEC-RAS study MDISLCRK_C.prj: MDISLCRK_C

--- MDISLCRK_C.g01 (geometry) --- (continued)

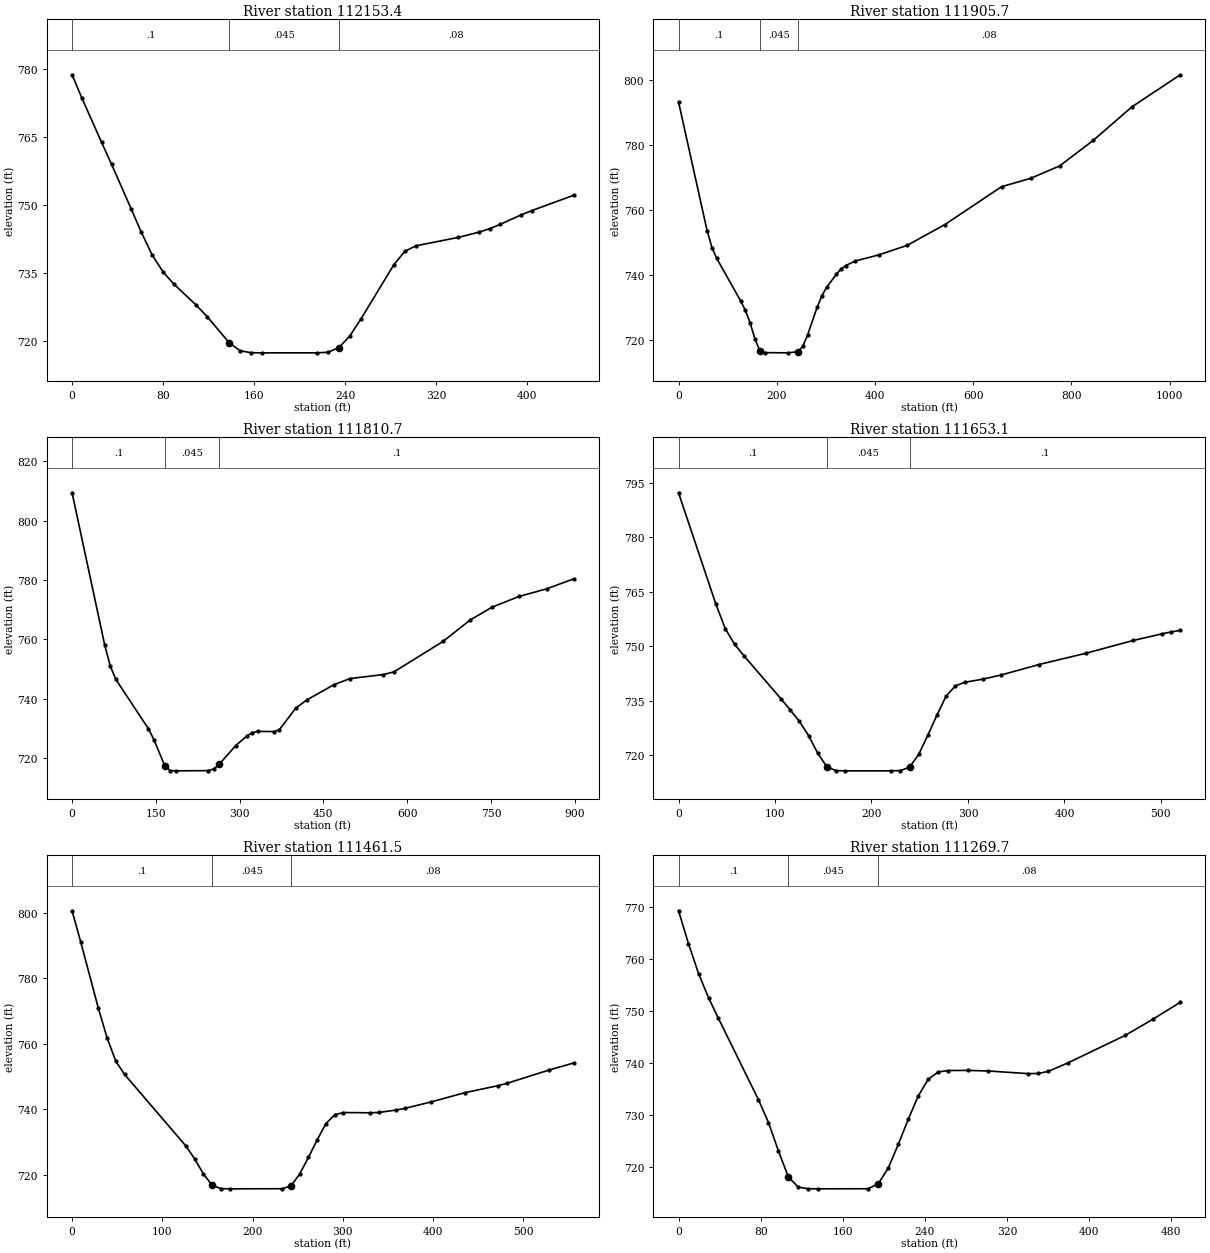
Type RM Length L Ch R = 1 ,112153.4,253.1,247.6,242.2
XS GIS Cut Line= 4
     1590965.768      311729.018     1591017.851      311697.768
     1591254.831      311614.435     1591377.226      311572.768
#Sta/Elev= 30
       0  778.75     8.7  773.58      26  763.84    34.7  759.04    52.1  749.14
    60.7  744.16    70.4  739.08    80.1  735.28    89.7   732.6     109  728.05
   118.7   725.5     138  719.77   147.7  717.96   157.4  717.53     167   717.5
   215.3   717.5     225  717.63   234.6  718.64   244.3  721.24     254  724.97
     283  736.94   292.6  739.87   302.3  741.07   339.6  742.93   358.1   744.1
   367.4  744.87   376.6  745.82   395.1  747.92   404.3  748.84   441.2  752.22
#Mann= 3 , 0 , 0
       0      .1       0     138    .045       0   234.6     .08       0
Bank Sta=138,234.6
XS Rating Curve= 0 ,0
Exp/Cntr=0.3,0.1

Type RM Length L Ch R = 1 ,111905.7,95.7,95,94.3
XS GIS Cut Line= 4
      1591089.24      311978.706     1591374.397      311792.508
     1591539.533      311521.834     1591843.812       311322.08
#Sta/Elev= 30
       0  793.28    58.4  753.42    68.1  748.37    77.8  745.03   126.5   731.9
   136.2  728.98     146     725   155.7  720.13   165.4  716.58   175.2  715.97
   223.8  715.91   243.3  716.29     253  717.96   262.7  721.39   282.2  729.95
   291.9  733.58   301.6  736.13   321.1   740.1   330.8  741.74   340.6  742.84
   359.8  744.22   407.8  746.12   465.5  749.06   542.3  755.47   657.6  767.15
   716.7  769.71   775.7  773.53   844.6  781.46   923.2  791.79  1021.6  801.66
#Mann= 3 , 0 , 0
       0      .1       0   165.4    .045       0   243.3     .08       0
Bank Sta=165.4,243.3
XS Rating Curve= 0 ,0
Exp/Cntr=0.3,0.1

Type RM Length L Ch R = 1 ,111810.7,159.6,157.6,155.6
XS GIS Cut Line= 2
     1591133.511      312071.154     1591869.854      311556.455
#Sta/Elev= 30
       0  809.36    58.6  757.93    68.4  751.02    78.1  746.58   136.7  729.87
   146.5  726.23     166  717.39   175.8  715.78   185.5   715.7   244.1  715.77
   253.9  716.36   263.7  717.96     293  724.21   312.5  727.38   322.2   728.5
     332     729   361.3  728.92   371.1  729.53   400.4   736.8   419.9  739.54
   468.7   744.7     498   746.8   556.6  748.11   576.2  749.02     664  759.27
   712.9  766.52   751.9  770.83   800.7  774.46   849.6     777   898.4  780.38
#Mann= 3 , 0 , 0
       0      .1       0     166    .045       0   263.7      .1       0
Bank Sta=166,263.7
XS Rating Curve= 0 ,0
Exp/Cntr=0.3,0.1

Type RM Length L Ch R = 1 ,111653.1,192.3,191.6,190.9
XS GIS Cut Line= 4
     1591266.324      312179.227     1591330.126      312134.956
      1591526.74      311969.591     1591686.897      311875.841
#Sta/Elev= 30
       0  792.25    38.8  761.51    48.5  754.81    58.2   750.5      68  747.31
   106.2  735.52   115.7   732.5   125.2  729.36   134.8   725.4   144.3  720.54
   153.8  716.78   163.3  715.76   172.8   715.7   220.4   715.7   229.9  715.77
   239.4   716.7   248.9   720.2   258.4  725.51     268  731.12   277.5  736.35
     287  739.09   296.5  740.06   315.5  740.95   334.6   742.1   373.6  744.97
   422.5  748.09   471.3  751.59   500.6  753.39   510.4  753.94   520.1  754.36
#Mann= 3 , 0 , 0
       0      .1       0   153.8    .045       0   239.4      .1       0
Bank Sta=153.8,239.4
XS Rating Curve= 0 ,0
Exp/Cntr=0.3,0.1

Type RM Length L Ch R = 1 ,111461.5,191.3,191.8,192.2
XS GIS Cut Line= 3
     1591409.553       312325.06     1591712.938      312052.924
     1591844.449      311983.914
#Sta/Elev= 30
       0   800.6     9.7  790.99    29.1  770.86    38.8  761.81    48.5  754.66
    58.2  750.62   126.2  728.77   135.8  724.88   145.6  720.23   155.3  716.77
     165  715.77   174.7   715.7   232.9  715.74   242.6   716.6   252.3  720.25
     262  725.32   271.7  730.71   281.4  735.64   291.1  738.32   300.8     739
   329.9  738.92   339.6  739.02     359  739.74   368.7  740.26   397.8  742.23
   435.4  745.06   472.5  747.23   481.8  747.91   528.2  751.94   556.1  754.15
#Mann= 3 , 0 , 0
       0      .1       0   155.3    .045       0   242.6     .08       0
Bank Sta=155.3,242.6
XS Rating Curve= 0 ,0
Exp/Cntr=0.3,0.1

Type RM Length L Ch R = 1 ,111269.7,265.7,263.5,261.5
XS GIS Cut Line= 3
     1591580.126      312424.018     1591882.209      312163.602
     1591938.199      312093.289
#Sta/Elev= 30
       0  769.23     9.7   762.9    19.5  757.13    29.2   752.5    38.9   748.5
    77.8  732.88    87.6  728.47    97.3  722.99     107  717.96   116.7  716.03
   126.5  715.71   136.2   715.7   184.8  715.72   194.6   716.7   204.3  719.71
     214  724.27   223.7  729.07   233.5  733.58   243.2   736.8   252.9   738.2
   262.6  738.48   282.1   738.5   301.6  738.39   340.5  737.88   350.2  737.91
   359.9   738.3   379.4  739.96   434.8  745.22   461.8  748.33   488.7  751.62
#Mann= 3 , 0 , 0
       0      .1       0     107    .045       0   194.6     .08       0
Bank Sta=107,194.6
XS Rating Curve= 0 ,0
Exp/Cntr=0.3,0.1

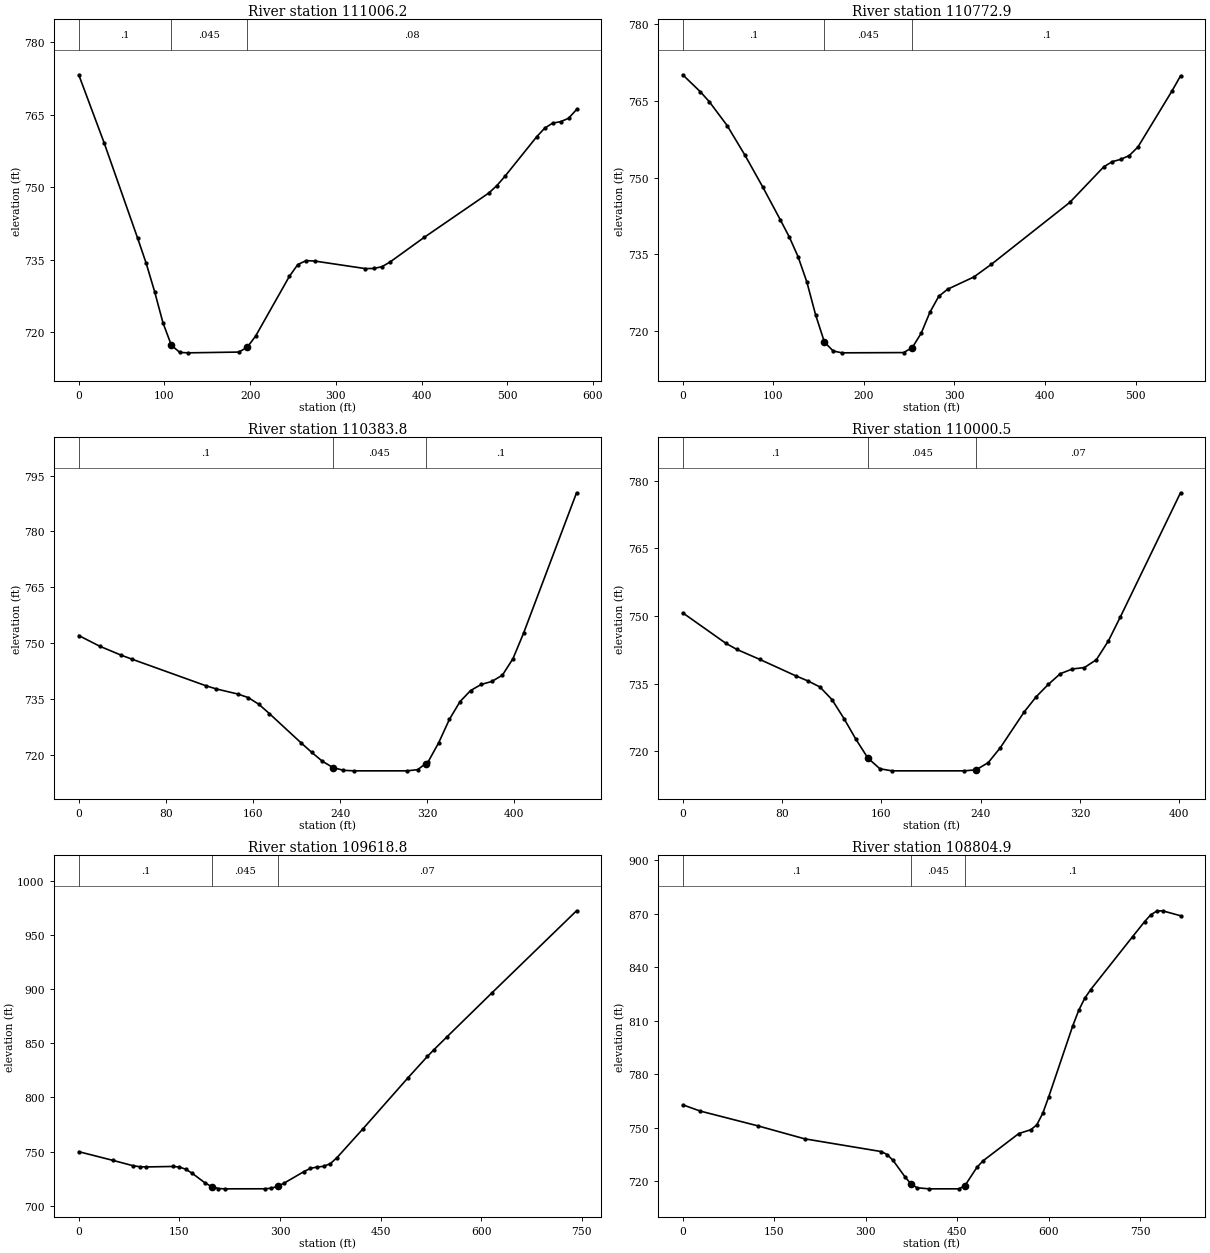
Type RM Length L Ch R = 1 ,111006.2,227.9,233.3,238.4
XS GIS Cut Line= 3
     1591791.063      312603.706     1592084.032      312299.018
     1592217.944      312214.962
#Sta/Elev= 30
       0  773.22    29.5   759.2    68.8  739.37    78.6  734.27    88.5  728.38
    98.3  721.89   108.1  717.26     118  715.78   127.8   715.7   186.8  715.86
   196.6  716.86   206.4  719.18   245.8  731.54   255.6  733.97   265.4  734.78
   275.2  734.69   334.2  733.13     344  733.15   353.9  733.52   363.7  734.55
     403  739.58   478.5  748.77   487.8  750.29   497.1  752.19   534.3   760.4
   543.6  762.17   552.9  763.22   562.2  763.52   571.5  764.22   580.8  766.04
#Mann= 3 , 0 , 0
       0      .1       0   108.1    .045       0   196.6     .08       0
Bank Sta=108.1,196.6
XS Rating Curve= 0 ,0
Exp/Cntr=0.3,0.1

Type RM Length L Ch R = 1 ,110772.9,376.4,389.1,402.1
XS GIS Cut Line= 4
     1591930.386      312763.862     1592002.001      312683.133
     1592244.188      312521.674     1592353.361      312418.087
#Sta/Elev= 30
       0  770.12    19.6  766.77    29.4  764.84      49  760.19    68.7  754.38
    88.3  748.17   107.9  741.68   117.6  738.39   127.3  734.53     137  729.58
   146.7  723.13   156.4  717.81   166.1  716.06   175.8   715.7   243.8  715.75
   253.4  716.72   263.2  719.53   272.9  723.65   282.6  726.75   292.3  728.14
   321.4  730.55   340.8  733.04   427.2  745.13   464.8  752.11   474.2  753.12
   483.6  753.57     493  754.32   502.5  755.99   540.1  766.96   549.5   769.9
#Mann= 3 , 0 , 0
       0      .1       0   156.4    .045       0   253.4      .1       0
Bank Sta=156.4,253.4
XS Rating Curve= 0 ,0
Exp/Cntr=0.3,0.1

Type RM Length L Ch R = 1 ,110383.8,373.6,383.3,392.9
XS GIS Cut Line= 2
     1592072.313      312924.018     1592529.345      312917.508
#Sta/Elev= 30
       0  752.04    19.4  749.15    38.9  746.77    48.6  745.72   116.7  738.56
   126.4  737.69   145.9  736.34   155.6  735.38   165.3  733.59     175  731.09
   204.2   723.2     214  720.65   223.7  718.27   233.4  716.58   243.1  715.84
   252.8   715.7   301.5   715.7   311.2  716.02   318.5717.6305   320.9  718.16
   330.6   723.3   340.4  729.56   350.1  734.29   359.8  737.26   369.6  738.91
   379.3   739.7     389  741.39   398.7  745.82   408.4  752.64   457.1  790.38
#Mann= 3 , 0 , 0
       0      .1       0   233.4    .045       0   318.5      .1       0
Bank Sta=233.4,318.5
XS Rating Curve= 0 ,0
Exp/Cntr=0.3,0.1

Type RM Length L Ch R = 1 ,110000.5,375.3,381.7,387.9
XS GIS Cut Line= 3
     1592031.949       313200.06     1592078.824      313223.497
     1592397.834      313364.122
#Sta/Elev= 27
       0   750.7    34.9  743.92    43.7  742.58    62.1  740.38    91.1  736.74
   100.8  735.62   110.5  734.28   120.2  731.49   129.9  727.28   139.6  722.65
   149.2  718.51   158.9  716.15   168.6   715.7   226.7   715.7   236.4  715.93
   246.1  717.52   255.8  720.81   275.1  728.76   284.8  732.13   294.5  734.85
   304.2  737.22   313.9  738.26   323.6  738.58   333.2  740.31   342.9  744.48
   352.6  749.83     401  777.29
#Mann= 3 , 0 , 0
       0      .1       0   149.2    .045       0   236.4     .07       0
Bank Sta=149.2,236.4
XS Rating Curve= 0 ,0
Exp/Cntr=0.3,0.1

Type RM Length L Ch R = 1 ,109618.8,794.2,814,833.7
XS GIS Cut Line= 4
     1591878.303      313460.477     1591906.949      313503.445
     1592163.459      313715.685     1592453.303      313924.886
#Sta/Elev= 30
       0  749.98    51.6  741.85      81  737.02    90.8  736.11   100.6   735.9
   139.8  736.34   149.6  735.87   159.4  733.83   169.2     730   188.7  720.96
   198.5  717.62   208.3  715.98   218.1   715.7   276.9  715.74   286.6  716.27
   296.4  717.92   306.2     721   335.6  731.58   345.4  734.62   355.2   735.8
     365  736.48   374.8  738.87   384.6  744.27   423.2  770.77   490.8  818.16
   519.8  837.92   529.5  844.09   548.8  855.88   616.4   896.8     742  972.19
#Mann= 3 , 0 , 0
       0      .1       0   198.5    .045       0   296.4     .07       0
Bank Sta=198.5,296.4
XS Rating Curve= 0 ,0
Exp/Cntr=0.3,0.1

Type RM Length L Ch R = 1 ,108804.9,479.7,496.4,513
XS GIS Cut Line= 3
     1591422.371       313490.28     1591345.751      313745.199
     1591346.532      314294.678
#Sta/Elev= 30
       0  762.86    28.5  759.36   123.6     751   199.6  743.78   325.1  736.63
   334.9  734.97   344.7  731.63   364.3   722.4     374718.4606   383.9  716.31
   403.6   715.7   452.6   715.7   462.4  717.48     482  727.73   491.9  731.36
   550.7  746.72   570.4  748.89   580.2   751.6     590  758.13   599.8  767.42
     639  807.07   648.9  815.88   658.7  822.61   668.5  827.51   737.2  857.23
   756.8  865.62   766.6  869.36   776.4  871.52   786.2  871.74   815.7  868.95
#Mann= 3 , 0 , 0
       0      .1       0     374    .045       0   462.4      .1       0
Bank Sta=374,462.4
XS Rating Curve= 0 ,0
Exp/Cntr=0.3,0.1

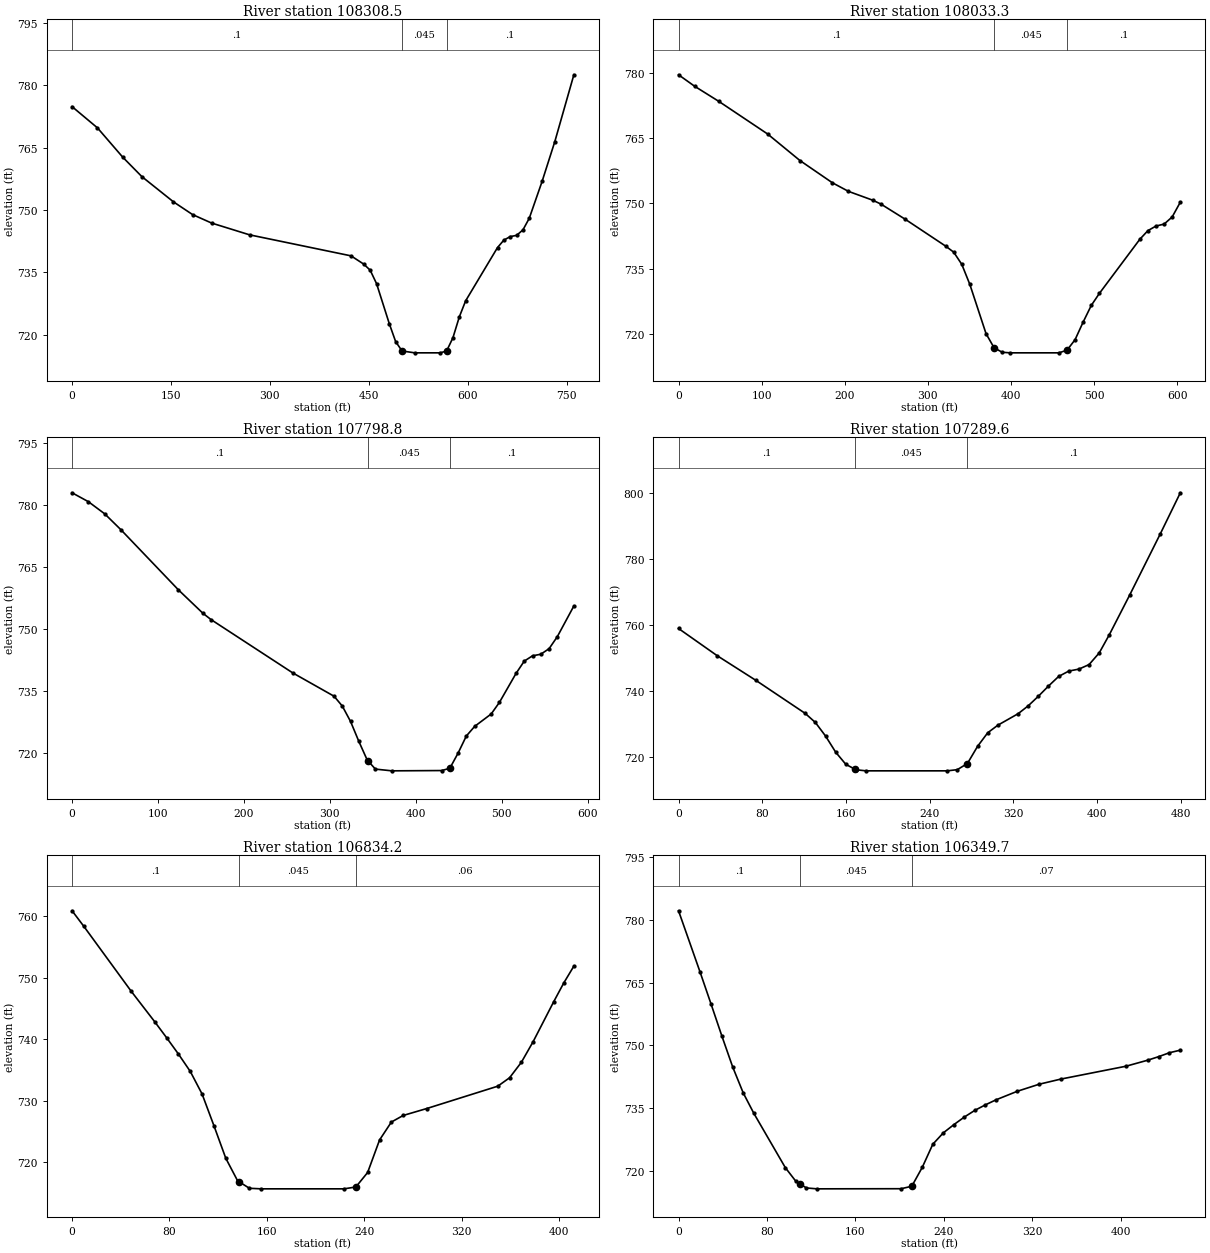
Type RM Length L Ch R = 1 ,108308.5,276.8,275.2,273.6
XS GIS Cut Line= 3
     1591346.416      313414.325     1590989.848      313623.671
     1590756.139      313880.905
#Sta/Elev= 30
       0  774.83    38.5  769.73    76.9  762.68   105.8  758.03   153.8  751.96
   182.7  748.91   211.6  746.87   269.2  744.04   423.1  738.99   442.4     737
   452.1  735.55   461.8  732.31   481.1   722.7   490.7  718.41   500.4  716.15
   519.7   715.7   558.3   715.7     568  716.14   577.6  719.32   587.3  724.34
   596.9   728.2   645.2  740.98   654.8  742.77   664.5  743.62   674.1  743.91
   683.8  745.23   693.4  748.03   712.8  756.86   732.1  766.42     761  782.48
#Mann= 3 , 0 , 0
       0      .1       0   500.4    .045       0     568      .1       0
Bank Sta=500.4,568
XS Rating Curve= 0 ,0
Exp/Cntr=0.3,0.1

Type RM Length L Ch R = 1 ,108033.3,235.5,234.5,233.6
XS GIS Cut Line= 2
      1590951.74      313211.952      1590578.39      313686.171
#Sta/Elev= 30
       0   779.5    19.5  776.85    48.7  773.37   107.1  765.92     146  759.83
     185  754.73   204.4  752.75   233.6  750.72   243.4  749.84   272.6  746.36
   321.2   740.2     331   738.8   340.7  736.01   350.4  731.41   369.9   720.1
   379.6  716.85   389.4  715.83   399.1   715.7   457.5   715.7   467.3  716.31
     477  718.72   486.7  722.76   496.5  726.58   506.2  729.33   554.9  741.76
   564.6  743.74   574.4   744.8   584.1  745.24   593.8  746.88   603.6  750.27
#Mann= 3 , 0 , 0
       0      .1       0   379.6    .045       0   467.3      .1       0
Bank Sta=379.6,467.3
XS Rating Curve= 0 ,0
Exp/Cntr=0.3,0.1

Type RM Length L Ch R = 1 ,107798.8,508.4,509.2,510
XS GIS Cut Line= 3
     1590579.345      313058.306     1590566.237      313314.643
     1590375.265      313580.268
#Sta/Elev= 30
       0     783      19  780.84      38   777.9      57  774.02   123.6  759.53
   152.1  753.86   161.6  752.32   256.7  739.41   304.8  733.76   314.4  731.38
     324  727.65   333.6  722.85   343.3  718.35   344.3718.1177   352.9  716.12
   372.1   715.7   429.9  715.77   439.5  716.32   449.1  719.99   458.7  724.13
   468.4  726.46   487.6  729.46   497.2  732.27   516.5  739.27   526.1  742.26
   535.7  743.54   545.3  743.92     555  745.27   564.6  748.19   583.8   755.6
#Mann= 3 , 0 , 0
       0      .1       0   344.3    .045       0   439.5      .1       0
Bank Sta=344.3,439.5
XS Rating Curve= 0 ,0
Exp/Cntr=0.3,0.1

Type RM Length L Ch R = 1 ,107289.6,456.1,455.3,454.9
XS GIS Cut Line= 3
     1590166.931      312977.838     1590123.529      313069.852
     1589892.423      313368.752
#Sta/Elev= 30
       0  758.86      37   750.6      74  743.12   121.1  733.11   130.8  730.36
   140.5  726.26   150.2  721.36   159.9  717.67   168.2716.2667   169.6  716.03
   179.2   715.7   256.7   715.7   266.4  716.05   276.1  717.92   285.8  723.12
   295.5  727.24   305.2  729.54   324.6  733.03   334.2  735.41   343.9  738.31
   353.6  741.41   363.3  744.32     373  745.95   382.7  746.55   392.4  747.92
   402.1  751.46   411.8  757.01   431.1  768.94   460.2  787.39   479.6  800.01
#Mann= 3 , 0 , 0
       0      .1       0   168.2    .045       0   276.1      .1       0
Bank Sta=168.2,276.1
XS Rating Curve= 0 ,0
Exp/Cntr=0.3,0.1

Type RM Length L Ch R = 1 ,106834.2,488.2,484.5,480.5
XS GIS Cut Line= 3
     1589772.834      312776.449     1589548.876      313082.004
     1589533.251      313111.518
#Sta/Elev= 28
       0  760.91     9.7  758.37    48.6  747.82      68  742.84    77.7  740.26
    87.4  737.61    97.1  734.79   106.8  731.12   116.6  725.93   126.3  720.66
     136     717   137.3716.8378   145.7  715.79   155.4   715.7   223.4   715.7
   233.1     716   242.8  718.36   252.6  723.65   262.3  726.56     272  727.63
   291.4  728.76   349.7  732.39   359.4  733.76   369.1  736.28   378.8  739.65
   395.5  746.07   403.9  749.17   412.2  751.91
#Mann= 3 , 0 , 0
       0      .1       0   137.3    .045       0   233.1     .06       0
Bank Sta=137.3,233.1
XS Rating Curve= 0 ,0
Exp/Cntr=0.3,0.1

Type RM Length L Ch R = 1 ,106349.7,487.6,472.3,456.5
XS GIS Cut Line= 4
     1589278.042      312604.574     1589258.945      312649.713
      1589149.57      312871.935     1589132.209      313028.185
#Sta/Elev= 30
       0  782.23    19.6  767.48    29.4  759.93    39.2  752.26      49  744.85
    58.5  738.66    68.1  733.77    96.6  720.77   106.2  717.48   110.3716.8024
   115.7  715.91   125.2   715.7   201.4  715.73     211  716.32   220.5  720.86
     230  726.37   239.5  729.09   249.1  731.07   258.6  732.89   268.1  734.49
   277.6   735.8   287.2     737   306.5  739.05   326.2  740.73   345.8  741.96
   404.8  745.04   424.4  746.48   434.2  747.32   444.1  748.27   453.9  748.88
#Mann= 3 , 0 , 0
       0      .1       0   110.3    .045       0     211     .07       0
Bank Sta=110.3,211
XS Rating Curve= 0 ,0
Exp/Cntr=0.3,0.1

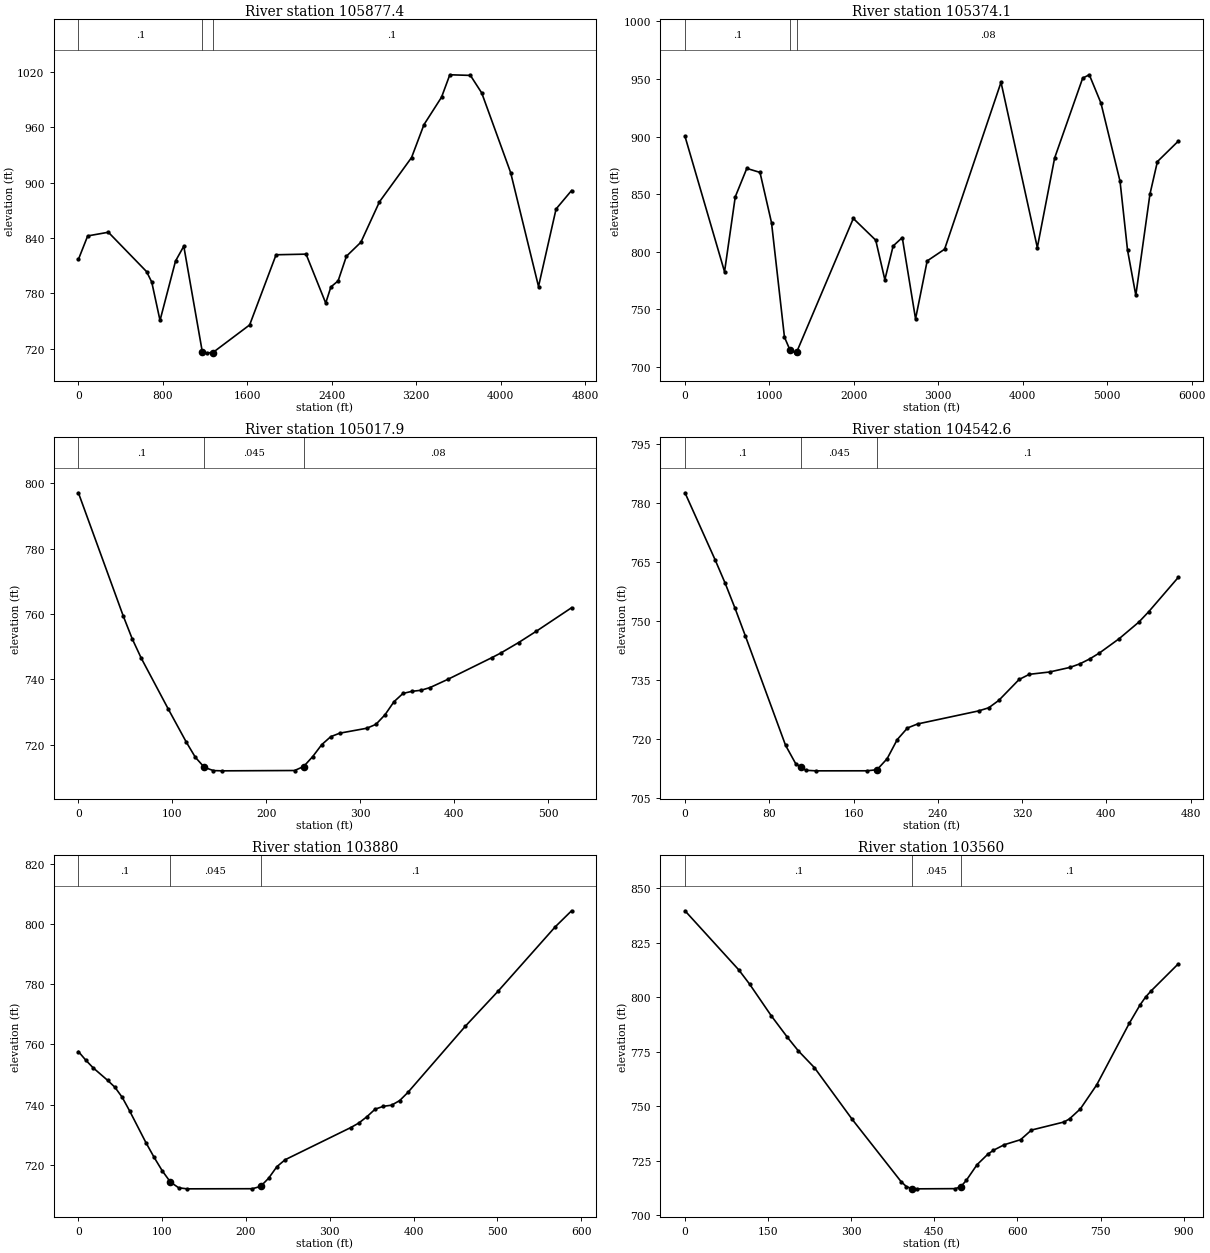
Type RM Length L Ch R = 1 ,105877.4,505.1,503.4,501.7
XS GIS Cut Line= 6
     1588461.289       311539.47      1588797.14      312998.671
     1588944.709      313278.185     1589340.083      314956.078
     1589494.055      315238.418     1590136.416      315734.946
#Sta/Elev= 30
       0  816.77    88.1  842.26   283.8  846.25   645.9  803.61   694.8  792.29
   773.1  750.79   919.9  815.06   998.2  831.16  1174.4  716.28  1213.5   715.7
  1272.3   715.9  1621.9  745.91  1872.2  821.87  2156.2  822.55  2342.3  769.59
  2391.3  787.02  2459.9  793.61  2538.2  820.25  2675.4  835.41  2851.6  879.23
  3155.3  927.08  3272.8  962.72  3439.3  992.46  3517.7 1016.71  3712.7 1016.04
  3819.9  997.03  4093.6  910.87  4357.7  787.51    4524  871.42  4670.8  891.42
#Mann= 3 , 0 , 0
       0      .1       0  1174.4    .045       0  1272.3      .1       0
Bank Sta=1174.4,1272.3
XS Rating Curve= 0 ,0
Exp/Cntr=0.3,0.1

Type RM Length L Ch R = 1 ,105374.1,355.8,356.1,356.5
XS GIS Cut Line= 6
     1587836.289      311647.977     1588319.709      313073.324
     1588283.251      313476.102      1587820.47      315244.446
       1588145.2      316217.516     1589160.825      316561.266
#Sta/Elev= 30
       0  900.15   468.5  782.47   595.4  847.58     732  872.28   888.2  868.81
  1024.9  825.04    1178  725.65  1244.8714.2306  1311.8     712  1324.6     713
  1993.5  828.78  2258.9  809.92    2367  775.54  2465.2  804.87  2573.3  812.18
  2730.6  741.51  2868.2  791.88  3074.5  802.05  3742.8  947.14  4172.7   803.5
  4377.8  881.37    4710  950.76  4788.3  953.65    4926  929.12  5152.3  861.09
  5240.8  801.38  5339.2  762.01  5506.4  849.89  5594.9   878.2  5840.8  895.89
#Mann= 3 , 0 , 0
       0      .1       0  1244.8    .045       0  1324.6     .08       0
Bank Sta=1244.8,1324.6
XS Rating Curve= 0 ,0
Exp/Cntr=0.3,0.1

Type RM Length L Ch R = 1 ,105017.9,477.3,475.3,473.3
XS GIS Cut Line= 4
     1587873.529      312743.463     1587871.792      312819.852
     1587958.598       313114.99     1587969.015      313255.615
#Sta/Elev= 30
       0  797.11    47.8  759.37    57.3  752.42    66.9   746.5    95.6  730.97
   114.9  720.79   124.5  716.16   134.1  713.07   143.7  712.08   153.3     712
   230.2   712.1   239.8  713.32   249.5  716.37   259.1  720.02   268.7  722.46
   278.3  723.53   307.1  725.04   316.8  726.23   326.4  729.14     336  733.15
   345.6  735.69   355.2  736.34   364.8  736.66   374.4  737.49   393.4  740.01
   440.4  746.67   449.8  748.07   468.6  751.25   487.5  754.72   525.1  761.93
#Mann= 3 , 0 , 0
       0      .1       0   134.1    .045       0   239.8     .08       0
Bank Sta=134.1,239.8
XS Rating Curve= 0 ,0
Exp/Cntr=0.3,0.1

Type RM Length L Ch R = 1 ,104542.6,664.1,662.6,661.1
XS GIS Cut Line= 4
     1587383.945      312934.435      1587422.14      313000.407
     1587528.042      313269.504     1587548.876      313370.199
#Sta/Elev= 30
       0  782.58    28.6  765.57    38.1  759.65    47.6  753.21    57.2  746.33
    95.5  718.47   105.2  713.77   110.6712.8531   114.8  712.14   124.4     712
   172.6  712.01   182.3  712.28   191.9  715.08   201.5  719.93   211.2  722.88
   220.8   723.9   278.7  727.21   288.3     728   297.9  729.88   317.2  735.19
   326.9   736.5   346.1  737.09   365.4  738.25   374.8  739.15   384.1  740.39
   393.5  741.92   412.2  745.55   430.8  749.74   440.2  752.38   468.2  761.08
#Mann= 3 , 0 , 0
       0      .1       0   110.6    .045       0   182.3      .1       0
Bank Sta=110.6,182.3
XS Rating Curve= 0 ,0
Exp/Cntr=0.3,0.1

Type RM Length L Ch R = 1 ,103880  ,320.2,320,319.7
XS GIS Cut Line= 3
      1586797.14      313167.074     1586791.931      313227.838
     1587016.808      313704.943
#Sta/Elev= 30
       0  757.61     8.7  754.79    17.4  752.26    34.8  748.07    43.6  745.75
    52.3   742.4      61  737.96    80.5  727.39    90.3  722.49   100.1  717.97
   109.8  714.25   119.6  712.36   129.4     712   207.5  712.04   217.3   712.8
     227  715.54   236.8  719.36   246.6  721.66   324.7  732.32   334.5  733.85
   344.2  735.96     354  738.47   363.8  739.41   373.6  739.79   383.3  741.32
   393.1  744.03   461.4  765.95   500.5   777.6   568.9  799.05   588.4  804.38
#Mann= 3 , 0 , 0
       0      .1       0   109.8    .045       0   217.3      .1       0
Bank Sta=109.8,217.3
XS Rating Curve= 0 ,0
Exp/Cntr=0.3,0.1

Type RM Length L Ch R = 1 ,103560  ,284.4,283.4,282.5
XS GIS Cut Line= 3
     1586508.996       313036.54      1586493.32      313347.629
     1586745.056      313868.463
#Sta/Elev= 30
       0  839.64    97.3  812.45   116.8   805.9   155.7  791.44   184.9  781.55
   204.4  775.38   233.6  767.63   301.8  743.88   389.9  715.34   399.7     713
   409.5  712.09   419.3     712     488  712.09   497.8  713.01   507.6  715.88
   527.2  723.13   546.8  727.96   556.6   729.7   576.2  732.25   605.6  734.56
   625.2  738.98   684.1  742.69   693.9  744.12   713.5  748.71   742.9  759.69
   801.7  787.96   821.3  796.46   831.1  800.01   840.9  802.79     890  815.23
#Mann= 3 , 0 , 0
       0      .1       0   409.5    .045       0   497.8      .1       0
Bank Sta=409.5,497.8
XS Rating Curve= 0 ,0
Exp/Cntr=0.3,0.1