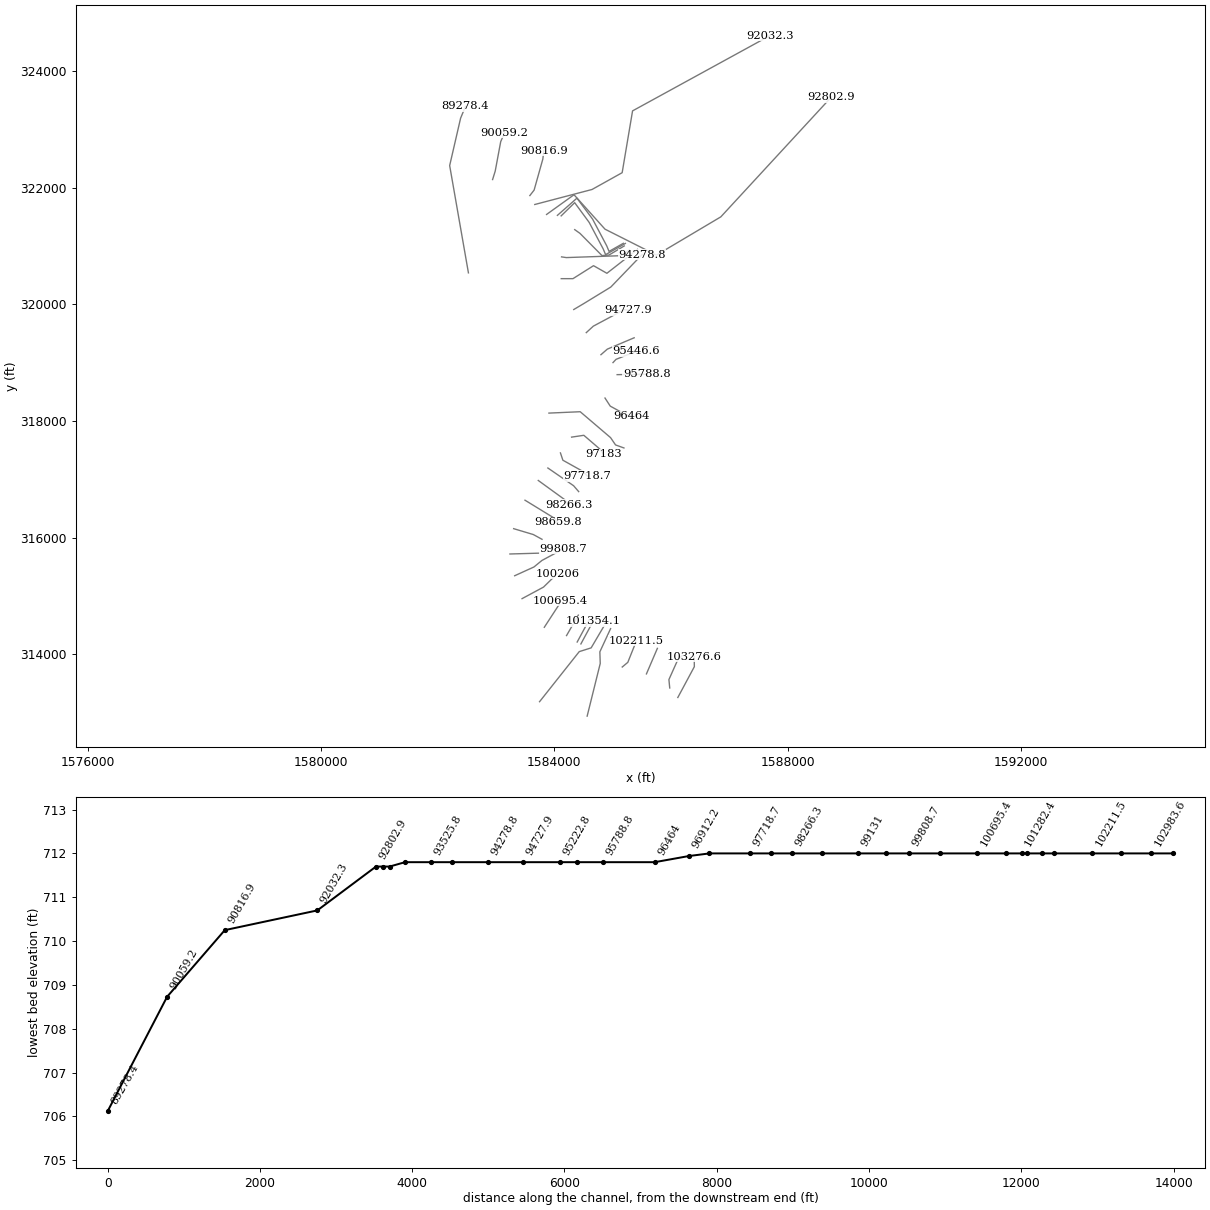
HEC-RAS study MDISLCRK_C.prj: MDISLCRK_C

--- MDISLCRK_C.g01 (geometry) --- (continued)

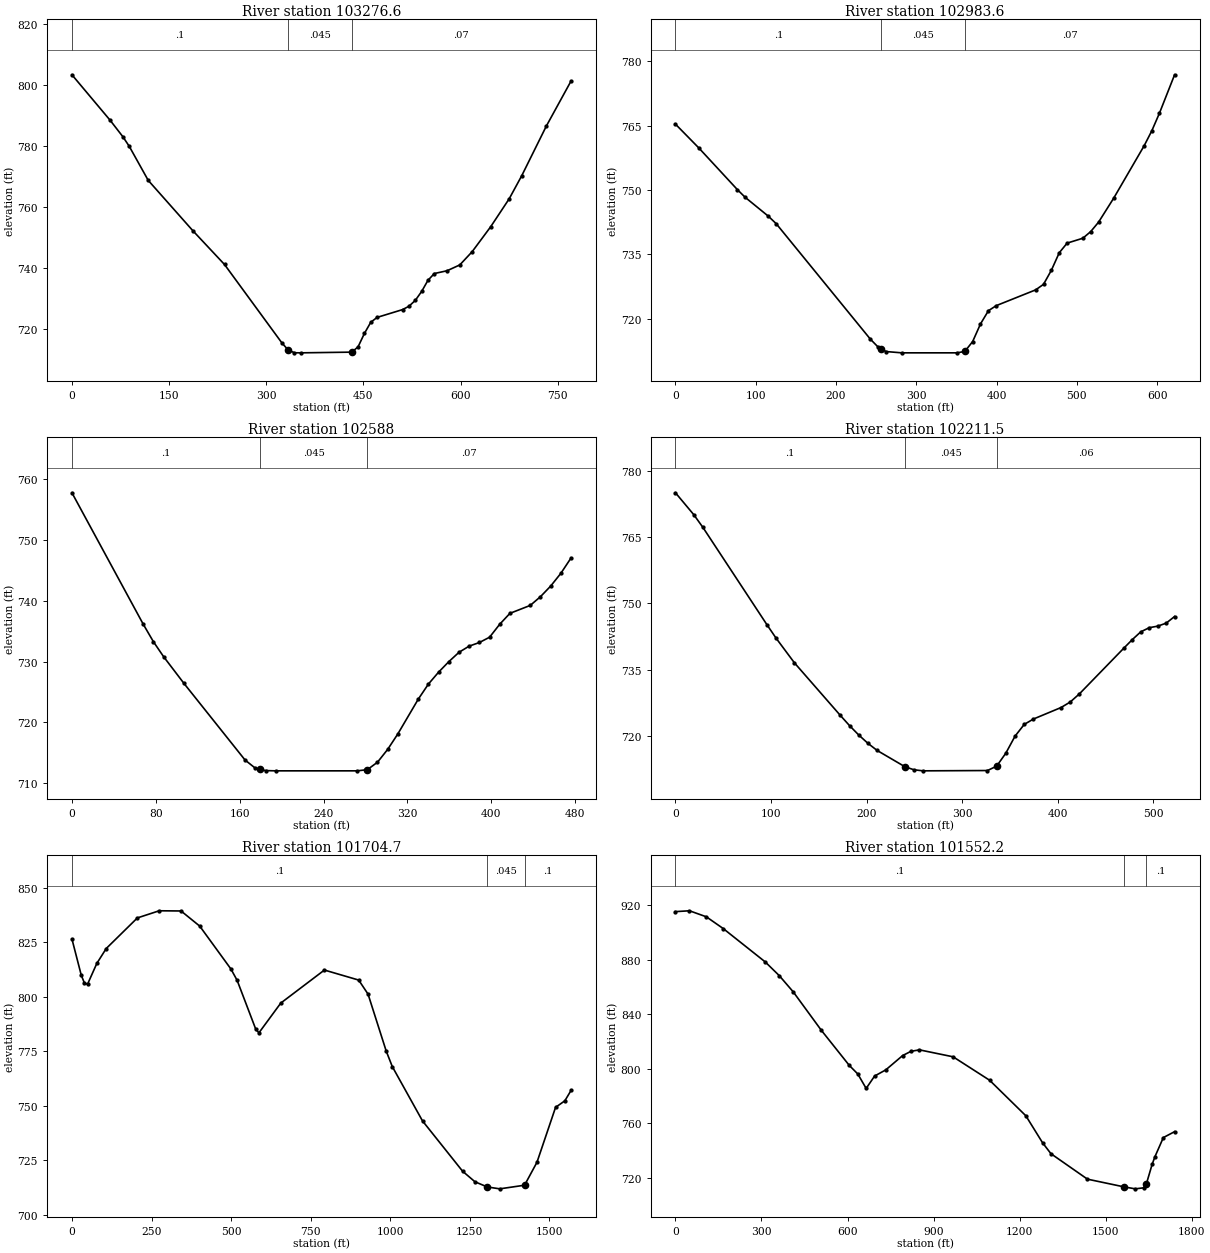
Type RM Length L Ch R = 1 ,103276.6,291.4,293,294.6
XS GIS Cut Line= 3
      1586118.32      313260.824     1586401.306      313788.602
      1586399.57      313960.477
#Sta/Elev= 30
       0   803.4    58.9  788.47    78.5  783.08    88.4  779.92   117.8  768.69
   186.5  752.19   235.6  741.04     324  715.32   333.8  712.95   343.6  712.02
   353.4     712     432  712.23   441.8  713.96   451.6  718.37   461.4  722.04
   471.2  723.65   510.5  726.21   520.3   727.3   530.1  729.22     540  732.18
   549.8  735.86   559.6  738.07   579.2  738.98   598.9   740.9     618  745.25
   646.6  753.45   675.2  762.65   694.4  770.16   732.6  786.57   770.7  801.35
#Mann= 3 , 0 , 0
       0      .1       0   333.8    .045       0     432     .07       0
Bank Sta=333.8,432
XS Rating Curve= 0 ,0
Exp/Cntr=0.3,0.1

Type RM Length L Ch R = 1 ,102983.6,395.2,395.6,395.9
XS GIS Cut Line= 4
     1585979.431      313424.018     1585965.542      313568.115
     1586121.792      313917.074     1586192.973      313979.574
#Sta/Elev= 30
       0  765.32      29  759.79    77.2  750.04    86.9  748.25   115.8  743.84
   125.5  742.11   242.8  715.19   252.6  713.32   256.5712.9141   262.4   712.3
     282     712   350.6     712   360.4  712.32   370.2  714.62     380  718.74
   389.9  721.83   399.7  723.01   448.7  726.68   458.5  727.97   468.3  731.25
   478.1  735.33   487.9  737.58   507.5  738.72   517.3  740.27   527.1  742.47
     546  748.08   583.9  760.29   593.4  763.76   602.9  767.86   621.8  776.83
#Mann= 3 , 0 , 0
       0      .1       0   256.5    .045       0   360.4     .07       0
Bank Sta=256.5,360.4
XS Rating Curve= 0 ,0
Exp/Cntr=0.3,0.1

Type RM Length L Ch R = 1 ,102588  ,375.9,376.5,377
XS GIS Cut Line= 2
     1585580.126      313665.338     1585767.626      314102.838
#Sta/Elev= 30
       0   757.8      68  736.15    77.7  733.27    87.4  730.81   106.8  726.41
   165.1  713.78   174.8  712.45   179.6712.2492   184.6  712.04   194.3     712
     272     712   281.7  712.19   291.4  713.42   301.1  715.53   310.8  718.08
   330.3  723.81     340   726.3   349.7  728.26   359.4  729.98   369.1  731.52
   378.8  732.54   388.6  733.14   398.3  734.01     408  736.15   417.7  737.94
   437.1  739.25   446.8  740.68   456.6  742.44   466.3  744.54     476  747.07
#Mann= 3 , 0 , 0
       0      .1       0   179.6    .045       0   281.7     .07       0
Bank Sta=179.6,281.7
XS Rating Curve= 0 ,0
Exp/Cntr=0.3,0.1

Type RM Length L Ch R = 1 ,102211.5,506.5,506.9,507.8
XS GIS Cut Line= 4
     1585165.195      313783.393     1585260.681      313863.254
     1585382.209      314167.074     1585396.098      314236.518
#Sta/Elev= 30
       0  775.13    19.2  770.15    28.7  767.28    95.8  745.16   105.3  742.13
   124.5  736.53   172.6  724.58   182.2  722.27   191.8  720.15   201.5  718.24
   211.1  716.63     240  712.96   249.6  712.24   259.2     712   326.6  712.07
   336.2  713.06   345.8     716   355.5  719.88   365.1  722.54   374.7  723.76
   403.6  726.37   413.2  727.62   422.8  729.46   469.4  739.86   478.3  741.81
   487.1  743.56     496   744.5   504.8  744.85   513.7  745.53   522.5  747.04
#Mann= 3 , 0 , 0
       0      .1       0     240    .045       0   336.2     .06       0
Bank Sta=240,336.2
XS Rating Curve= 0 ,0
Exp/Cntr=0.3,0.1

Type RM Length L Ch R = 1 ,101704.7,156.2,152.4,148.1
XS GIS Cut Line= 4
      1584563.72      312941.379     1584788.004      313844.252
     1584781.515       314043.81     1584965.542      314441.379
#Sta/Elev= 30
       0  826.49    29.4  809.84    39.2  806.31      49  805.75    78.3  815.32
   107.7  822.11   205.6  836.14   274.2  839.41   342.8  839.32   401.5  832.38
   499.4  812.75     519  807.54   577.8  785.04   587.6  783.51   656.1  797.11
   793.2  812.25   900.9  807.66   930.3  801.22   987.4  775.11  1006.4  768.04
  1101.4  743.12  1227.3  720.08  1266.3  715.22  1305.2  712.85  1344.2     712
    1422  713.66    1461  724.18  1519.4  749.33  1548.6  752.34  1568.1   757.1
#Mann= 3 , 0 , 0
       0      .1       0  1305.2    .045       0    1422      .1       0
Bank Sta=1305.2,1422
XS Rating Curve= 0 ,0
Exp/Cntr=0.3,0.1

Type RM Length L Ch R = 1 ,101552.2,197.3,198.2,198.9
XS GIS Cut Line= 4
     1583747.747      313188.775     1584428.094       314047.23
     1584632.209      314111.518     1584850.959      314483.046
#Sta/Elev= 30
       0  915.18    48.9   915.8   107.6  911.39   166.3   902.8     313  878.32
   361.9  868.27   410.8  856.34   508.6  828.21   606.4   802.4   635.7  796.21
     665  785.59   694.4  794.67   733.5   799.2   792.2  809.69   821.5  812.81
   850.9  813.86   968.2  808.77  1095.4   791.6  1221.8  765.55  1280.2  745.74
  1309.4  737.74  1436.7  719.09  1564.1  713.44  1603.3     712  1632.7  712.75
  1642.5  715.89  1662.1  729.88  1671.9  735.52  1701.3  749.58  1740.5   753.9
#Mann= 3 , 0 , 0
       0      .1       0  1564.1    .045       0  1642.5      .1       0
Bank Sta=1564.1,1642.5
XS Rating Curve= 0 ,0
Exp/Cntr=0.3,0.1

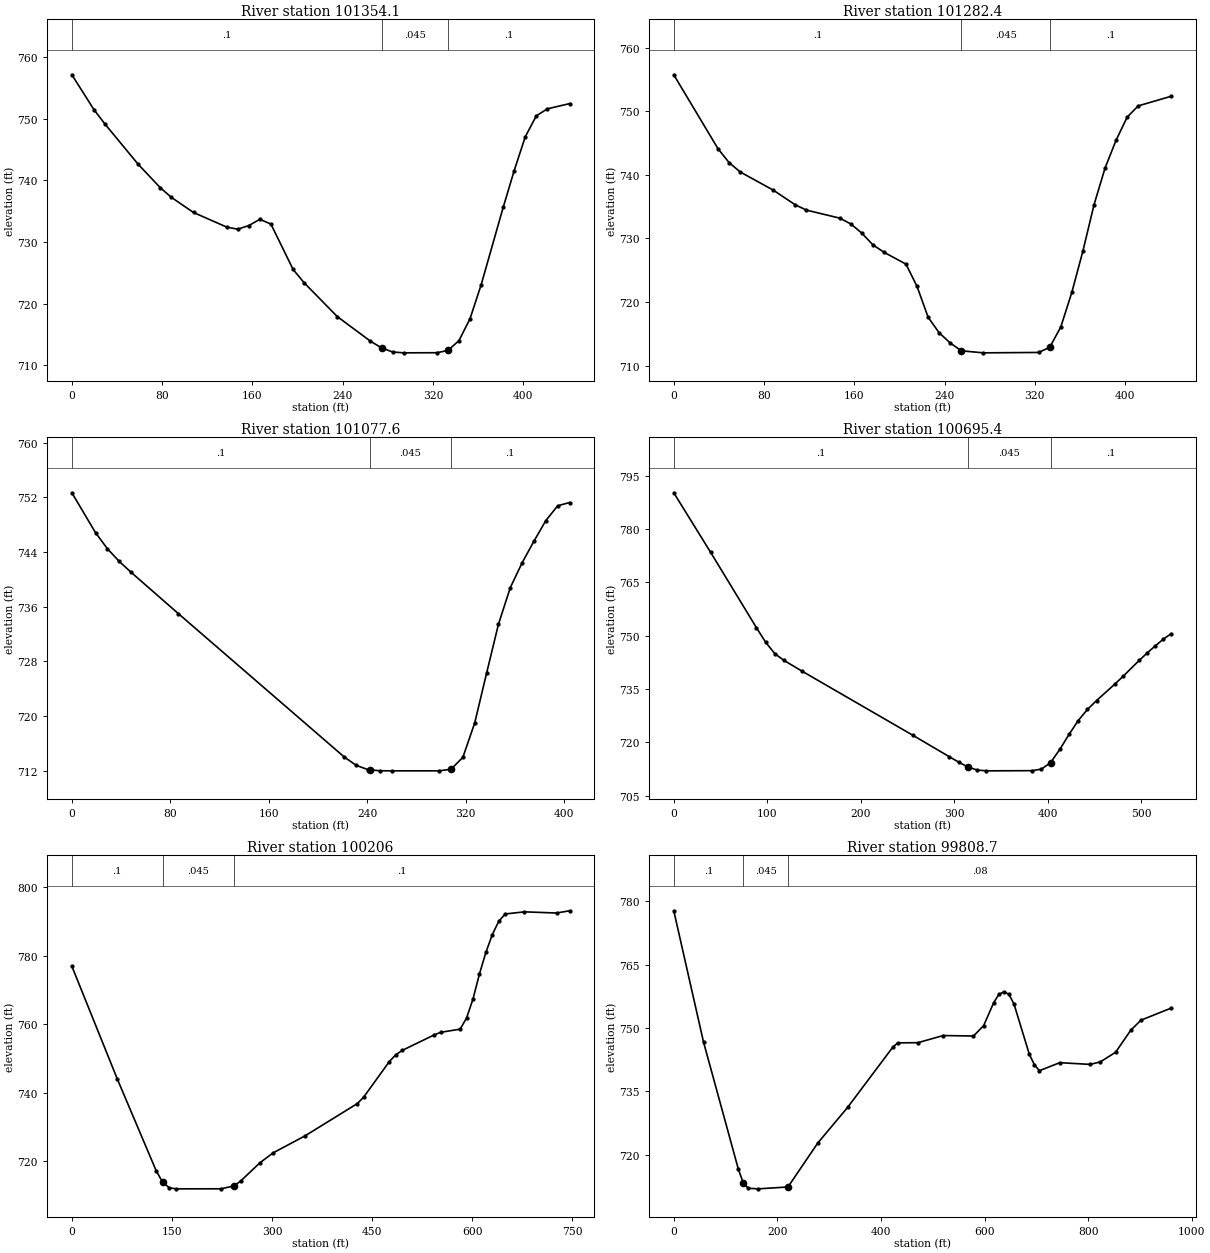
Type RM Length L Ch R = 1 ,101354.1,71.7,71.7,71.7
XS GIS Cut Line= 2
     1584456.428      314179.227     1584666.063      314567.247
#Sta/Elev= 30
       0  757.09    19.6  751.43    29.4  749.09    58.8  742.57    78.4  738.77
    88.2  737.21   107.8  734.76   137.2  732.39     147  732.05   156.8  732.64
   166.6  733.65   176.4  732.88     196  725.54   205.8  723.37   235.2  717.88
   264.6  713.89   274.4  712.81   284.2  712.14     294     712   323.4  712.02
   333.2  712.38     343  713.97   352.8  717.52   362.6  722.97   382.2  735.57
     392  741.56   401.8  747.04   411.6  750.43   421.4  751.57     441  752.41
#Mann= 3 , 0 , 0
       0      .1       0   274.4    .045       0   333.2      .1       0
Bank Sta=274.4,333.2
XS Rating Curve= 0 ,0
Exp/Cntr=0.3,0.1

Type RM Length L Ch R = 1 ,101282.4,205.5,204.8,204.3
XS GIS Cut Line= 2
     1584392.626      314211.779     1584602.261      314599.799
#Sta/Elev= 30
       0  755.74    39.2  744.11      49  741.93    58.8  740.46    88.2  737.59
   107.8  735.27   117.6  734.45     147  733.19   156.8  732.29   166.6  730.84
   176.4     729   186.2  727.83   205.8  725.95   215.6  722.44   225.4   717.6
   235.2  715.15     245  713.55   254.8  712.32   274.4     712   323.4  712.06
   333.2712.8826     343  716.08   352.8  721.54   362.6  728.04   372.4  735.28
   382.2  741.07     392  745.46   401.8  749.08   411.6  750.85     441  752.37
#Mann= 3 , 0 , 0
       0      .1       0   254.8    .045       0   333.2      .1       0
Bank Sta=254.8,333.2
XS Rating Curve= 0 ,0
Exp/Cntr=0.3,0.1

Type RM Length L Ch R = 1 ,101077.6,383.3,382.2,380.9
XS GIS Cut Line= 2
     1584210.334      314322.456     1584412.157      314672.716
#Sta/Elev= 24
       0  752.67    19.2  746.84    28.9  744.48    38.5  742.63    48.1  741.04
    86.6  734.98   221.4     714     231   712.8   240.6  712.17   241.8  712.15
   250.2  712.01   259.9     712   298.4     712     308  712.24   317.6  713.98
   327.2     719   336.9  726.32   346.5  733.45   356.1  738.79   365.8  742.46
   375.4  745.62     385  748.61   394.6  750.77   404.2  751.24
#Mann= 3 , 0 , 0
       0      .1       0   241.8    .045       0     308      .1       0
Bank Sta=241.8,308
XS Rating Curve= 0 ,0
Exp/Cntr=0.3,0.1

Type RM Length L Ch R = 1 ,100695.4,500.6,489.4,478
XS GIS Cut Line= 3
     1583829.005      314464.491     1584086.636      314860.216
     1584105.733      314917.508
#Sta/Elev= 28
       0  790.18    39.4  773.46    88.5  752.24    98.4  748.13   108.2  744.93
     118  743.04   137.7  739.96   255.8  722.01   295.1  715.94     305  714.44
   314.8  713.09   324.6  712.23   334.5     712   383.7  712.05   393.5  712.49
   403.3  714.31   413.2  718.05     423  722.22   432.8  726.12   442.7  729.26
   452.5  731.77   472.2  736.42   480.8  738.56   498.1  743.04   506.7  745.15
   515.3  747.13     524  749.03   532.6   750.6
#Mann= 3 , 0 , 0
       0      .1       0   314.8    .045       0   403.3      .1       0
Bank Sta=314.8,403.3
XS Rating Curve= 0 ,0
Exp/Cntr=0.3,0.1

Type RM Length L Ch R = 1 ,100206  ,398.8,397.3,395.8
XS GIS Cut Line= 3
     1583447.747      314955.702     1583815.803      315153.619
     1584050.178      315382.786
#Sta/Elev= 30
       0  776.93      68  744.08   126.3   717.3   136.1   713.9   145.8  712.36
   155.5     712   223.5  712.01     243  712.85   252.7  714.23   281.8   719.6
   301.3  722.46   349.9  727.51   427.5  736.84   437.2  738.73   475.7  749.12
   485.4  751.11     495  752.38   543.2  756.93   552.9  757.67   581.8  758.58
   591.4   761.8   601.1  767.38   610.7  774.64   620.4  780.97     630  786.15
   639.6  790.01   649.3  792.18   678.2   792.8   726.4  792.46   745.7  793.11
#Mann= 3 , 0 , 0
       0      .1       0   136.1    .045       0     243      .1       0
Bank Sta=136.1,243
XS Rating Curve= 0 ,0
Exp/Cntr=0.3,0.1

Type RM Length L Ch R = 1 ,99808.7 ,311.2,302.2,293.1
XS GIS Cut Line= 4
     1583321.011      315348.063     1583652.608      315499.105
     1583788.025      315610.216       1584159.3      315809.399
#Sta/Elev= 30
       0   777.7    57.5  746.66   124.7  716.65   134.2   713.4   143.8  712.13
     163     712   220.5  712.44   278.1  722.83   335.6  731.23   422.8  745.45
   432.5  746.49   471.4  746.53   520.1  748.22   578.7  748.11   598.3  750.55
   617.9  756.02   627.7  757.93   637.5  758.56   647.3  757.95   657.1  755.61
   686.5  743.81   696.3  741.32   706.1  739.92   745.3  741.81   804.1   741.4
   823.7     742   853.1  744.27   882.5  749.49   902.1  751.85   960.9  754.73
#Mann= 3 , 0 , 0
       0      .1       0   134.2    .045       0   220.5     .08       0
Bank Sta=134.2,220.5
XS Rating Curve= 0 ,0
Exp/Cntr=0.3,0.1

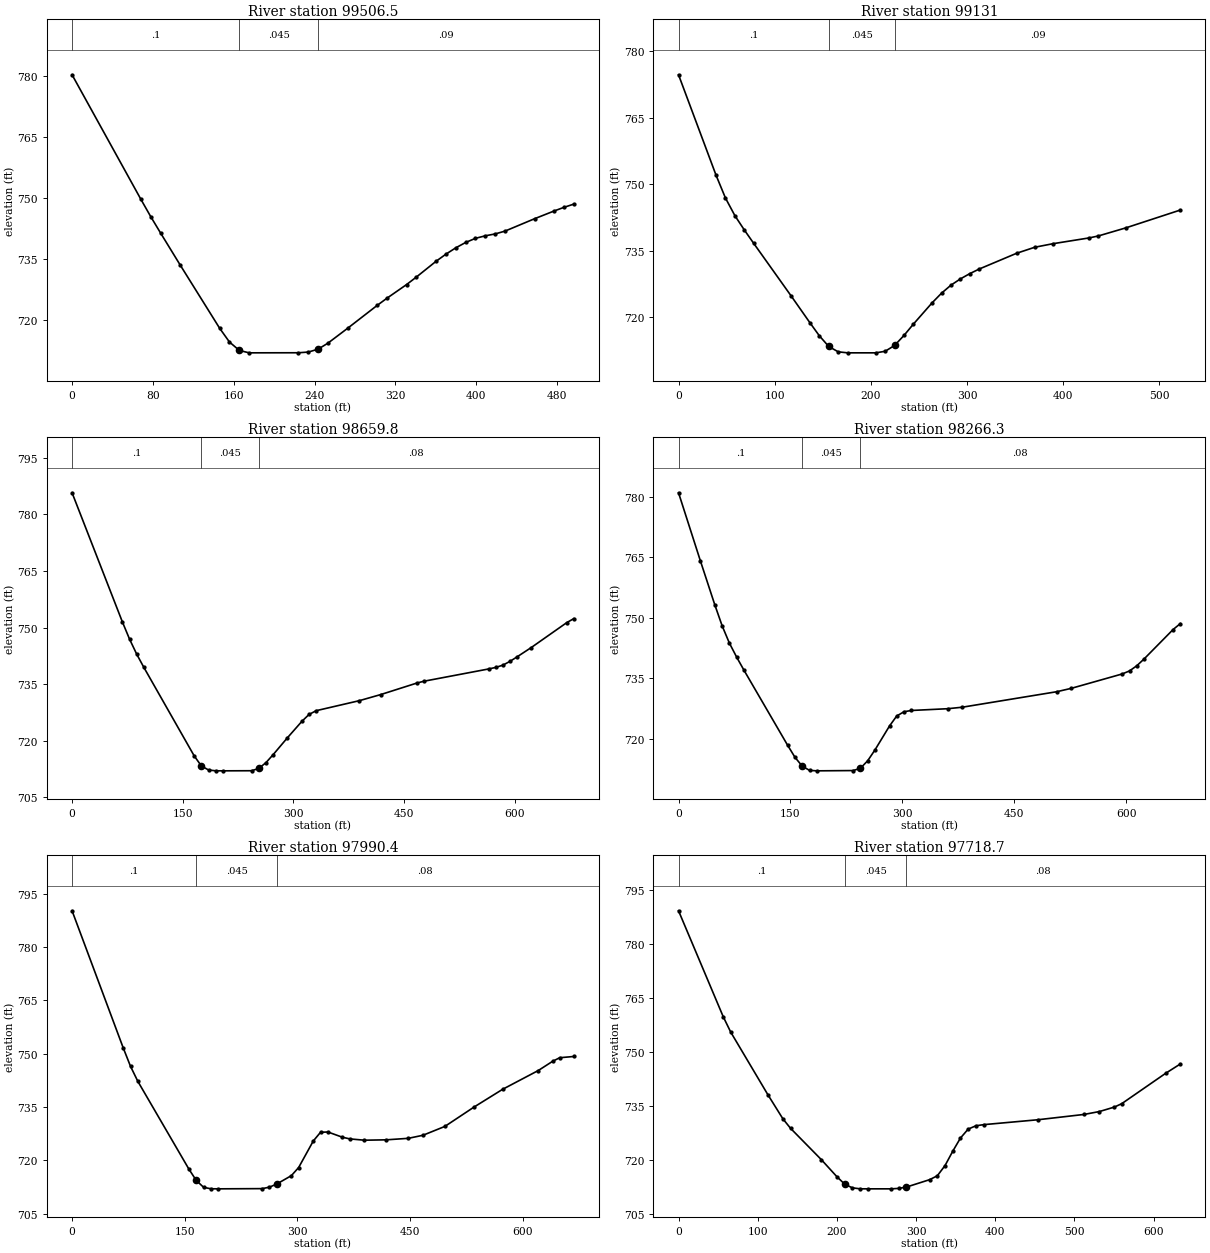
Type RM Length L Ch R = 1 ,99506.5 ,382.7,375.5,368.3
XS GIS Cut Line= 2
     1583239.414      315721.327     1583735.942      315735.216
#Sta/Elev= 30
       0   780.4    68.2  749.73    77.9  745.49    87.7  741.44   107.1  733.57
   146.1  718.04   155.8  714.66   165.6  712.59   175.3     712     224  712.02
   233.8  712.19   243.5   712.9   253.2  714.37   272.7  718.03   301.9  723.65
   311.7  725.44   331.2  728.81   340.9  730.66   360.4  734.54   370.1  736.28
   379.8  737.83   389.6  739.15   399.3  740.17   409.1  740.79   418.8  741.25
   428.5  741.94   457.8  744.99   477.2   746.9     487   747.8   496.7  748.59
#Mann= 3 , 0 , 0
       0      .1       0   165.6    .045       0   243.5     .09       0
Bank Sta=165.6,243.5
XS Rating Curve= 0 ,0
Exp/Cntr=0.3,0.1

Type RM Length L Ch R = 1 ,99131   ,477,471.2,465.4
XS GIS Cut Line= 3
      1583303.65      316155.355     1583640.456      316054.661
     1583789.761      315973.063
#Sta/Elev= 30
       0  774.64    39.1  751.96    48.8  746.87    58.6   742.9    68.4  739.68
    78.1  736.68   117.2  724.78   136.7  718.75   146.5  715.81   156.2  713.43
     166  712.23   175.8     712   205.1     712   214.8  712.35   224.6  713.66
   234.4  715.92   244.1  718.45   263.6  723.26   273.4  725.43   283.2  727.24
     293  728.65   302.7  729.83   312.5  730.87   351.5  734.43   370.4  735.79
   389.4  736.59   427.2   737.9   436.6  738.34     465  740.15   521.7  744.17
#Mann= 3 , 0 , 0
       0      .1       0   156.2    .045       0   224.6     .09       0
Bank Sta=156.2,224.6
XS Rating Curve= 0 ,0
Exp/Cntr=0.3,0.1

Type RM Length L Ch R = 1 ,98659.8 ,395.2,393.5,391.7
XS GIS Cut Line= 3
     1583498.095      316643.202     1583987.859      316343.253
     1584059.473      316265.128
#Sta/Elev= 30
       0  785.76    68.1  751.56    77.9  746.95    87.6  742.96    97.3  739.45
   165.5  715.99   175.2  713.32     185  712.23   194.7  712.01   204.4     712
   243.4  712.03   253.1  712.64   262.8  714.16   272.6  716.29     292  720.78
   311.5  725.11   321.2  726.95     331  727.96   389.4  730.61   418.6  732.24
   467.2  735.27     477  735.77   564.6  739.02   574.3  739.43     584  740.03
   593.6  741.03   603.2  742.22   622.5   744.7   670.7  751.32   680.3  752.39
#Mann= 3 , 0 , 0
       0      .1       0   175.2    .045       0   253.1     .08       0
Bank Sta=175.2,253.1
XS Rating Curve= 0 ,0
Exp/Cntr=0.3,0.1

Type RM Length L Ch R = 1 ,98266.3 ,275.4,275.9,276.6
XS GIS Cut Line= 3
     1583725.525      316981.744     1584175.178      316655.355
     1584253.303      316568.549
#Sta/Elev= 30
       0  781.01    29.2  764.16    48.7  753.15    58.5  747.96    68.2  743.68
      78  740.18    87.7  736.97   146.2  718.34     156  715.37   165.7  713.17
   175.5  712.12   185.2     712     234  712.07   243.7  712.64   253.4  714.49
   263.2  717.18   282.7  723.13   292.4  725.62   302.2  726.67   311.9  726.98
   360.7  727.42   380.2  727.79   506.9  731.64   526.4  732.48   594.6  736.05
   604.3   736.8     614  738.07   623.8  739.76   662.7  747.07   672.4  748.54
#Mann= 3 , 0 , 0
       0      .1       0   165.7    .045       0   243.7     .08       0
Bank Sta=165.7,243.7
XS Rating Curve= 0 ,0
Exp/Cntr=0.3,0.1

Type RM Length L Ch R = 1 ,97990.4 ,269.4,271.6,273.7
XS GIS Cut Line= 3
     1583890.456      317195.286     1584331.428      316891.466
     1584418.233      316790.772
#Sta/Elev= 30
       0  790.17    68.2  751.59    77.9  746.42    87.6  742.22   155.8  717.48
   165.5  714.35   175.3  712.41     185  712.02   194.7     712   253.2  712.06
   262.9  712.47   272.6  713.35   292.1  715.71   301.8  717.99   321.3  725.45
     331  727.91   340.8  727.98   360.2   726.5     370  726.04   389.5  725.67
   418.7  725.78   447.9   726.2   467.4  727.06   496.6  729.55   535.5     735
   573.5  739.98     621  745.26     640  747.84   649.5  748.86   668.4  749.21
#Mann= 3 , 0 , 0
       0      .1       0   165.5    .045       0   272.6     .08       0
Bank Sta=165.5,272.6
XS Rating Curve= 0 ,0
Exp/Cntr=0.3,0.1

Type RM Length L Ch R = 1 ,97718.7 ,540.3,535.7,531.3
XS GIS Cut Line= 4
     1584105.733      317453.966       1584147.4      317328.966
     1584505.039      317129.313     1584564.067      317058.133
#Sta/Elev= 30
       0  789.34    56.5  759.85    65.9   755.6   112.9  738.16   131.8  731.48
   141.5  728.83   180.5  720.09     200  715.38   209.8  713.32   219.5  712.28
   229.3  712.01     239     712   268.3     712     278  712.12   287.8  712.49
     317  714.54   326.8  715.62   336.6  718.47   346.3  722.44   356.1  726.13
   365.8  728.61   375.6  729.54   385.3  729.85   453.6  731.21   512.1  732.69
   531.6   733.5   550.6  734.75   559.8  735.69   615.3  744.14   633.8  746.73
#Mann= 3 , 0 , 0
       0      .1       0   209.8    .045       0   287.8     .08       0
Bank Sta=209.8,287.8
XS Rating Curve= 0 ,0
Exp/Cntr=0.3,0.1

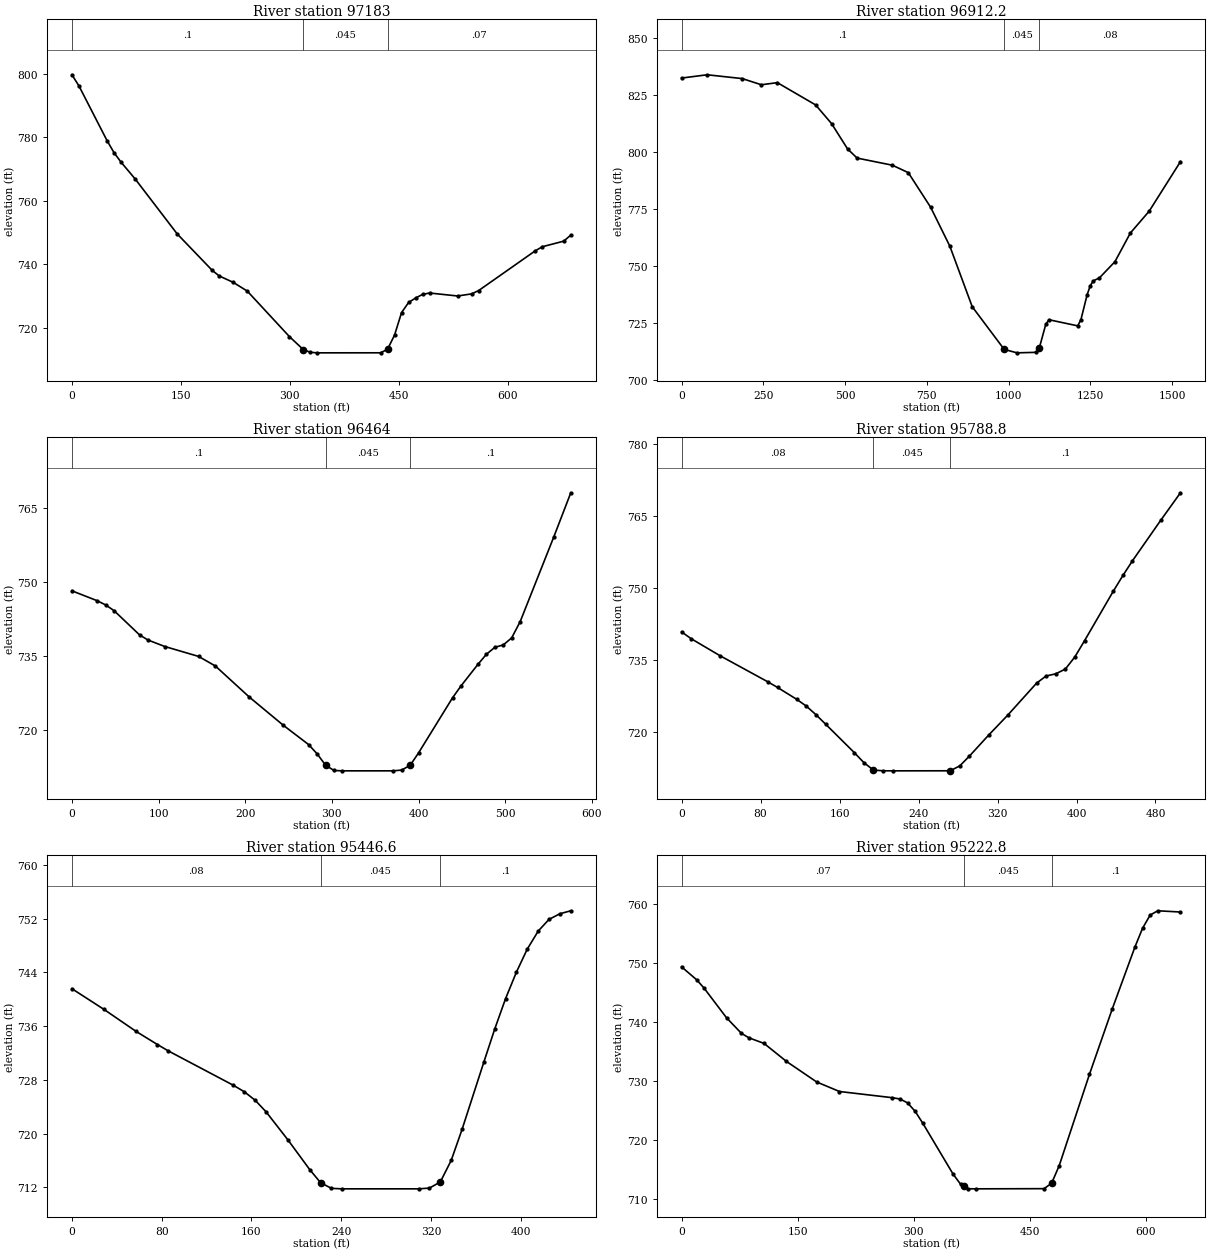
Type RM Length L Ch R = 1 ,97183   ,270.4,270.8,270.6
XS GIS Cut Line= 4
     1584296.706      317724.799     1584506.775      317756.049
     1584777.608      317523.411     1584845.317      317427.924
#Sta/Elev= 30
       0   799.8     9.6  796.31    48.3  779.02    57.9  775.21    67.6  772.21
    86.9  766.94   144.8  749.57   193.1  738.03   202.7  736.28     222  734.25
   241.3   731.5   299.2  717.15   318.5  713.01   328.2  712.16   337.8     712
   424.7  712.01   434.3  713.12     444  717.62   453.6   724.7   463.3   727.9
   472.9  729.31   482.6  730.46   492.2  730.89   530.8  729.95   550.1  730.62
   559.8  731.68   637.7  744.23   647.4  745.51   676.7  747.26   686.5  749.17
#Mann= 3 , 0 , 0
       0      .1       0   318.5    .045       0   434.3     .07       0
Bank Sta=318.5,434.3
XS Rating Curve= 0 ,0
Exp/Cntr=0.3,0.1

Type RM Length L Ch R = 1 ,96912.2 ,443.5,448.1,453.1
XS GIS Cut Line= 5
     1583908.338      318136.692      1584444.45      318160.293
     1584965.108      317716.119     1585050.178      317591.119
     1585194.275      317539.036
#Sta/Elev= 30
       0  832.44    78.1  833.88   185.4  832.21   243.9   829.5   292.7  830.43
   409.8  820.66   458.6  812.46   507.4  801.38   536.6  797.35   644.2  794.23
   693.1  790.97   761.5  775.78   820.2  758.71   888.6  732.17   986.4  713.45
  1025.5  711.94  1084.1  712.16  1093.9  714.16  1113.5  724.42  1123.2  726.46
  1211.2  723.77    1221  726.47  1239.9  737.37  1249.4  741.32  1258.8   743.5
  1277.7  744.83    1325  751.91  1372.2  764.49  1429.7  774.06  1525.4   795.8
#Mann= 3 , 0 , 0
       0      .1       0   986.4    .045       0  1093.9     .08       0
Bank Sta=986.4,1093.9
XS Rating Curve= 0 ,0
Exp/Cntr=0.3,0.1

Type RM Length L Ch R = 1 ,96464   ,663.6,675.2,686.7
XS GIS Cut Line= 4
     1584869.622      318394.938       1584959.9      318256.049
     1585242.886      318101.536     1585327.956      318080.702
#Sta/Elev= 30
       0   748.3    29.2  746.29      39  745.43    48.7  744.27      78  739.37
    87.7  738.33   107.2  737.01   146.2     735   165.6  733.05   204.7  726.76
   243.8  721.06   273.1  717.13   282.9  715.26   292.7  712.95   302.4  711.87
   312.2   711.8   370.8   711.8   380.6  711.96   390.4  712.93   400.1  715.46
   439.2   726.6     449  729.02   468.5  733.38   478.3  735.43   488.1  736.85
   497.8  737.33   507.5  738.76   517.3  742.06   556.2  759.28   575.7  768.18
#Mann= 3 , 0 , 0
       0      .1       0   292.7    .045       0   390.4      .1       0
Bank Sta=292.7,390.4
XS Rating Curve= 0 ,0
Exp/Cntr=0.3,0.1

Type RM Length L Ch R = 1 ,95788.8 ,333.9,342.2,350.5
XS GIS Cut Line= 2
     1585077.956       318795.98     1585583.164      318802.924
#Sta/Elev= 30
       0  740.81     9.7  739.39    38.9  735.84    87.4  730.38    97.2  729.21
   116.6  726.73   126.3  725.32     136  723.54   145.8  721.56   174.9  715.61
   184.6  713.52   194.3  711.96     204  711.81   213.8   711.8   272.1  711.81
   281.8  712.84   291.5  714.87   310.9  719.24   330.4  723.44   359.5   730.1
   369.2  731.61   378.9  732.05   388.7  733.05   398.4  735.61   408.1  738.96
   437.2  749.29     447  752.59   456.7  755.67   485.8  764.26   505.3  769.86
#Mann= 3 , 0 , 0
       0     .08       0   194.3    .045       0   272.1      .1       0
Bank Sta=194.3,272.1
XS Rating Curve= 0 ,0
Exp/Cntr=0.3,0.1

Type RM Length L Ch R = 1 ,95446.6 ,223.4,223.8,224.3
XS GIS Cut Line= 3
     1585006.775      319002.577     1585058.858      319058.133
     1585400.872      319195.286
#Sta/Elev= 28
       0  741.56    28.6  738.48    57.1  735.22    76.2  733.26    85.8  732.32
     144  727.19   153.7  726.23   163.4  724.96   173.1  723.24   192.5  719.08
   211.9  714.67   221.6  712.72   231.3  711.87     241   711.8   308.9   711.8
   318.6  711.91   328.3  712.82     338  716.02   347.7  720.64   367.1  730.64
   376.8  735.56   386.5   740.1   396.2  744.05   405.8  747.45   415.6  750.14
   425.2  751.87   434.9  752.71   444.6  753.15
#Mann= 3 , 0 , 0
       0     .08       0   221.6    .045       0   328.3      .1       0
Bank Sta=221.6,328.3
XS Rating Curve= 0 ,0
Exp/Cntr=0.3,0.1

Type RM Length L Ch R = 1 ,95222.8 ,492.9,494.9,497
XS GIS Cut Line= 3
     1584800.178      319137.994     1584909.553       319233.48
     1585369.622      319427.924
#Sta/Elev= 30
       0  749.36    19.4  747.18      29  745.77    58.1  740.74    77.4   738.1
    87.1  737.35   106.5  736.41   135.5  733.36   174.6  729.88     204  728.27
   272.5  727.22   282.3     727   292.1  726.34   301.9   724.9   311.7   722.9
   350.9  714.28   360.6  712.57   365.1 712.221   370.4  711.81   380.2   711.8
   468.4  711.83   478.2  712.75     488  715.73   527.1  731.19   556.5  742.23
   585.9  752.74   595.7  755.89   605.5  758.12   615.3  758.85   644.7  758.64
#Mann= 3 , 0 , 0
       0     .07       0   365.1    .045       0   478.2      .1       0
Bank Sta=365.1,478.2
XS Rating Curve= 0 ,0
Exp/Cntr=0.3,0.1

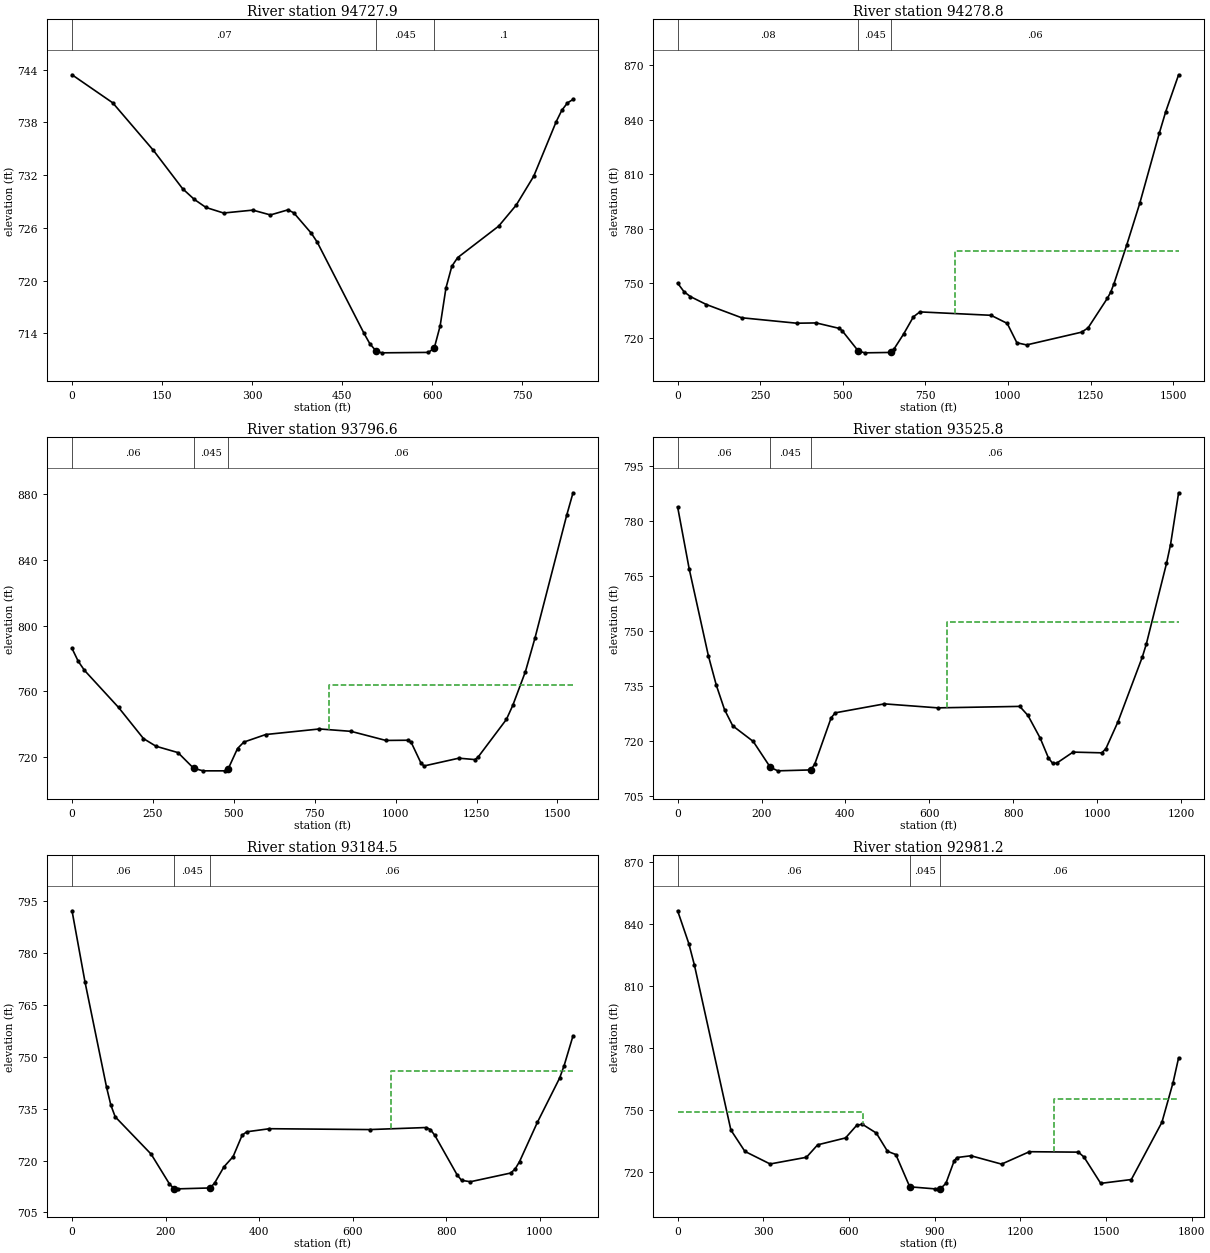
Type RM Length L Ch R = 1 ,94727.9 ,447.6,449.1,450.2
XS GIS Cut Line= 4
     1584548.442      319516.466      1584669.97      319627.577
     1585202.956      319912.299     1585267.192      319900.147
#Sta/Elev= 30
       0  743.42    67.8  740.23   135.6  734.82   184.2  730.46   203.6  729.25
   223.1  728.33   252.4   727.7   301.1  728.03   330.4  727.48   359.6  728.06
   369.3  727.72   398.6  725.39   408.3  724.39   486.3  714.01     496  712.83
   505.8  712.05   515.5   711.8   593.5  711.85   603.2  712.34     613  714.86
   622.7  719.18   632.5  721.65   642.2  722.63   710.5  726.21   739.7   728.6
   768.9  731.89   806.3  738.09   815.6  739.38     825  740.22   834.3  740.62
#Mann= 3 , 0 , 0
       0     .07       0   505.8    .045       0   603.2      .1       0
Bank Sta=505.8,603.2
XS Rating Curve= 0 ,0
Exp/Cntr=0.3,0.1

Type RM Length L Ch R = 1 ,94278.8 ,481.8,482.2,482.4
XS GIS Cut Line= 4
     1584334.032      319912.473     1584500.699      320011.431
     1584969.449       320297.89     1585505.907      320855.181
#Sta/Elev= 30
       0   750.1    19.4  745.38    38.8   742.7    87.2  738.34   193.8  731.08
   360.6  728.08   419.5  728.24   488.1  725.29   497.9  724.02     547   712.8
   566.6   711.8   645.1  712.02   654.9  713.85   684.3  722.18   713.8  731.59
   733.4   734.3   948.8  732.43   997.8  727.98  1027.1  717.33  1056.5  716.15
    1223  723.16  1242.6  725.51  1301.3  741.86  1311.1  745.14  1320.9  749.74
    1360  771.29  1399.2  794.05    1458  832.35  1477.6  844.28  1516.7   864.6
#Mann= 3 , 0 , 0
       0     .08       0     547    .045       0   645.1     .06       0
#XS Ineff= 2 , 0
                          838.97          767.96
Permanent Ineff=
       F       F
Bank Sta=547,645.1
XS Rating Curve= 0 ,0
Exp/Cntr=0.3,0.1

Type RM Length L Ch R = 1 ,93796.6 ,282.8,270.8,259
XS GIS Cut Line= 5
     1584119.274      320441.746     1584320.663      320441.746
     1584673.094      320663.968     1584902.261       320533.76
     1585427.782      320943.723
#Sta/Elev= 30
       0  786.15    19.2  778.34    38.4  772.85   143.8   750.3   220.8  731.39
   259.5  726.74   327.4  722.88   375.8  713.36   404.9   711.8   472.7   711.8
   482.4  712.94   511.4  725.36   530.8  729.26   598.6  733.86   764.5  737.24
   862.1  735.79   969.8  730.27  1038.4  730.39  1048.2  729.02  1077.6  716.81
  1087.4  714.75  1195.3  719.49  1244.3  718.65  1254.1  719.99  1342.3  743.06
  1361.9  751.55  1401.1  772.13  1430.5  792.46  1528.5  867.03  1548.1  880.71
#Mann= 3 , 0 , 0
       0     .06       0   375.8    .045       0   482.4     .06       0
#XS Ineff= 2 , 0
                          795.04          764.03
Permanent Ineff=
       F       F
Bank Sta=375.8,482.4
XS Rating Curve= 0 ,0
Exp/Cntr=0.3,0.1

Type RM Length L Ch R = 1 ,93525.8 ,360.1,341.3,322.9
XS GIS Cut Line= 4
     1584124.831      320815.077     1584206.428      320802.924
     1585144.397      320835.505     1585286.687      320934.768
#Sta/Elev= 30
       0  783.92    27.5  767.04    73.3  743.26    92.3  735.18   111.8  728.54
   131.4   724.1   180.3  719.83     221712.7615   238.9   711.8   317.1  712.05
   326.9  713.62     366  726.28   375.8  727.65   493.1   730.1   620.2  729.01
   815.7  729.41   835.3  726.93   864.6  720.71   884.2  715.31   893.9  713.89
   903.7  713.89   942.8  716.92  1011.3  716.72    1021  717.84    1050  725.22
  1107.8  742.85  1117.4   746.4  1165.6  768.46  1175.2  773.59  1194.5  787.78
#Mann= 3 , 0 , 0
       0     .06       0     221    .045       0   317.1     .06       0
#XS Ineff= 2 , 0
                          641.98          752.55
Permanent Ineff=
       F       F
Bank Sta=221,317.1
XS Rating Curve= 0 ,0
Exp/Cntr=0.3,0.1

Type RM Length L Ch R = 1 ,93184.5 ,210.5,203.3,196.1
XS GIS Cut Line= 5
     1584350.525      321282.091     1584440.803      321217.855
     1584817.539      320837.647     1584937.331      320846.327
     1585199.483      321002.577
#Sta/Elev= 30
       0  792.31    27.7  771.72    73.9  741.17    83.1  736.01    92.3  732.66
   169.2  721.84   208.1  713.27   217.8  711.86   227.6   711.8   295.7  712.06
   305.4   713.6   324.9  718.17   344.4  721.12   363.8  727.34   373.6  728.32
   422.2  729.21   636.3  728.96   756.9  729.55   766.2  728.98   775.7  727.31
   823.4  715.86   832.9  714.26     852  713.86   937.8  716.37   947.4  717.52
   956.9  719.68     995  731.03  1042.7  743.89  1052.3   747.5  1071.3   756.1
#Mann= 3 , 0 , 0
       0     .06       0   217.8    .045       0   295.7     .06       0
#XS Ineff= 2 , 0
                          681.31          746.05
Permanent Ineff=
       F       F
Bank Sta=217.8,295.7
XS Rating Curve= 0 ,0
Exp/Cntr=0.3,0.1

Type RM Length L Ch R = 1 ,92981.2 ,85.5,85.1,85.5
XS GIS Cut Line= 6
     1584117.956      321518.088     1584349.718      321744.414
     1584598.789      321405.355     1584840.108      320948.758
     1584880.039      320853.272     1585218.979      321045.879
#Sta/Elev= 30
       0  846.43    39.3   830.5    58.9  820.06   186.5   740.2   235.6  729.84
   323.9  723.75   451.1  726.99   490.3  733.02   588.1  736.37   627.2  742.49
   646.8     743   695.7  738.74   734.9   729.9   764.1  728.32   812.9  712.68
   899.9   711.7     920  711.71   939.5  714.36   968.8   725.4   978.5  726.87
  1027.2  727.73  1134.4  723.68  1231.9  729.69  1403.6  729.48  1423.1  727.09
  1481.6  714.35  1588.8  716.21    1696  743.97    1735   763.2  1754.4   775.2
#Mann= 3 , 0 , 0
       0     .06       0   812.9    .045       0     920     .06       0
#XS Ineff= 2 , 0
          650.13  748.78 1319.75           755.1
Permanent Ineff=
       F       F
Bank Sta=812.9,920
XS Rating Curve= 0 ,0
Exp/Cntr=0.3,0.1

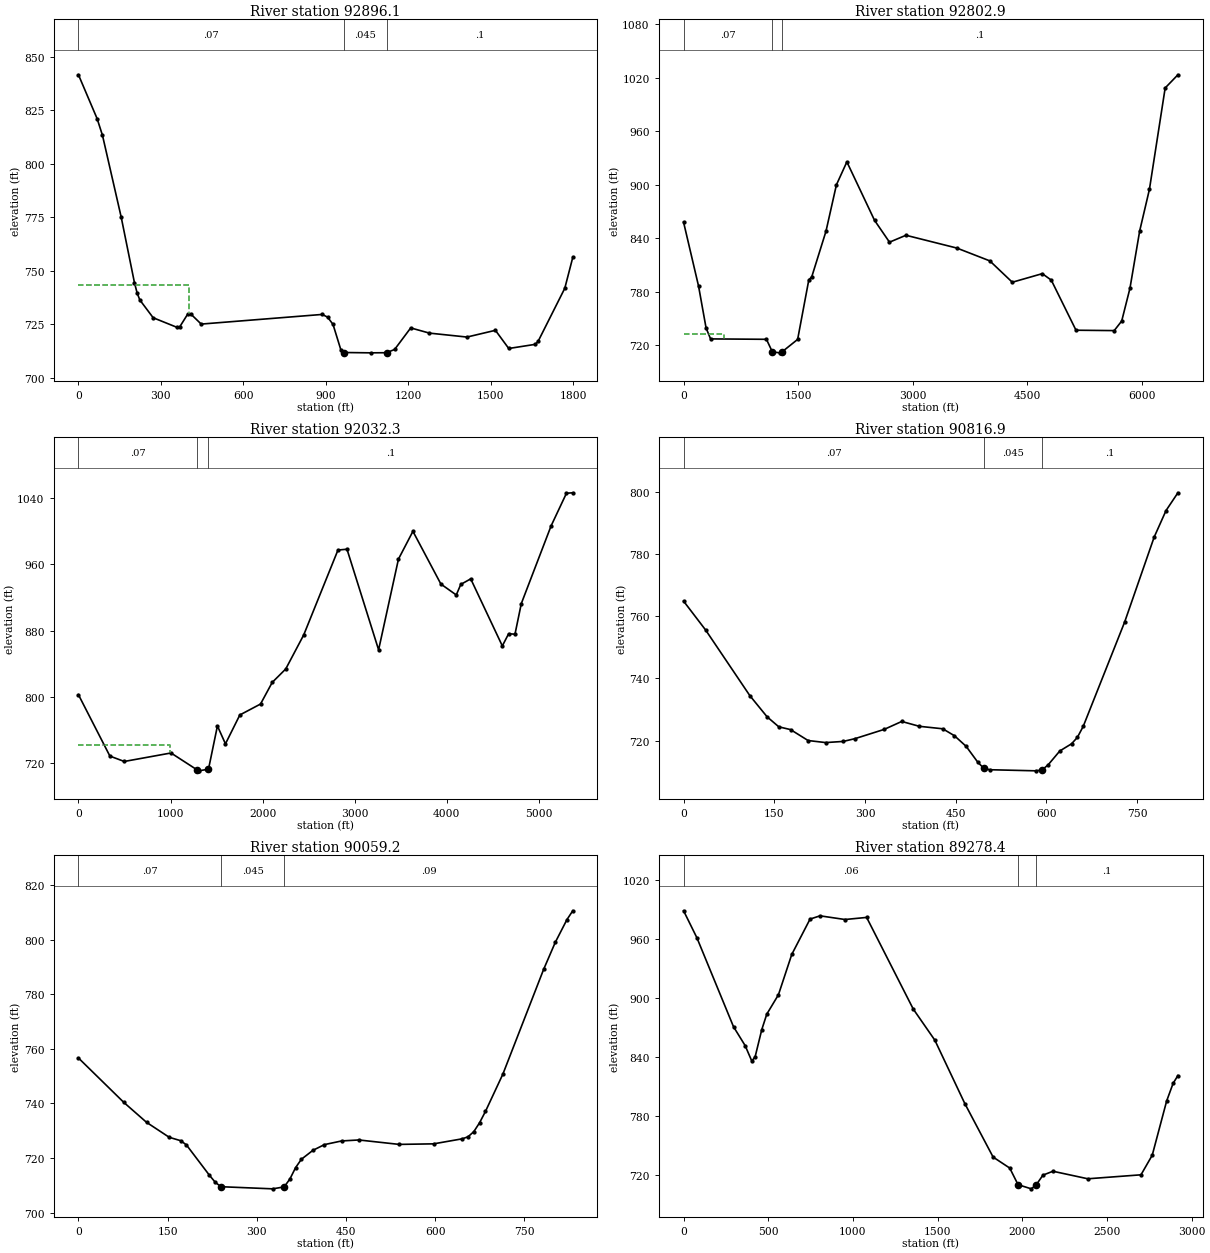
Type RM Length L Ch R = 1 ,92896.1 ,88.5,93.2,96.5
XS GIS Cut Line= 6
      1584053.72      321526.769     1584388.789      321821.907
     1584657.817      321460.911     1584899.136      321004.313
     1584939.067      320908.827     1585183.858      321047.716
#Sta/Elev= 30
       0  841.57      68  821.05    87.4  813.29   155.3   775.2   203.8  744.41
   213.6  739.59   223.3  736.39   271.8  728.09   359.2  723.57   368.9  723.94
     398   729.9   407.7  729.96   446.5  725.13     887  729.64   906.5  728.34
     926  724.98   955.2  712.82   967.3711.8528  1062.4   711.7  1120.8  711.76
  1150.1  713.28  1208.6  723.34  1276.8  720.91  1413.2  719.07  1516.7  722.22
  1565.2  713.73  1662.3  715.68    1672  717.07    1769  741.83  1798.1  756.27
#Mann= 3 , 0 , 0
       0     .07       0   967.3    .045       0  1120.8      .1       0
#XS Ineff= 2 , 0
          402.13  743.47
Permanent Ineff=
       F       F
Bank Sta=967.3,1120.8
XS Rating Curve= 0 ,0
Exp/Cntr=0.3,0.1

Type RM Length L Ch R = 1 ,92802.9 ,737.9,770.6,802.9
XS GIS Cut Line= 6
     1583867.956      321542.394     1584338.372      321880.355
     1584869.622      321290.077     1585751.567      320845.633
     1586855.446      321501.158     1588751.567       323556.57
#Sta/Elev= 30
       0  858.04   196.4  786.37   294.5  739.59   353.4  727.31  1084.9  726.86
  1162.7  712.75  1259.9   711.7  1284.2712.4464  1493.5  726.75  1639.6   793.4
  1678.6  796.94  1864.4  847.86  2001.3  899.95  2138.2  925.68  2500.2  860.21
  2696.2  835.69  2911.8  843.44  3578.3   829.1  4009.9  814.73  4304.2   790.8
  4696.7  800.42  4814.5  793.19  5138.3  737.04  5638.7  736.62  5736.8  747.34
  5844.7     784  5972.3  848.36  6099.8  894.88  6305.9 1008.49  6472.7 1023.26
#Mann= 3 , 0 , 0
       0     .07       0  1162.7    .045       0  1284.2      .1       0
#XS Ineff= 2 , 0
          530.66  732.82
Permanent Ineff=
       F       F
Bank Sta=1162.7,1284.2
XS Rating Curve= 0 ,0
Exp/Cntr=0.3,0.1

Type RM Length L Ch R = 1 ,92032.3 ,1197.4,1215.4,1232.9
XS GIS Cut Line= 5
     1583665.829      321713.155       1584647.4      321970.633
     1585163.815       322258.47     1585342.242      323318.227
     1587699.049      324609.088
#Sta/Elev= 30
       0  802.58   341.5  728.51   497.6  722.01    1005  732.26  1285.5712.0815
  1305.5   710.7  1412.2  712.68  1509.1   764.9  1596.3  743.28  1752.5  778.14
  1977.2  791.35  2104.2  817.46  2250.8  833.65  2446.2  874.75    2818  977.22
    2916  978.22  3259.3  856.79    3475  966.34    3632  999.82    3936  936.13
  4102.7  923.01  4151.7  935.74  4259.6  942.44  4602.9  861.48  4671.5  876.24
  4740.2   875.6  4808.8  912.56  5132.5  1006.4  5299.2  1045.8  5367.8 1046.35
#Mann= 3 , 0 , 0
       0     .07       0  1285.5    .045       0  1412.2      .1       0
#XS Ineff= 2 , 0
           993.8  742.41
Permanent Ineff=
       F       F
Bank Sta=1285.5,1412.2
XS Rating Curve= 0 ,0
Exp/Cntr=0.3,0.1

Type RM Length L Ch R = 1 ,90816.9 ,755.7,757.7,759.9
XS GIS Cut Line= 4
     1583581.428      321866.466     1583654.345      321960.216
      1583803.65      322491.466     1583821.011      322637.299
#Sta/Elev= 30
       0  764.89    36.5  755.58   109.6  734.46   138.1  727.65   157.5  724.42
   176.9  723.53   205.9  720.01   234.9  719.35     264  719.72   283.4  720.61
   331.8   723.6   360.8  726.15   389.8  724.59   428.6  723.79   447.9  721.56
   467.3  718.14   486.7  712.99   496.3  711.12     506  710.61   583.5  710.25
   593.2   710.6   602.8  712.16   622.2  716.65   641.6  718.96   651.2  721.01
   660.9  724.56   729.4  758.15   778.3  785.54   797.9  794.07   817.5  799.78
#Mann= 3 , 0 , 0
       0     .07       0   496.3    .045       0   593.2      .1       0
Bank Sta=496.3,593.2
XS Rating Curve= 0 ,0
Exp/Cntr=0.3,0.1

Type RM Length L Ch R = 1 ,90059.2 ,781.7,780.8,779.7
XS GIS Cut Line= 4
     1582942.539      322140.772     1582987.678      322286.605
     1583081.428      322790.077       1583147.4      322942.855
#Sta/Elev= 30
       0  756.63    76.3  740.37   114.5  733.08   152.7  727.59     172  726.35
   181.6   724.8   220.3  713.68     230  711.14   239.6  709.51   326.6  708.73
   345.9  709.44   355.6  712.35   365.2  716.52   374.9  719.56   394.2  722.82
   413.6  724.92   442.5  726.26   471.5  726.62   539.2     725   597.2   725.2
   645.5  727.05   655.1  727.79   664.8  729.67   674.6  732.96   684.4  737.08
   713.7  750.74   782.2  789.07   801.8  798.97   821.4  807.29   831.2  810.52
#Mann= 3 , 0 , 0
       0     .07       0   239.6    .045       0   345.9     .09       0
Bank Sta=239.6,345.9
XS Rating Curve= 0 ,0
Exp/Cntr=0.3,0.1

Type RM Length L Ch R = 1 ,89278.4 ,1105.7,1105.4,1098.8
XS GIS Cut Line= 4
     1582528.129      320541.206     1582206.428      322380.355
     1582393.928      323192.855     1582477.261      323394.244
#Sta/Elev= 30
       0  988.31    78.6  960.93   294.8  870.65   363.6  851.45   402.9  835.78
   422.6  840.19   461.8  867.75   491.3   883.4   560.1  903.08   638.7  943.96
   746.8  979.88   805.8  983.18   953.2  979.45  1080.9  981.57  1356.1  888.59
  1483.8  856.95  1660.7  792.65  1827.8  738.34  1925.9   727.2    1975  710.34
  2053.5  706.12  2082.9  710.36  2122.1  720.04    2181  723.97    2387  716.33
  2700.9  720.36  2767.3  740.22  2852.5  795.32  2890.4  813.09  2918.9  821.11
#Mann= 3 , 0 , 0
       0     .06       0    1975    .045       0  2082.9      .1       0
Bank Sta=1975,2082.9
XS Rating Curve= 0 ,0
Exp/Cntr=0.3,0.1