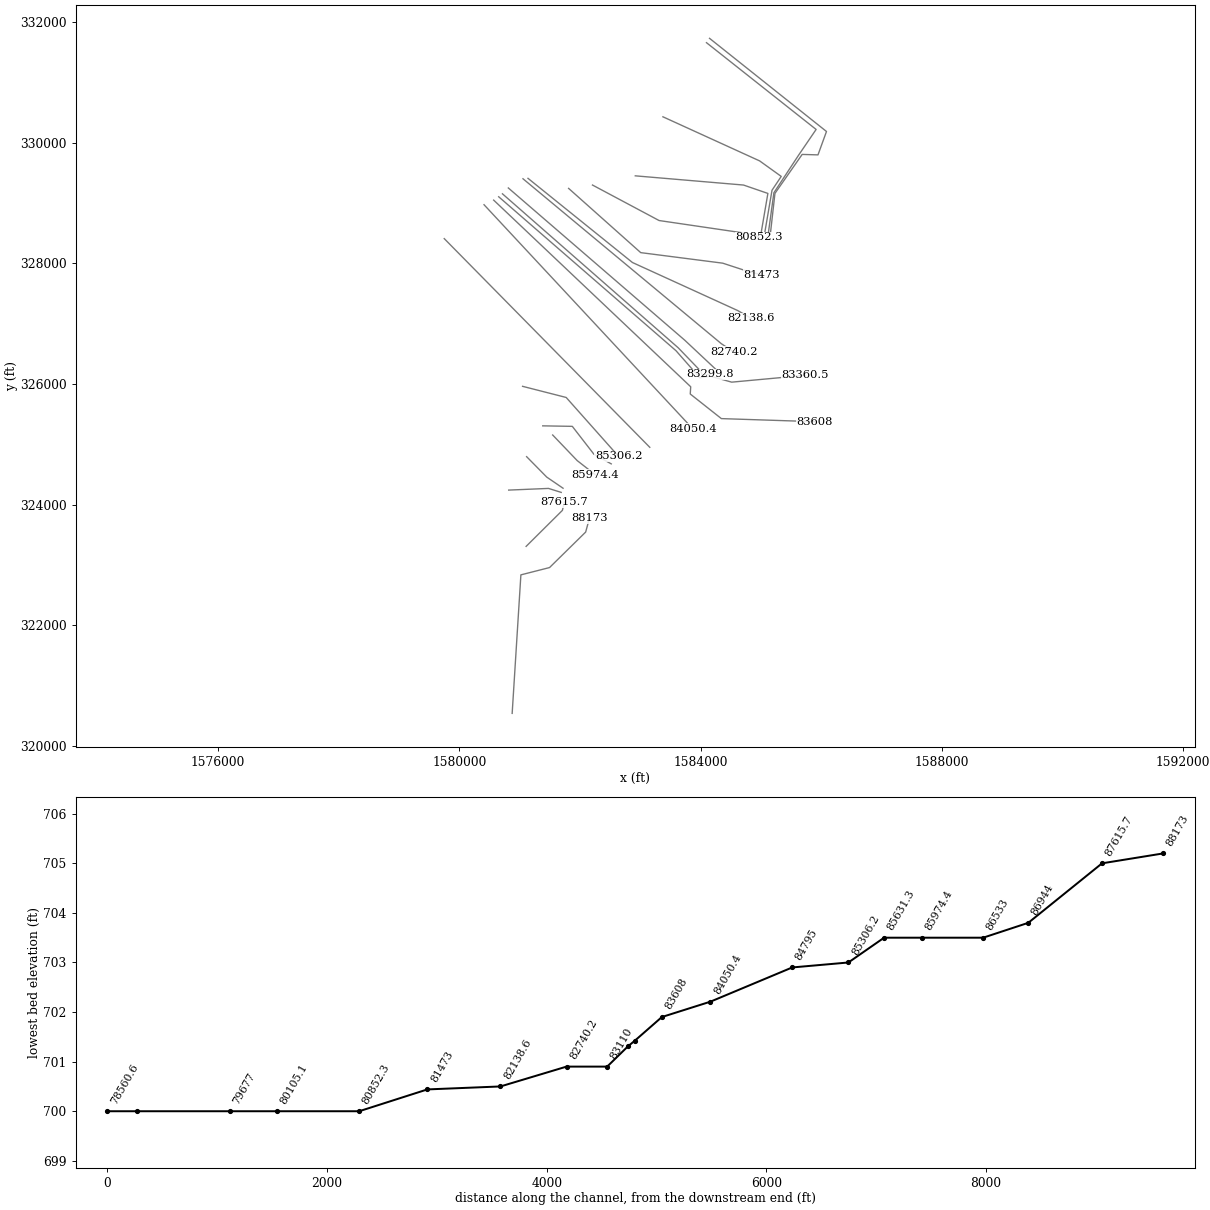
HEC-RAS study MDISLCRK_C.prj: MDISLCRK_C

--- MDISLCRK_C.g01 (geometry) --- (continued)

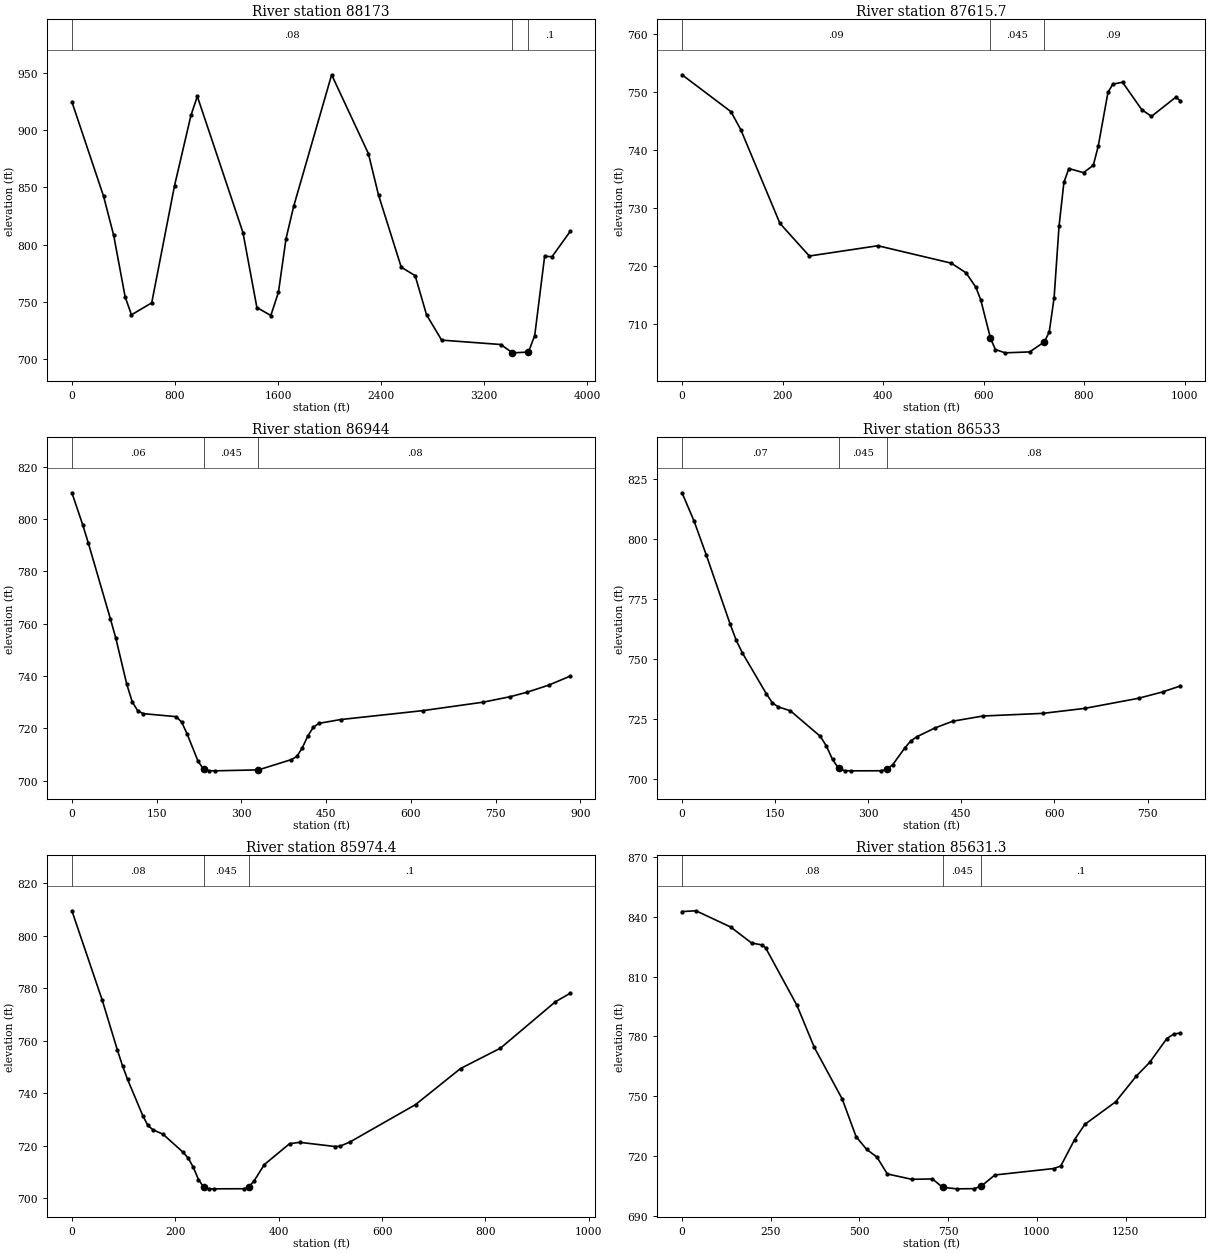
Type RM Length L Ch R = 1 ,88173   ,569.5,557.4,551.3
XS GIS Cut Line= 5
     1580875.229      320538.565     1581019.807      322835.593
     1581495.129      322956.751     1582094.087      323545.293
     1582156.587       323774.46
#Sta/Elev= 30
       0  924.86   245.9   842.2   324.6  807.93   413.1  754.24   462.3  738.48
   619.6  748.94   796.7   851.5   924.6  913.24   973.7  929.68  1327.8  810.52
    1436  744.88  1544.2  737.87  1603.2  758.19  1662.2  805.12  1721.3  833.31
  2016.3  948.57  2301.6  879.59  2380.1  843.36  2556.6  780.16  2664.6  772.76
  2752.8  738.54  2870.2  716.33  3329.1  712.49    3417  705.46  3426.8   705.2
  3543.9  705.89  3592.8  720.29  3669.8  789.77  3726.8  789.28  3869.4  811.69
#Mann= 3 , 0 , 0
       0     .08       0    3417    .045       0  3543.9      .1       0
Bank Sta=3417,3543.9
XS Rating Curve= 0 ,0
Exp/Cntr=0.3,0.1

Type RM Length L Ch R = 1 ,87615.7 ,688.1,671.6,654.1
XS GIS Cut Line= 3
     1581106.735      323307.914     1581708.235      323905.108
     1581742.747      324045.197
#Sta/Elev= 30
       0   752.9    97.4  746.54   116.9  743.44   194.8   727.3   253.3  721.68
   389.7  723.45   535.8  720.45   565.1  718.78   584.6  716.32   594.3  714.16
   613.8  707.51   623.5  705.57     643     705   691.7  705.16     721  706.88
   730.7  708.59   740.4   714.5   750.2  726.81   759.9  734.36   769.7  736.75
   798.9  736.04   818.4  737.31   828.1  740.56   847.6  749.88   857.2  751.28
   876.5  751.62   914.9  746.88   934.2  745.74   982.3  749.02   991.9  748.44
#Mann= 3 , 0 , 0
       0     .09       0   613.8    .045       0     721     .09       0
Bank Sta=613.8,721
XS Rating Curve= 0 ,0
Exp/Cntr=0.3,0.1

Type RM Length L Ch R = 1 ,86944   ,430.2,411.1,392.8
XS GIS Cut Line= 3
     1580817.539      324241.466     1581477.261      324269.244
     1581689.067      324203.272
#Sta/Elev= 30
       0  809.98    19.4  797.58    29.1  790.76      68  761.94    77.7  754.48
    97.1  736.88   106.8  730.14   116.5  726.73   126.2  725.64   184.5  724.49
   194.2  722.43   203.9   717.9   223.3  707.47     233  704.41   242.8  703.82
   252.5   703.8   330.2  704.17   388.4  708.09   398.1  709.28   407.8  712.59
   417.6  717.15   427.3  720.43     437  721.93   475.8  723.39   621.5   726.8
   727.8  730.02     776  732.13     805  733.79   843.6   736.5   882.2  739.99
#Mann= 3 , 0 , 0
       0     .06       0     233    .045       0   330.2     .08       0
Bank Sta=233,330.2
XS Rating Curve= 0 ,0
Exp/Cntr=0.3,0.1

Type RM Length L Ch R = 1 ,86533   ,558.8,558.5,558.1
XS GIS Cut Line= 3
      1581114.95      324795.845     1581448.284      324457.304
     1581719.117      324272.408
#Sta/Elev= 30
       0  819.08    19.4   807.3    38.8  793.41    77.6  764.42    87.3  757.75
      97  752.61   135.7  735.56   145.4   731.8   155.1  730.06   174.5  728.47
     223  717.78   232.7  713.72   242.4  708.24   252.1  704.59   261.8  703.58
   271.5   703.5     320  703.53   329.7  704.09   339.4  706.06   358.8  712.98
   368.4  715.91   378.1  717.64   407.2  721.29   436.3  724.14   484.8  726.29
   581.2  727.39   648.7  729.46   735.5  733.67   774.1   736.3     803  738.79
#Mann= 3 , 0 , 0
       0     .07       0   252.1    .045       0   329.7     .08       0
Bank Sta=252.1,329.7
XS Rating Curve= 0 ,0
Exp/Cntr=0.3,0.1

Type RM Length L Ch R = 1 ,85974.4 ,342.3,343.1,345.7
XS GIS Cut Line= 3
     1581547.242       325155.22     1581953.492      324730.741
     1582250.367       324498.97
#Sta/Elev= 30
       0  809.49    58.8  775.34    88.1  756.33    97.9  750.42   107.7   745.2
   137.1  731.41   146.9  727.66   156.7  726.02   176.3  724.32   215.4  717.38
   225.2  715.16     235  711.67   244.8  707.05   254.6  704.27   264.4  703.54
   274.2   703.5     333  703.54   342.7  704.32   352.5  706.54   372.1  712.73
   421.1  720.71   440.7  721.23   509.2  719.63     519  719.76   538.6  721.44
   664.8  735.62   751.7  749.35     829  757.13   935.2   774.8   964.2  778.08
#Mann= 3 , 0 , 0
       0     .08       0   254.6    .045       0   342.7      .1       0
Bank Sta=254.6,342.7
XS Rating Curve= 0 ,0
Exp/Cntr=0.3,0.1

Type RM Length L Ch R = 1 ,85631.3 ,325.8,325.1,322.3
XS GIS Cut Line= 4
     1581382.296      325306.831     1581872.763      325298.449
     1582232.138      324834.908     1582518.596      324676.054
#Sta/Elev= 30
       0  842.72    39.2  843.12   137.4  834.93   196.2  826.91   225.6  825.97
   235.5  824.53   323.8  795.62   372.8  774.48   451.3  748.64   490.5   729.7
   519.9  723.36   549.2  719.44   578.5  710.97     647   708.3   705.6  708.46
   734.3704.2657     774   703.5   822.9  703.59   842.5  704.76   881.6  710.46
  1047.7   713.7  1067.3  714.98    1106  728.16  1134.9  735.86  1221.6  747.14
  1279.4  759.97  1317.9  767.03  1366.1  778.96  1385.4  781.18  1404.6  781.78
#Mann= 3 , 0 , 0
       0     .08       0   734.3    .045       0   842.5      .1       0
Bank Sta=734.3,842.5
XS Rating Curve= 0 ,0
Exp/Cntr=0.3,0.1

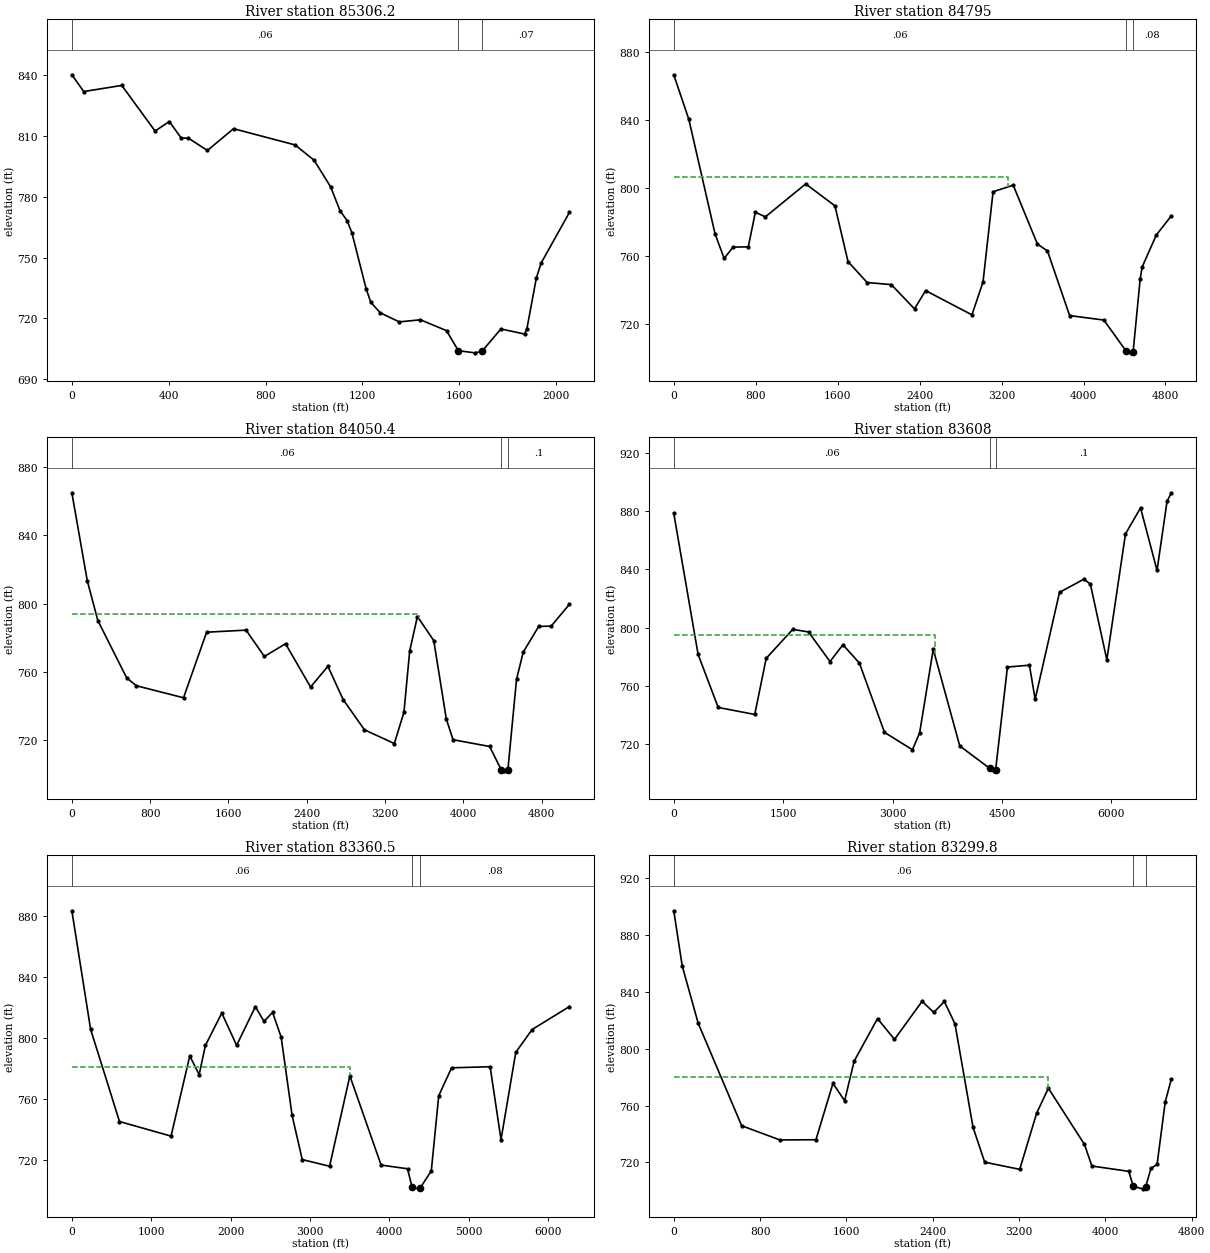
Type RM Length L Ch R = 1 ,85306.2 ,510.8,511.3,511.7
XS GIS Cut Line= 3
     1581048.095      325962.213     1581771.245      325777.467
     1582640.976      324799.018
#Sta/Elev= 30
       0  840.25    49.1  831.97   206.2     835   343.7  812.47   402.6  817.18
   451.8  809.01   481.2  808.98   559.8  802.88   667.8  813.64   922.2  805.62
  1000.4  798.08  1068.8  784.97  1107.8  773.12  1137.2  768.22  1156.7  762.25
  1215.3  734.71  1234.8  727.94  1273.9  722.76  1352.1  718.28    1440  719.31
  1547.5  713.96  1596.3  704.06  1664.7     703    1694  703.75  1772.2   714.8
  1869.9  712.27  1879.6  714.88  1918.7  739.97  1938.3  747.29  2055.5  772.38
#Mann= 3 , 0 , 0
       0     .06       0  1596.3    .045       0    1694     .07       0
Bank Sta=1596.3,1694
XS Rating Curve= 0 ,0
Exp/Cntr=0.3,0.1

Type RM Length L Ch R = 1 ,84795   ,745.2,744.6,743.9
XS GIS Cut Line= 2
     1579748.905      328411.634      1583157.47      324950.928
#Sta/Elev= 30
       0  866.58   147.5   840.3   403.2  772.94   491.6  758.53   580.1  765.14
   727.6  765.29   796.5  785.63   894.8  782.96  1288.1  802.35  1573.3  789.44
  1701.1  756.62  1887.9  744.29  2123.9  743.06  2350.1  728.77  2458.2  739.56
  2910.5  725.26  3018.7  744.52    3117  797.72  3313.7  801.58  3549.7  766.94
    3648  762.87  3864.3  724.84  4198.6  722.19    4415     704  4464.1   702.9
  4483.8  703.38  4552.6  746.19  4572.3  753.47    4710   772.2  4857.4  783.59
#Mann= 3 , 0 , 0
       0     .06       0    4415    .045       0  4483.8     .08       0
#XS Ineff= 2 , 0
         3263.95  806.53
Permanent Ineff=
       F       F
Bank Sta=4415,4483.8
XS Rating Curve= 0 ,0
Exp/Cntr=0.3,0.1

Type RM Length L Ch R = 1 ,84050.4 ,440.9,442.4,443.7
XS GIS Cut Line= 2
     1580408.627      328974.134     1583873.615      325254.747
#Sta/Elev= 30
       0  864.86   157.3  813.43   265.5  790.11   560.4  756.55   658.8     752
  1140.6  744.95  1376.5  783.31  1779.6  784.51  1966.5  769.11  2182.8  776.55
  2438.4  751.23  2615.4  763.35  2772.7  743.75    2989  726.21  3293.8  718.19
  3392.2  736.43  3451.1  772.35  3529.8  792.49    3697  778.39  3824.8  732.57
  3893.6  720.43  4267.2  716.46  4385.2  702.93  4414.7  702.21    4454  702.76
  4542.5  755.84  4611.4  771.72  4768.7  786.68  4896.5  786.88  5083.3  799.67
#Mann= 3 , 0 , 0
       0     .06       0  4385.2    .045       0    4454      .1       0
#XS Ineff= 2 , 0
         3544.73  793.67
Permanent Ineff=
       F       F
Bank Sta=4385.2,4454
XS Rating Curve= 0 ,0
Exp/Cntr=0.3,0.1

Type RM Length L Ch R = 1 ,83608   ,248.7,247.6,246.6
XS GIS Cut Line= 5
     1580568.349      329050.523     1583836.304      325954.699
     1583828.492      325834.908     1584344.702      325426.976
     1585887.504      325376.275
#Sta/Elev= 30
       0   878.4   334.2  781.64   609.4  745.35  1110.6  740.52  1267.9  779.02
  1631.6  798.83  1847.8  797.09  2142.6  776.79  2319.6  788.31  2545.6  775.74
  2889.6  728.25  3272.9  716.34  3371.2  727.87    3558   785.2  3921.6  718.96
  4334.4  703.53  4386.8   701.9  4413.1  702.46  4575.4  773.03  4876.9   774.3
  4955.4  750.92  5289.3   824.2  5623.6  833.23  5712.1  829.92  5938.2  778.03
  6193.9  864.24  6400.4  882.08  6626.5  839.25  6764.1  886.67  6823.1  892.44
#Mann= 3 , 0 , 0
       0     .06       0  4334.4    .045       0  4413.1      .1       0
#XS Ineff= 2 , 0
          3577.5  795.15
Permanent Ineff=
       F       F
Bank Sta=4334.4,4413.1
XS Rating Curve= 0 ,0
Exp/Cntr=0.3,0.1

Type RM Length L Ch R = 1 ,83360.5 ,60.8,60.7,60.8
XS GIS Cut Line= 6
     1580651.683      329106.078     1583592.381       326552.79
     1583988.214      326103.137     1584163.436      326129.996
     1584515.936      326031.511     1585735.595      326144.504
#Sta/Elev= 30
       0  883.33     236  805.81   599.9  745.45    1249  735.91    1485  788.37
    1603  776.13  1681.7  795.24  1888.2  816.41  2075.1  795.28  2311.1  820.59
  2419.3  810.98  2527.5  816.85  2635.7  800.71  2773.3  749.57  2901.2  720.56
  3245.4  716.21  3501.1   775.3  3894.5  716.97  4226.9  714.55  4285.6  702.35
  4373.6  701.42  4383.4  701.66  4526.7  713.21    4620   762.3  4781.9   780.6
  5267.4   781.3  5404.6  733.62  5590.7  790.75  5796.5  805.66  6266.9   820.7
#Mann= 3 , 0 , 0
       0     .06       0  4285.6    .045       0  4383.4     .08       0
#XS Ineff= 2 , 0
          3503.1  781.38
Permanent Ineff=
       F       F
Bank Sta=4285.6,4383.4
XS Rating Curve= 0 ,0
Exp/Cntr=0.3,0.1

Type RM Length L Ch R = 1 ,83299.8 ,188.5,189.8,190.8
XS GIS Cut Line= 5
     1580714.183       329154.69     1583628.839      326601.401
     1584002.103      326214.248     1584024.672      326151.748
     1584156.617      326162.165
#Sta/Elev= 30
       0  897.18    78.7  858.28   226.2  818.03   629.4  745.76   983.5  735.75
  1317.8   735.9  1475.2  775.59  1583.4  763.38  1671.9  791.28  1888.2  821.24
  2045.6  806.58  2301.3  833.41  2409.5  825.59  2507.8  833.28  2606.2  817.47
  2773.4  744.64  2881.6  720.09  3206.1  715.04  3363.4  754.71  3471.6  772.18
    3806  732.61  3874.9  717.38  4217.1  713.63  4257.9703.0952  4344.2  701.31
  4373.5  702.83  4422.1  715.71  4479.1  718.52  4554.7  762.65  4611.4  778.72
#Mann= 3 , 0 , 0
       0     .06       0  4257.9    .045       0  4373.5     .08       0
#XS Ineff= 2 , 0
         3467.67  780.36
Permanent Ineff=
       F       F
Bank Sta=4257.9,4373.5
XS Rating Curve= 0 ,0
Exp/Cntr=0.3,0.1

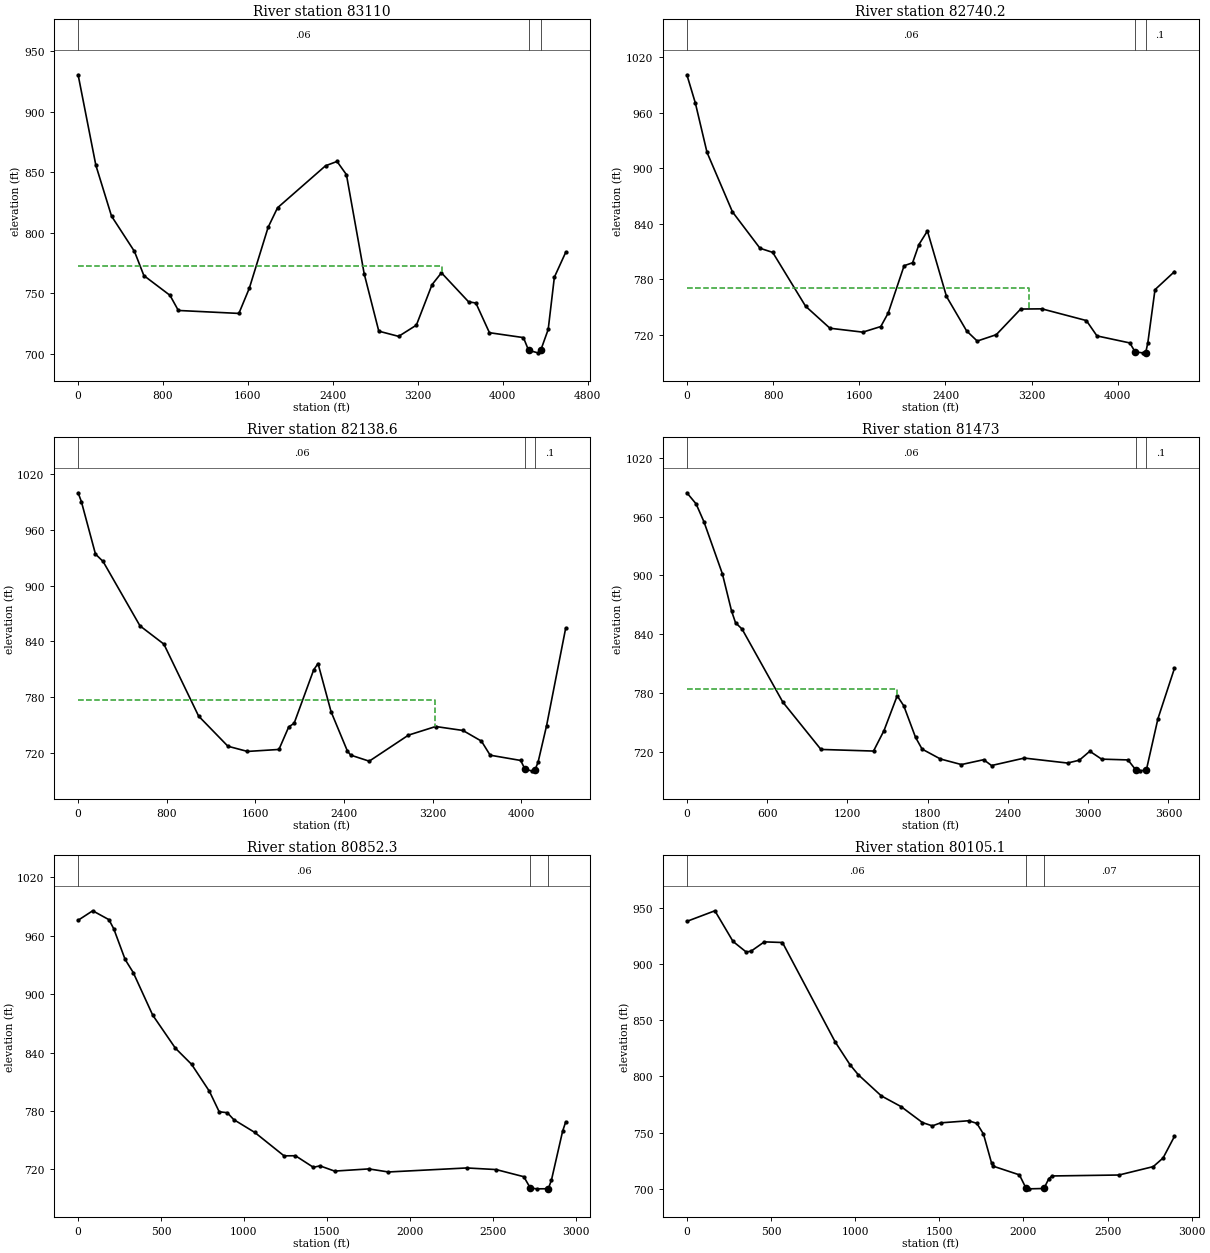
Type RM Length L Ch R = 1 ,83110   ,368.4,369.9,371.1
XS GIS Cut Line= 3
     1580811.405      329251.912     1583738.214      326726.401
     1584269.464      326228.137
#Sta/Elev= 30
       0  930.48   167.2  855.77   314.8   813.8   531.2  784.58   619.7  764.67
   865.6  748.39   944.3  735.89  1514.8  733.44  1613.2  754.26  1790.3  804.56
  1878.8  820.65  2331.3  855.36  2439.5  858.92    2528  848.04  2695.2  766.27
    2833   718.8  3019.8   714.5  3187.1  723.76  3334.6  757.18  3423.2  766.99
  3678.9  743.04  3747.8  742.02  3875.5  717.53    4196  713.48  4244.5  702.96
    4332   700.9  4361.1  703.59  4429.1  720.21  4487.3  763.38  4594.2  783.92
#Mann= 3 , 0 , 0
       0     .06       0  4244.5    .045       0  4361.1      .1       0
#XS Ineff= 2 , 0
         3432.24  772.39
Permanent Ineff=
       F       F
Bank Sta=4244.5,4361.1
XS Rating Curve= 0 ,0
Exp/Cntr=0.3,0.1

Type RM Length L Ch R = 1 ,82740.2 ,595.5,601.5,607.5
XS GIS Cut Line= 3
      1581054.46       329404.69     1584344.117      326669.109
     1584550.714      326532.824
#Sta/Elev= 30
       0 1000.74    78.7  970.24   186.9  917.07   422.9  852.93   678.6  813.68
   796.7  809.21  1101.6   751.2  1327.8  727.44  1632.7  723.21  1799.9  729.26
  1868.8  743.85  2016.3  794.84    2095  798.03    2154  817.69  2232.7  832.32
  2409.7  761.68  2596.6  724.54  2694.9   713.6    2872  720.49  3098.2  748.12
  3294.9  748.34    3708  735.71  3806.4  719.16  4111.3  711.58  4160.4  701.93
  4229.3   700.9  4258.8  701.12  4278.5  711.72  4345.1  769.04    4526   788.5
#Mann= 3 , 0 , 0
       0     .06       0  4160.4    .045       0  4258.8      .1       0
#XS Ineff= 2 , 0
         3179.81  770.98
Permanent Ineff=
       F       F
Bank Sta=4160.4,4258.8
XS Rating Curve= 0 ,0
Exp/Cntr=0.3,0.1

Type RM Length L Ch R = 1 ,82138.6 ,663.3,665.7,668.3
XS GIS Cut Line= 4
     1581137.794      329411.634     1582870.041      328015.605
     1584615.124      327219.109     1584840.384      327091.071
#Sta/Elev= 30
       0 1000.01    29.4  990.54   156.8  933.96   225.4  926.03   558.6  856.67
   774.3     837  1087.9  759.47  1352.5     727  1528.9   721.4  1813.1  723.54
  1901.3  747.78  1950.3  751.75  2126.8  809.27    2166  816.08  2283.8  764.16
  2431.4  721.75  2460.9  717.44  2628.1   710.9  2982.2  738.96  3228.2  748.24
  3474.1  743.99  3641.3  732.49    3720  717.35  3995.5  711.68  4034.8  702.13
  4093.8   700.5  4123.4  701.14  4152.6  709.83  4229.4  749.19  4402.1  854.41
#Mann= 3 , 0 , 0
       0     .06       0  4034.8    .045       0  4123.4      .1       0
#XS Ineff= 2 , 0
         3224.09  776.79
Permanent Ineff=
       F       F
Bank Sta=4034.8,4123.4
XS Rating Curve= 0 ,0
Exp/Cntr=0.3,0.1

Type RM Length L Ch R = 1 ,81473   ,616.4,620.7,624
XS GIS Cut Line= 5
     1581811.405      329244.967     1583007.256       328179.52
     1584367.294      328004.699     1584825.193       327854.96
     1585011.825      327815.897
#Sta/Elev= 30
       0  984.39    68.8  973.08   127.7  954.74   265.3   901.7   334.1  863.61
   363.6   851.7   412.7  845.19   717.3  770.62  1002.2  722.29  1395.3  720.64
  1473.9  741.62  1572.2  777.03  1621.2  766.94  1709.4  734.65  1758.4  722.65
  1895.5  712.54  2052.2  706.85  2218.7  711.81  2277.5  705.86  2522.3  713.48
  2845.5  708.41  2933.7  711.29  3012.2  720.44  3100.7  712.39  3297.3  711.59
  3356.3  701.35  3385.8  700.44    3435  701.34  3521.4   753.6  3645.3  805.24
#Mann= 3 , 0 , 0
       0     .06       0  3356.3    .045       0    3435      .1       0
#XS Ineff= 2 , 0
         1573.07  784.18
Permanent Ineff=
       F       F
Bank Sta=3356.3,3435
XS Rating Curve= 0 ,0
Exp/Cntr=0.3,0.1

Type RM Length L Ch R = 1 ,80852.3 ,751.7,747.2,743.4
XS GIS Cut Line= 4
     1582207.238      329300.523     1583311.653       328711.93
     1584888.127       328479.96     1584970.593      328432.217
#Sta/Elev= 30
       0  975.97      88  985.72   185.8  976.59   215.1  967.15   283.5   935.7
   332.4  922.26   449.8  878.49   586.6  844.51   684.4  827.91   791.9  800.16
   850.6  779.22   899.5  778.22   938.6  771.14  1065.7  757.91  1241.7   733.9
  1310.5  734.01  1418.7  722.11    1458  723.64  1546.6  718.23  1753.1  720.48
  1871.1  717.33  2343.3  721.46  2520.3  719.81  2687.5  712.47  2726.9  700.79
  2766.2     700  2835.1  700.11  2854.4  709.18  2921.2  759.03  2940.2  768.88
#Mann= 3 , 0 , 0
       0     .06       0  2726.9    .045       0  2835.1      .1       0
Bank Sta=2726.9,2835.1
XS Rating Curve= 0 ,0
Exp/Cntr=0.3,0.1

Type RM Length L Ch R = 1 ,80105.1 ,434,428.1,421.1
XS GIS Cut Line= 4
     1582917.018      329453.026     1584712.346      329300.272
     1585115.992      329161.383     1585003.145      328501.661
#Sta/Elev= 30
       0  937.75   166.5  947.16   274.2  919.92   352.5  910.52   381.9   911.3
   460.2  919.53     568  918.96   881.3   830.6   969.4  810.36  1018.4  801.48
  1155.5  782.63    1273   773.1  1400.3  758.88  1459.1  755.96    1508  758.65
  1674.5  760.52  1723.5  758.19  1762.6  748.72  1811.5  722.54  1821.2  720.11
  1976.4  712.41  2015.2   700.7  2032.3     700    2122  700.31  2151.1  709.02
  2170.5  711.45  2568.2  712.29  2771.9  719.76  2830.1  727.41    2898  746.67
#Mann= 3 , 0 , 0
       0     .06       0  2015.2    .045       0    2122     .07       0
Bank Sta=2015.2,2122
XS Rating Curve= 0 ,0
Exp/Cntr=0.3,0.1

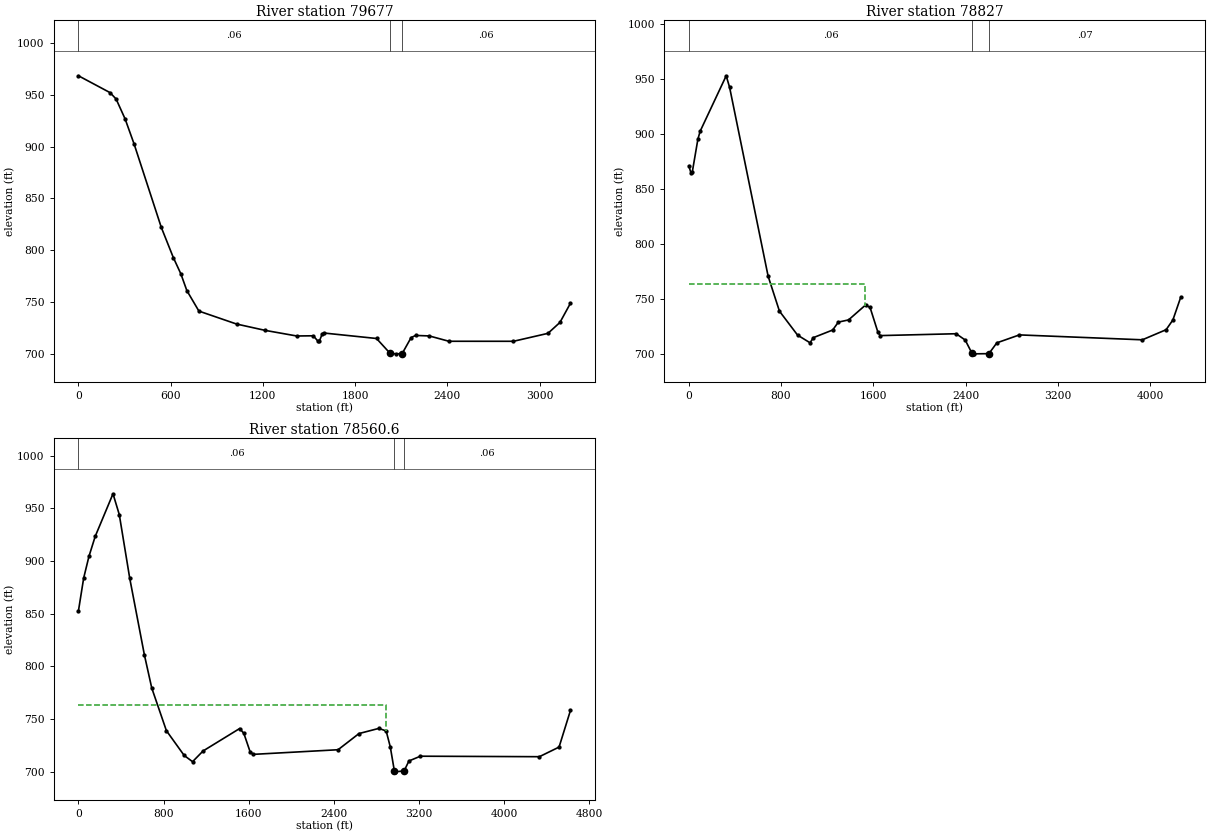
Type RM Length L Ch R = 1 ,79677   ,885,850,814.8
XS GIS Cut Line= 5
     1583375.351      330432.192     1584979.707      329700.446
     1585337.346      329443.501     1585184.568      329214.335
      1585063.04      328502.529
#Sta/Elev= 30
       0  968.28   205.7  952.01   244.9  945.88   303.7   926.6   362.5  902.28
   538.8   822.1   617.2  792.92   666.2  777.21   705.3  761.02   783.7  741.24
  1028.6  728.76  1214.8  722.64  1420.5  717.22  1528.2  717.42  1557.6   712.3
  1567.4  712.28    1587  719.46  1596.8  720.09  1939.5  714.81  2027.6  700.49
  2066.7     700  2105.9  700.14  2164.6  715.71  2193.9  717.76  2282.4  717.28
  2410.3  712.13  2830.4  712.11  3054.9  719.77  3132.9   730.3  3201.2   748.8
#Mann= 3 , 0 , 0
       0     .06       0  2027.6    .045       0  2105.9     .06       0
Bank Sta=2027.6,2105.9
XS Rating Curve= 0 ,0
Exp/Cntr=0.3,0.1

Type RM Length L Ch R = 1 ,78827   ,289.4,266.4,243.5
XS GIS Cut Line= 5
     1584097.574      331661.359     1585915.942      330222.378
     1585629.013       329801.14     1585215.818      329172.668
     1585122.068      328492.113
#Sta/Elev= 30
       0  871.05    19.6  864.08    29.5  864.97    78.6  895.18    98.3  902.44
   324.2  952.86   353.7  942.34   687.8  770.63   786.1  738.82   943.3  717.04
  1051.4  710.06  1080.8  714.76  1247.9  721.67    1297  728.85  1385.4  730.85
  1532.8  744.38  1572.1   742.2  1640.9  719.46  1660.5  716.59  2318.9  718.28
  2397.3  712.57  2456.1  700.52  2475.7     700  2603.1  700.17  2671.7     710
  2867.6  717.22    3934  712.76  4140.1  721.94    4199  730.81  4267.7  751.72
#Mann= 3 , 0 , 0
       0     .06       0  2456.1    .045       0  2603.1     .07       0
#XS Ineff= 2 , 0
          1527.9   763.9
Permanent Ineff=
       F       F
Bank Sta=2456.1,2603.1
XS Rating Curve= 0 ,0
Exp/Cntr=0.3,0.1

Type RM Length L Ch R = 1 ,78560.6 ,1096,1121.9,1147.6
XS GIS Cut Line= 6
     1584148.427       331733.35     1586087.918      330188.435
      1585946.98      329800.727     1585684.568      329808.085
     1585233.179      329162.251      1585156.79      328485.168
#Sta/Elev= 30
       0  852.84    49.2  883.99    98.4  904.39   157.4  923.46   324.7  963.92
   383.8  944.15   482.1  883.63   619.9  810.92   688.8   779.6   826.5  739.08
   993.8  715.54  1072.5  709.63  1170.9  719.78  1515.3  741.12  1554.7  736.46
  1613.7  718.92  1643.2  716.59  2440.2  720.98  2636.8  736.34  2823.4  741.24
  2892.1   738.8    2931  723.65  2969.9  700.45  2979.6     700  3061.2700.9337
    3106  710.32  3213.6  714.84  4332.1  714.37  4517.1   723.5  4624.1  758.23
#Mann= 3 , 0 , 0
       0     .06       0  2969.9    .045       0  3061.2     .06       0
#XS Ineff= 2 , 0
         2887.51   763.9
Permanent Ineff=
       F       F
Bank Sta=2969.9,3061.2
XS Rating Curve= 0 ,0
Exp/Cntr=0.3,0.1