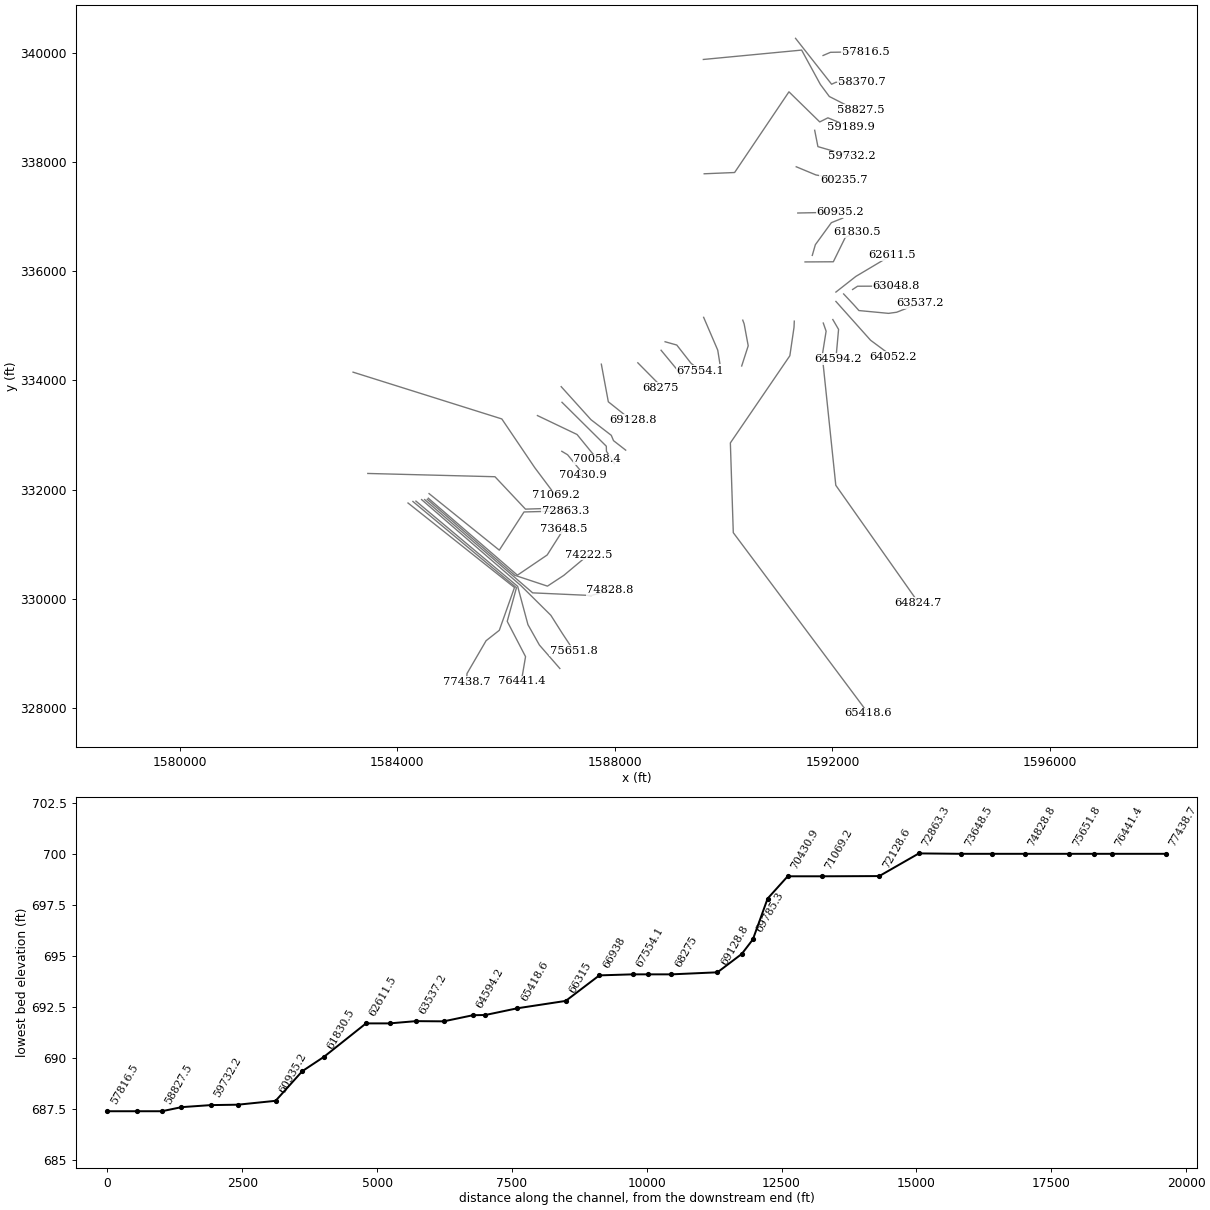
HEC-RAS study MDISLCRK_C.prj: MDISLCRK_C

--- MDISLCRK_C.g01 (geometry) --- (continued)

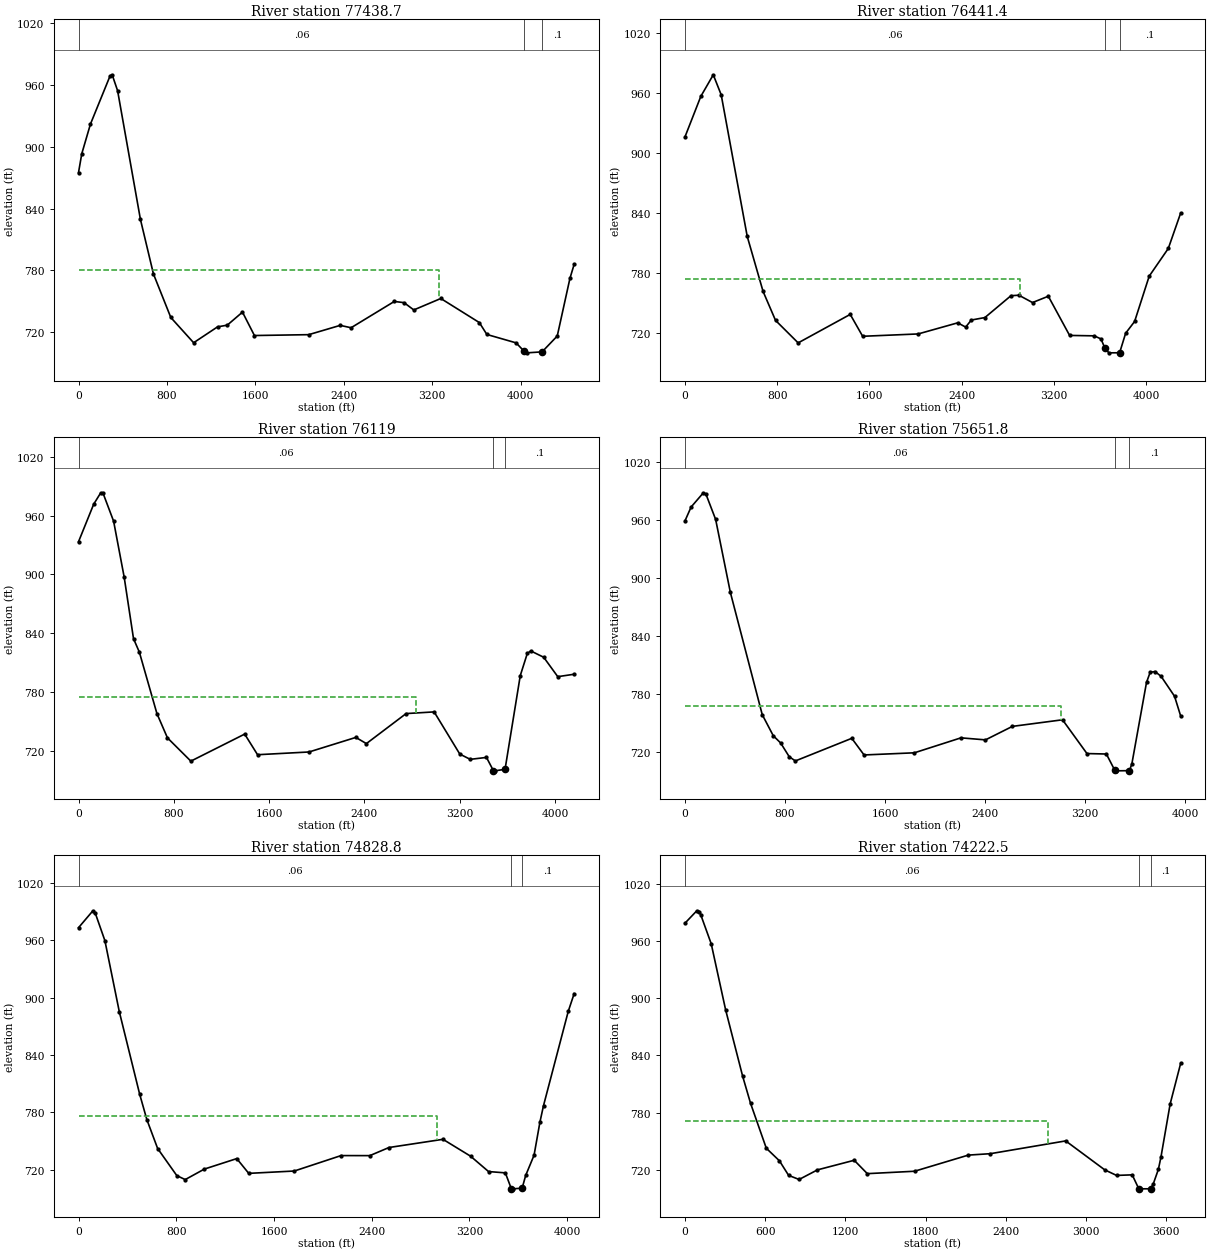
Type RM Length L Ch R = 1 ,77438.7 ,975.9,997.2,1018.5
XS GIS Cut Line= 6
     1584197.038      331754.183     1586154.526      330205.873
      1585875.54      329422.668     1585632.485      329231.696
      1585281.79      328631.001     1585271.374      328478.224
#Sta/Elev= 30
       0  874.95    29.5  893.24   108.1  922.04     285  968.63   304.6  969.87
   353.7  954.42   560.1  829.59     678  776.58   835.2  734.31  1041.6   709.8
  1257.7  725.19  1346.2  726.89  1483.7  739.52  1591.8   716.8  2083.1  717.64
  2368.1  726.66  2466.3  724.35  2857.7  749.88  2945.7  748.71  3033.8  741.64
  3278.3  752.74  3626.7   729.4  3695.1  717.83  3959.6  709.68  4033.9701.3457
  4057.6     700  4194.7  700.94  4331.9  716.31  4446.7  772.27    4485  785.95
#Mann= 3 , 0 , 0
       0     .06       0  4033.9    .045       0  4194.7      .1       0
#XS Ineff= 2 , 0
         3263.95  780.36
Permanent Ineff=
       F       F
Bank Sta=4033.9,4194.7
XS Rating Curve= 0 ,0
Exp/Cntr=0.3,0.1

Type RM Length L Ch R = 1 ,76441.4 ,321.7,322.5,323.2
XS GIS Cut Line= 5
     1584287.316      331781.961     1586190.883      330202.235
     1586021.276      329586.395     1586358.179      328940.029
     1586281.023      328489.065
#Sta/Elev= 30
       0  916.16   137.4  956.71   245.4  978.32   314.1  958.29   539.9  816.54
   677.3  761.49   785.3   732.5   981.6  709.96  1433.2  738.47  1541.1  716.57
  2022.1  718.91  2365.7  730.04  2434.4  725.77  2483.5  732.83  2601.4  735.32
  2827.5   757.2  2896.2  757.66  3014.2  750.33  3151.3  756.66    3336  717.43
  3549.8  717.01  3608.1  713.91  3639.8705.2898  3676.1     700  3769.8700.0703
  3821.9  719.63  3899.8   731.4  4026.3  776.76  4191.8  804.46  4298.9   839.8
#Mann= 3 , 0 , 0
       0     .06       0  3639.8    .045       0  3769.8      .1       0
#XS Ineff= 2 , 0
         2905.23  773.47
Permanent Ineff=
       F       F
Bank Sta=3639.8,3769.8
XS Rating Curve= 0 ,0
Exp/Cntr=0.3,0.1

Type RM Length L Ch R = 1 ,76119   ,466.1,467.2,468.4
XS GIS Cut Line= 5
     1584342.872      331788.905     1586213.181      330227.013
     1586402.161      329526.111     1586612.664      329152.848
     1586988.488       328723.44
#Sta/Elev= 30
       0  933.29   127.7  971.59   186.7  983.16   206.3  982.64   294.8  954.19
   383.2  897.44   461.8   834.6   510.9  820.86   658.3  758.35   746.7  733.59
   943.2  709.87  1395.2  737.42  1503.3  716.42  1935.6  719.21  2328.6  734.04
  2417.1  727.73  2750.6  758.31  2986.1  760.02  3201.6  717.06  3289.2   711.7
  3425.6  713.67    3484  700.08  3493.8     700  3581.4  701.51  3709.2  796.94
  3768.3  819.56  3797.8  822.09    3906  815.66  4024.1   795.9  4161.8  798.37
#Mann= 3 , 0 , 0
       0     .06       0    3484    .045       0  3581.4      .1       0
#XS Ineff= 2 , 0
         2834.37     775
Permanent Ineff=
       F       F
Bank Sta=3484,3581.4
XS Rating Curve= 0 ,0
Exp/Cntr=0.3,0.1

Type RM Length L Ch R = 1 ,75651.8 ,801.2,822.9,844.4
XS GIS Cut Line= 5
     1584447.038      331816.683     1586273.427      330240.294
     1586823.168      329697.552     1587031.501      329369.861
      1587247.39      329045.258
#Sta/Elev= 30
       0  959.25      49  973.62   147.1   988.4   166.7  987.31   245.2  960.75
   362.9  885.06   617.9  758.25   706.1  736.39     765   728.9   833.6  714.64
   882.7  710.27  1333.8  733.73  1431.9  716.47    1834   718.7  2206.7  734.22
  2402.8  732.12    2618  746.11  3018.9  752.95  3214.2  717.93  3369.6  717.45
  3437.5  700.38  3447.2     700    3554   700.2  3573.4  707.27  3690.4  791.68
  3719.6  802.18  3758.6  802.99  3807.3  797.98  3914.6  777.36  3963.3  757.02
#Mann= 3 , 0 , 0
       0     .06       0  3437.5    .045       0    3554      .1       0
#XS Ineff= 2 , 0
         3007.97  767.73
Permanent Ineff=
       F       F
Bank Sta=3437.5,3554
XS Rating Curve= 0 ,0
Exp/Cntr=0.3,0.1

Type RM Length L Ch R = 1 ,74828.8 ,589.6,606.3,622.9
XS GIS Cut Line= 4
     1584502.594      331816.683     1586488.705       330108.35
     1587567.525      330059.966     1587911.452      330156.369
#Sta/Elev= 30
       0  973.01   117.7   990.7   137.4  988.13   215.9   959.5   333.6  885.37
   500.4  799.01   559.3  772.42   647.6  742.17   804.6  713.83   873.2  709.67
  1030.2  720.67  1295.2  731.61  1393.3  716.18  1766.1  718.63  2148.8  734.77
  2384.3  734.72  2541.2  743.21    2983  751.77  3208.8  734.14    3356  718.07
  3493.5   716.7  3542.6  700.09  3552.4     700  3630.9  700.69  3660.4  714.14
  3728.6  735.18  3776.9     770  3805.8  786.96  4008.6  885.65  4056.8  904.11
#Mann= 3 , 0 , 0
       0     .06       0  3542.6    .045       0  3630.9      .1       0
#XS Ineff= 2 , 0
         2936.23  775.77
Permanent Ineff=
       F       F
Bank Sta=3542.6,3630.9
XS Rating Curve= 0 ,0
Exp/Cntr=0.3,0.1

Type RM Length L Ch R = 1 ,74222.5 ,567.1,574,581
XS GIS Cut Line= 5
      1584551.06      331821.313     1586161.748      330429.428
     1586760.743      330231.512     1587061.883      330428.889
     1587513.272      330804.323
#Sta/Elev= 30
       0  978.76    88.3  991.78   107.9  991.01   117.7  987.68   196.2  957.17
   304.1  887.75   431.6  818.02   490.5  789.71   608.2   742.6   706.3  729.41
     775  714.14   853.5  709.82   990.8  719.91  1265.5  729.98  1363.6  715.94
  1716.8  718.46    2119   735.4    2284  736.89  2847.2   750.3  3139.2  719.93
  3227.3  714.09  3344.7  714.68  3393.7  700.12  3403.4     700  3481.7  700.06
  3501.3  704.82  3540.4  720.44    3560  733.63  3628.5  789.12  3706.8  831.54
#Mann= 3 , 0 , 0
       0     .06       0  3393.7    .045       0  3481.7      .1       0
#XS Ineff= 2 , 0
         2717.45  770.79
Permanent Ineff=
       F       F
Bank Sta=3393.7,3481.7
XS Rating Curve= 0 ,0
Exp/Cntr=0.3,0.1

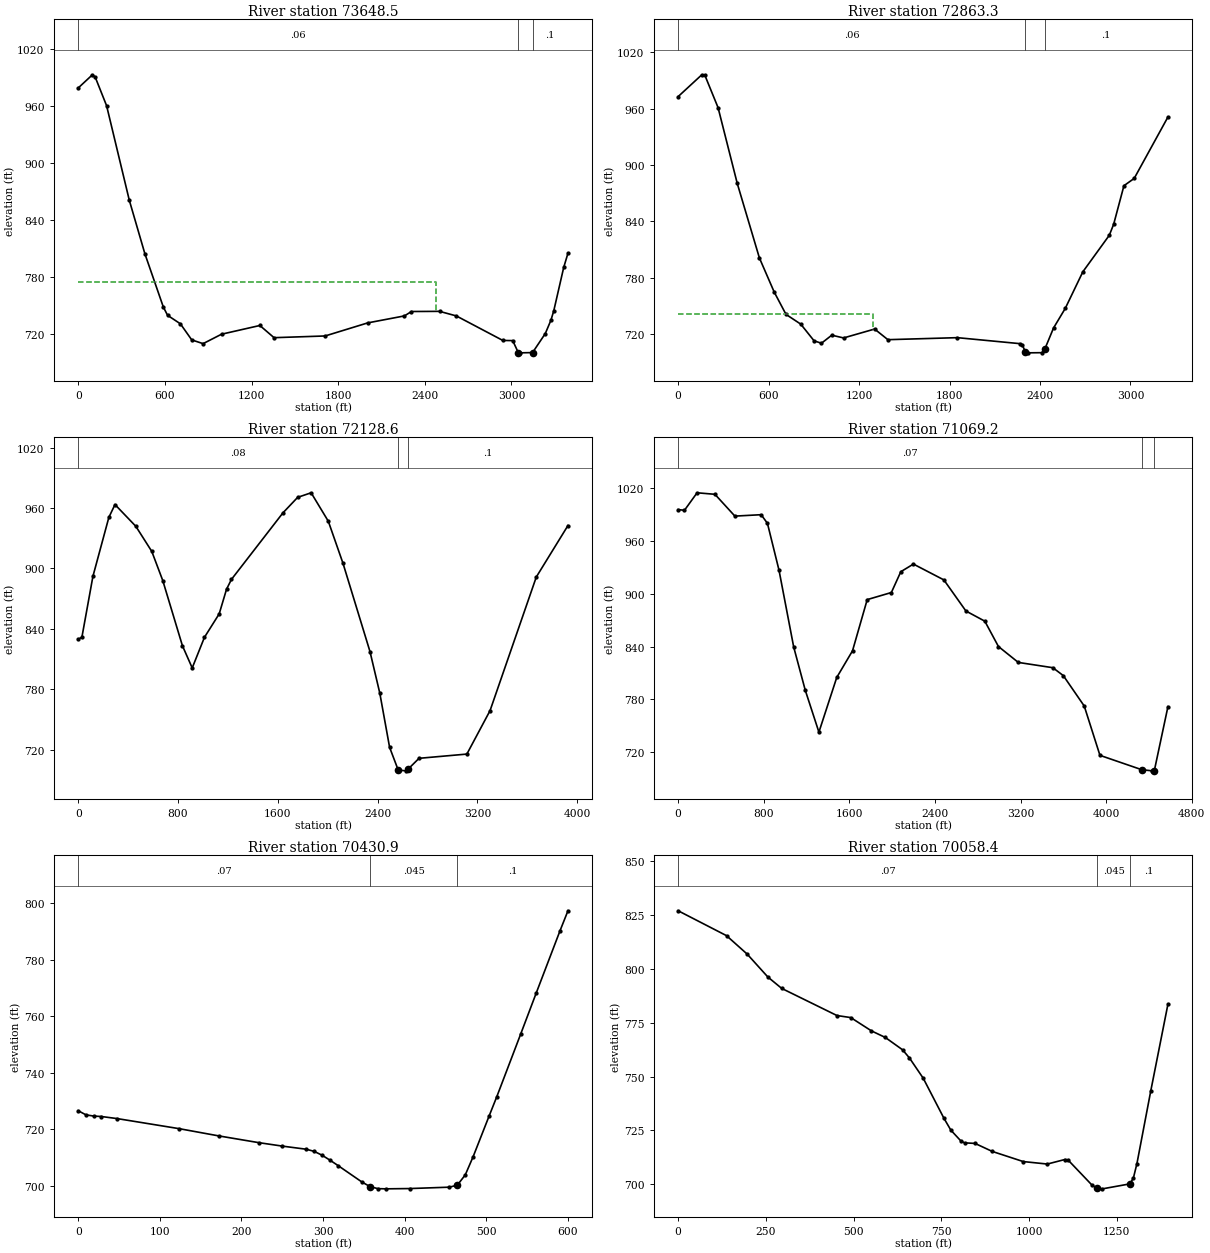
Type RM Length L Ch R = 1 ,73648.5 ,785.2,785.1,784.9
XS GIS Cut Line= 4
     1584569.796      331841.915     1586208.685      330432.192
     1586755.893      330802.153     1587061.883      331281.754
#Sta/Elev= 30
       0  979.41    98.3  993.32   117.9   990.8   196.5   960.7   353.8  860.92
   461.8  804.44   589.6  748.23     619  739.56   707.5  730.62   786.1  713.65
   864.7   709.7   992.4  719.65  1257.8  728.85    1356  715.99  1709.8   717.8
  2004.6  731.59  2258.9  738.96  2307.5  743.59  2501.8  743.77  2618.3  738.94
    2940  713.08  3008.7  712.89  3047.9  700.02  3057.7     700    3146  700.26
  3234.3  720.36  3273.5  734.51  3293.1  744.47  3361.8  790.13  3391.2  805.11
#Mann= 3 , 0 , 0
       0     .06       0  3047.9    .045       0    3146      .1       0
#XS Ineff= 2 , 0
         2480.07  774.62
Permanent Ineff=
       F       F
Bank Sta=3047.9,3146
XS Rating Curve= 0 ,0
Exp/Cntr=0.3,0.1

Type RM Length L Ch R = 1 ,72863.3 ,775.6,734.8,693.8
XS GIS Cut Line= 4
     1584583.974      331926.565     1585875.351      330890.526
     1586329.766      331590.192     1587088.314      331609.724
#Sta/Elev= 30
       0  972.85   156.7  996.02   176.3  995.77   264.5  961.08   391.9  880.32
   538.8  801.01   636.8  764.78   715.1  740.96   813.1  730.57   901.3  712.84
   950.3  710.22  1018.8  718.81  1097.2  715.88  1302.9  725.35  1391.1  714.03
  1851.9  716.18  2264.1  709.85  2283.8  708.01  2303.4  700.97    2323  700.02
  2411.4  700.19    2431  703.63  2489.9  726.48  2567.7  747.36  2684.4  786.31
  2859.6  825.13  2888.7  836.88  2956.8  877.92  3024.9  885.69  3248.7  951.05
#Mann= 3 , 0 , 0
       0     .06       0  2303.4    .045       0    2431      .1       0
#XS Ineff= 2 , 0
         1289.64  741.33
Permanent Ineff=
       F       F
Bank Sta=2303.4,2431
XS Rating Curve= 0 ,0
Exp/Cntr=0.3,0.1

Type RM Length L Ch R = 1 ,72128.6 ,1061.5,1059.4,1057
XS GIS Cut Line= 4
     1583457.889      332295.416     1585796.118      332235.447
     1586356.588      331641.997     1587127.377      331666.148
#Sta/Elev= 30
       0  829.64    29.5   831.6   117.9  892.08   245.7  950.68   294.8   963.4
   461.9  941.79   589.7  916.89   678.1  887.85   835.4  823.19     914  801.11
  1012.3   831.6  1130.2  854.82  1189.2  879.33  1228.5  889.07  1641.2  955.13
  1759.2  970.55  1867.3   975.1  2004.9  946.86  2122.8  905.04    2339  817.44
  2417.7  776.19  2496.4  722.27  2565.2  699.75  2624.2  698.91  2643.9  700.51
  2732.4  711.35  3115.9  715.56  3301.7   758.7  3672.6  891.46  3926.4  942.56
#Mann= 3 , 0 , 0
       0     .08       0  2565.2    .045       0  2643.9      .1       0
Bank Sta=2565.2,2643.9
XS Rating Curve= 0 ,0
Exp/Cntr=0.3,0.1

Type RM Length L Ch R = 1 ,71069.2 ,637.5,638.3,639.1
XS GIS Cut Line= 4
     1583186.622      334150.885     1585921.663      333294.132
     1586525.859      332403.716     1586907.803      331895.903
#Sta/Elev= 30
       0  995.79    58.9  995.06   176.7 1014.94   343.5 1013.21     530  988.42
   775.4  990.03   834.3   980.2   942.3  926.99  1079.7  839.61  1187.7  790.55
  1315.3  742.89  1482.1  805.04  1629.4  835.32  1766.8  893.52  1992.5  901.57
  2080.9  925.23  2198.6   933.9  2483.3  915.92  2689.4  880.57  2866.1     869
  2993.3  840.22  3179.1  822.12  3501.9  816.12  3599.8  807.12  3795.4  772.55
  3942.2   716.5  4333.2  700.17  4430.9   698.9  4450.5  699.18  4577.6  771.84
#Mann= 3 , 0 , 0
       0     .07       0  4333.2    .045       0  4450.5      .1       0
Bank Sta=4333.2,4450.5
XS Rating Curve= 0 ,0
Exp/Cntr=0.3,0.1

Type RM Length L Ch R = 1 ,70430.9 ,372.3,372.5,372.5
XS GIS Cut Line= 4
     1587024.991      332701.025     1587131.327      332638.091
     1587346.171      332373.334     1587417.786      332258.316
#Sta/Elev= 29
       0  726.53     9.5  725.07      19  724.64    28.5  724.48    47.5  723.76
   123.6  720.19   172.3  717.62     221  715.25   250.2  714.01   279.4  712.91
   289.2  712.14   298.9  710.77   308.7  708.99   318.4  707.12   347.6  701.31
   357.4  699.71   367.1  698.97   376.8   698.9   406.1     699   454.8  699.49
   464.5  700.22   474.2  703.84   483.9  710.33   503.2  724.52   512.9  731.56
     542  753.59   561.3   768.3   590.3  790.22     600  797.26
#Mann= 3 , 0 , 0
       0     .07       0   357.4    .045       0   464.5      .1       0
Bank Sta=357.4,464.5
XS Rating Curve= 0 ,0
Exp/Cntr=0.3,0.1

Type RM Length L Ch R = 1 ,70058.4 ,270.7,273.2,275.5
XS GIS Cut Line= 3
      1586576.74      333355.804     1587304.939      333009.184
     1587678.202      332553.455
#Sta/Elev= 30
       0  827.05   137.7  815.49   196.7   806.9   255.7  796.24   295.1  790.96
   452.4  778.36   491.8  777.41   550.8  771.22   590.1  768.18   639.3  762.45
     659  758.64   698.3  749.21   757.3  730.61     777  725.09   806.5   719.9
   816.3  719.18   845.8  718.93   894.8  715.21   983.2  710.49  1051.9  709.33
    1101  711.41  1110.8  711.25  1179.6  699.48  1193.7698.0445    1209  697.81
  1287.6  700.13  1297.4  702.99  1307.2   709.5  1346.5  743.17  1395.6  783.64
#Mann= 3 , 0 , 0
       0     .07       0  1193.7    .045       0  1287.6      .1       0
Bank Sta=1193.7,1287.6
XS Rating Curve= 0 ,0
Exp/Cntr=0.3,0.1

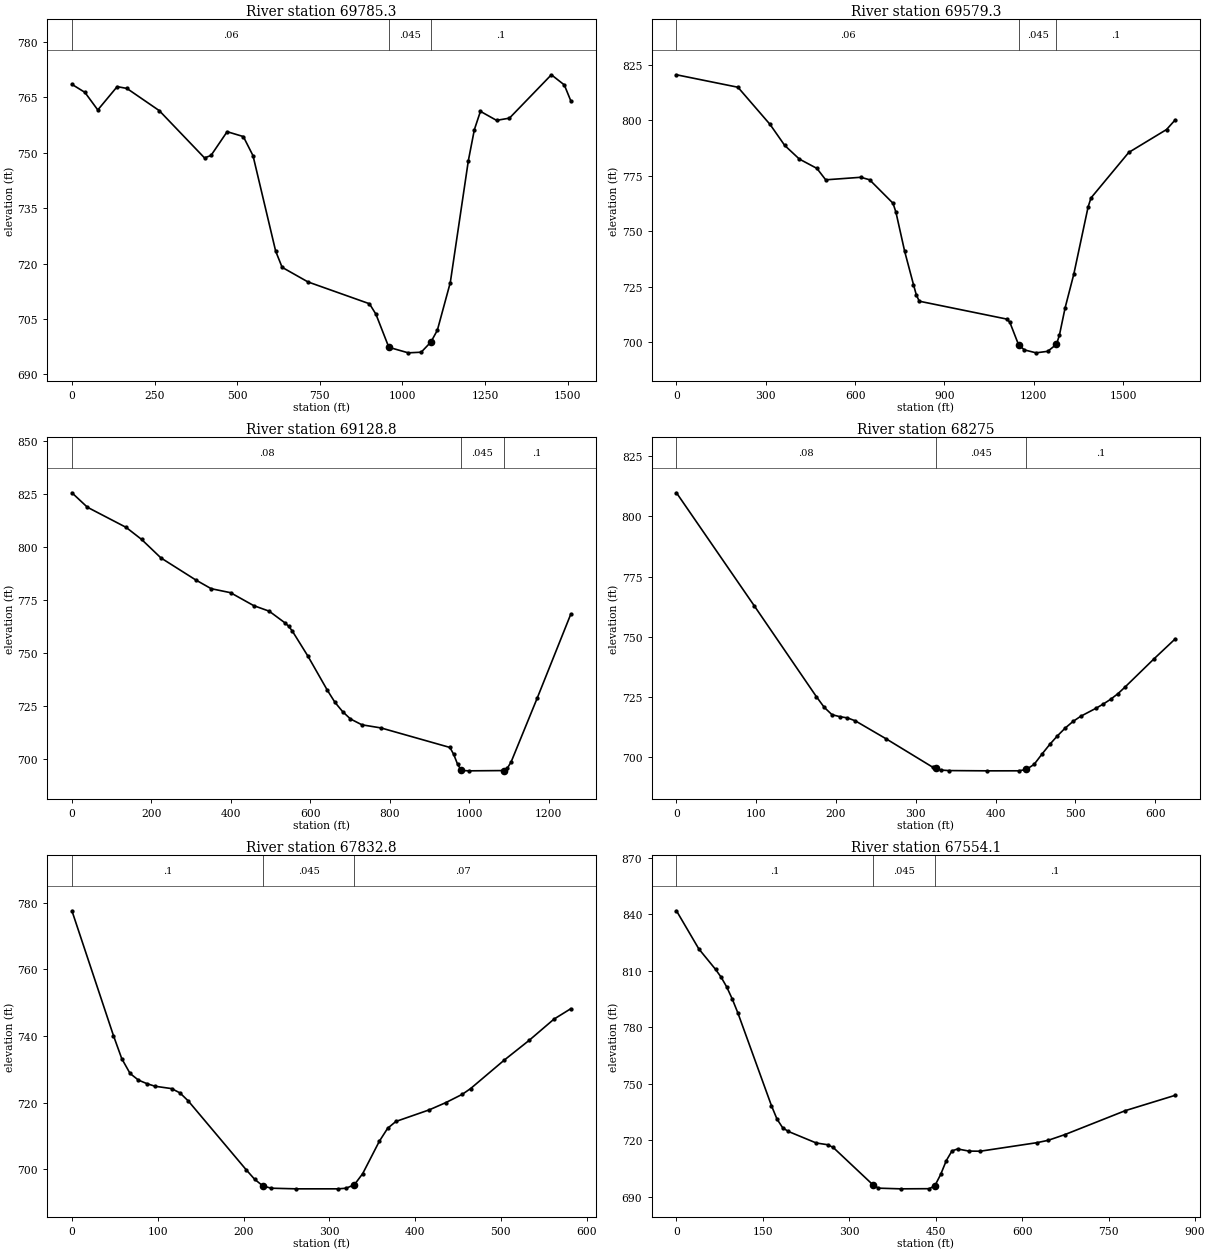
Type RM Length L Ch R = 1 ,69785.3 ,203,205.9,206.5
XS GIS Cut Line= 4
     1587028.129      333598.859     1587843.133      332794.341
     1587845.303      332703.195     1587992.873       332473.16
#Sta/Elev= 30
       0  768.56    39.2  766.39    78.3  761.62     137  767.94   166.4  767.45
   264.3  761.44   401.3  748.63   420.9  749.28   469.8  755.73   518.8  754.41
   548.1  749.23   616.6  723.38   636.2  718.98   714.5  715.02   900.5  709.11
   920.1  706.28   959.2  697.31    1018  695.81  1057.1  695.98  1086.5  698.74
    1106  701.93  1145.2  714.86  1199.9  747.91  1218.1   756.3  1236.4  761.24
  1285.2   758.8  1324.2   759.4  1451.1  771.15  1490.2  768.41  1509.7  764.14
#Mann= 3 , 0 , 0
       0     .06       0   959.2    .045       0  1086.5      .1       0
Bank Sta=959.2,1086.5
XS Rating Curve= 0 ,0
Exp/Cntr=0.3,0.1

Type RM Length L Ch R = 1 ,69579.3 ,450.7,450.5,452.2
XS GIS Cut Line= 5
     1587013.615      333885.102     1587561.015      333280.452
     1587934.279      332993.993     1587975.512      332896.337
     1588199.036      332722.726
#Sta/Elev= 30
       0  820.54   206.4  814.92   314.5  798.11   363.6  788.66   412.7  782.52
   471.7  778.31   501.2  773.15   619.1   774.3   648.6  773.18   727.2  762.59
     737   758.6   766.5  740.84     796   725.9   805.8  721.11   815.6  718.39
  1109.7  710.32  1119.5  708.92  1148.9  698.76  1168.5  696.42  1207.7   695.1
  1246.9  695.79  1276.3  698.95  1286.1  703.06  1305.4  715.48  1334.3  730.51
  1382.5  760.93  1392.2  764.98    1519  785.51  1645.9  795.84  1675.2  800.22
#Mann= 3 , 0 , 0
       0     .06       0  1148.9    .045       0  1276.3      .1       0
Bank Sta=1148.9,1276.3
XS Rating Curve= 0 ,0
Exp/Cntr=0.3,0.1

Type RM Length L Ch R = 1 ,69128.8 ,856.6,853.9,851.3
XS GIS Cut Line= 4
     1587751.463      334297.428     1587880.025      333608.143
     1588196.866      333356.407     1588324.904      333278.282
#Sta/Elev= 30
       0  825.65      39  818.81   136.3  809.31   175.3  803.62     224  794.87
   311.6  784.46   350.6  780.31   399.3  778.42   457.7   772.3   496.7  769.67
   535.6  764.26   545.4  762.62   555.1  760.22     594  748.47   642.7  732.42
   662.2  726.59   681.7  722.16   701.2  718.73   730.1  715.96   778.2  714.48
   951.7  705.25   961.3  701.93     971  697.29   980.6  694.37   999.9   694.2
  1086.6  694.33  1096.2  695.44  1105.8  698.43  1171.5  728.62  1255.8   768.2
#Mann= 3 , 0 , 0
       0     .08       0   980.6    .045       0  1086.6      .1       0
Bank Sta=980.6,1086.6
XS Rating Curve= 0 ,0
Exp/Cntr=0.3,0.1

Type RM Length L Ch R = 1 ,68275   ,444,442.1,440
XS GIS Cut Line= 3
      1588422.56      334322.118     1588793.654      333948.854
     1588837.057      333859.879
#Sta/Elev= 30
       0  809.87    97.5  762.83   175.4  724.99   185.2  720.56   194.9   717.5
   204.7  716.66   214.4  716.14   224.2  714.92   263.2  707.36   321.6  695.54
   325.7695.0756   331.4  694.43   341.2  694.21   389.9   694.1   428.9  694.11
   438.6  694.67   448.4   696.8   458.1  701.02   467.9  705.08   477.6  708.68
   487.4  711.93   497.1  714.65   506.8  716.82   526.3  720.22   535.3  721.96
   544.3   723.9   553.3  726.18   562.3  728.97   598.3  740.62   625.3  749.06
#Mann= 3 , 0 , 0
       0     .08       0   325.7    .045       0   438.6      .1       0
Bank Sta=325.7,438.6
XS Rating Curve= 0 ,0
Exp/Cntr=0.3,0.1

Type RM Length L Ch R = 1 ,67832.8 ,279.4,278.7,278.1
XS GIS Cut Line= 3
     1588850.077      334552.153     1589134.366      334209.271
      1589199.47      334089.914
#Sta/Elev= 30
       0   777.6    48.4  740.13    58.1  733.19    67.8  728.74    77.5  726.76
    87.1  725.72    96.8  724.91   116.2   724.2   125.9  722.91   135.6   720.5
   203.3  699.77     213  696.97   222.7  694.95   232.4  694.29   261.4   694.1
   309.8   694.1   319.5  694.28   329.2  695.33   338.9  698.66   358.3  708.38
     368  712.28   377.6  714.33   416.4  717.81   435.7  719.98   455.1   722.5
   464.8  724.23   503.7  732.71   532.8  738.66   561.9  745.07   581.4  748.18
#Mann= 3 , 0 , 0
       0      .1       0   222.7    .045       0   329.2     .07       0
Bank Sta=222.7,329.2
XS Rating Curve= 0 ,0
Exp/Cntr=0.3,0.1

Type RM Length L Ch R = 1 ,67554.1 ,621.9,616.1,610.3
XS GIS Cut Line= 4
     1588924.075      334707.946     1589138.706      334647.639
     1589399.123      334315.608     1589570.564      334176.719
#Sta/Elev= 30
       0  841.74    38.8   821.5    67.8  810.65    77.6  806.44    87.2   801.3
    96.9  794.85   106.6  787.48   164.8   738.3   174.5  731.12   184.2  726.58
   193.9  724.61   242.6  718.44   262.2  717.53     272  716.08   340.7   696.3
   350.5  694.46     389   694.1   438.8  694.18   448.6  695.85   458.5  701.74
   468.3  709.11   478.1  714.23   487.9  715.28   507.5  714.14   527.2  714.08
   625.3   718.6   644.9  719.85   673.7  722.86   779.2  735.65   865.6  743.77
#Mann= 3 , 0 , 0
       0      .1       0   340.7    .045       0   448.6      .1       0
Bank Sta=340.7,448.6
XS Rating Curve= 0 ,0
Exp/Cntr=0.3,0.1

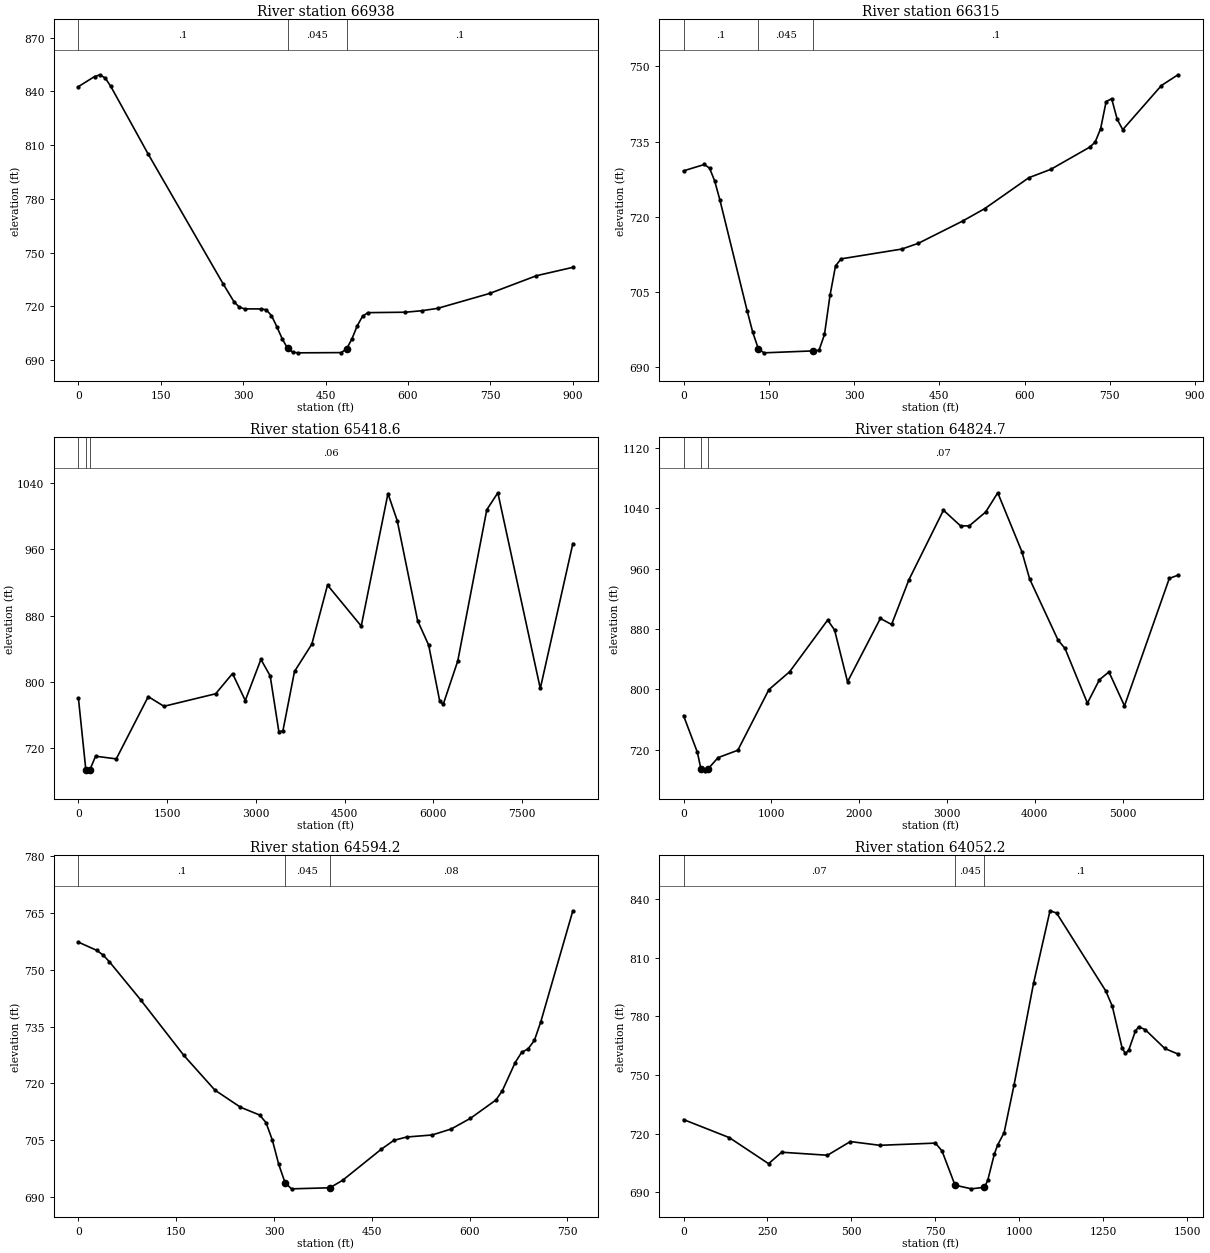
Type RM Length L Ch R = 1 ,66938   ,628.1,623,618
XS GIS Cut Line= 3
     1589632.626      335154.995     1589891.744      334554.323
     1589930.807      334311.268
#Sta/Elev= 30
       0  842.65    29.3  848.25    39.1  849.24    48.8  847.41    58.6  842.91
   126.9  805.04   263.6  732.49   283.2  722.61   292.9  719.55   302.7  718.58
     332  718.56   341.7  718.12   351.5  714.88   361.3  708.68     371  701.92
   380.8  696.62   390.6  694.36   400.3  694.05   478.4  694.18   488.2   696.2
     498  701.78   507.7  709.12   517.5  714.53   527.2  716.48   595.6  716.72
   624.9  717.54   654.2  718.88   748.9   727.2   834.1  737.09   900.4  741.77
#Mann= 3 , 0 , 0
       0      .1       0   380.8    .045       0   488.2      .1       0
Bank Sta=380.8,488.2
XS Rating Curve= 0 ,0
Exp/Cntr=0.3,0.1

Type RM Length L Ch R = 1 ,66315   ,903.8,896.4,888.9
XS GIS Cut Line= 4
     1590351.814      335103.368     1590377.421      335034.792
     1590452.074       334633.75     1590332.282      334263.959
#Sta/Elev= 30
       0  729.15    36.6  730.42    45.8  729.69    54.9   727.1      64  723.32
     112  701.17   121.8  696.89   131.5  693.66   141.2   692.8   228.6  693.19
   238.3  693.29     248  696.48   257.7  704.28   267.4  710.16   277.2  711.57
     384  713.53   413.1  714.68   490.8  719.11   529.7  721.59   607.5  727.78
   646.3  729.46   714.4  733.87   724.1  734.87   733.8  737.57   743.5  742.99
   753.2  743.56     763  739.44   772.7  737.38   840.7  746.19   869.8  748.34
#Mann= 3 , 0 , 0
       0      .1       0   131.5    .045       0   228.6      .1       0
Bank Sta=131.5,228.6
XS Rating Curve= 0 ,0
Exp/Cntr=0.3,0.1

Type RM Length L Ch R = 1 ,65418.6 ,594.2,593.9,593.6
XS GIS Cut Line= 6
     1591299.296      335085.139     1591294.088      334970.556
     1591217.699      334451.459     1590123.882      332854.623
     1590177.697      331210.807     1592659.278      327900.885
#Sta/Elev= 30
       0  779.81   124.4  693.99   143.8  692.44   192.4  693.56   289.6  710.12
   639.4  706.88  1179.8   782.1    1445  770.39  2319.5  785.53  2604.3  809.97
  2819.7  777.35    3084     827  3240.6  807.13  3387.5  739.74    3456  740.77
  3651.8  812.45  3945.5  845.57  4209.8  916.73  4779.7  867.27  5231.7  1027.3
    5389  994.32  5732.9   873.8  5919.6  844.21  6106.3  776.69  6165.2  772.68
  6410.9  825.01  6902.2 1007.76  7088.9 1028.24  7806.2  791.92  8356.5  966.89
#Mann= 3 , 0 , 0
       0      .1       0   124.4    .045       0   192.4     .06       0
Bank Sta=124.4,192.4
XS Rating Curve= 0 ,0
Exp/Cntr=0.3,0.1

Type RM Length L Ch R = 1 ,64824.7 ,228.9,230.4,232
XS GIS Cut Line= 5
     1591832.282      335050.417     1591884.366      334901.111
     1591813.185      334456.667     1592062.477      332078.401
     1593581.587      329929.964
#Sta/Elev= 30
       0  765.31   158.1   716.5   197.3  695.03   246.2  692.11   275.6  694.17
     393  709.59   618.1  719.38   972.3  799.72  1208.5  823.37  1641.5  891.84
  1720.2   878.7  1867.8  810.08  2241.8     894  2369.7     886  2566.5  945.11
  2960.2 1037.39  3156.6 1016.49  3254.8 1016.68  3441.4    1035  3578.8 1060.48
  3853.7  982.38  3942.1  946.25  4266.1  865.15  4344.6   854.3  4599.9  781.81
  4737.3   812.9  4845.3  823.11  5022.1  778.16  5532.6  947.05  5630.8  951.26
#Mann= 3 , 0 , 0
       0      .1       0   197.3    .045       0   275.6     .07       0
Bank Sta=197.3,275.6
XS Rating Curve= 0 ,0
Exp/Cntr=0.3,0.1

Type RM Length L Ch R = 1 ,64594.2 ,523.3,542,560.8
XS GIS Cut Line= 4
      1592007.63      335114.653     1592113.532      334934.098
     1592073.602      334494.861     1592108.324      334392.431
#Sta/Elev= 30
       0  757.32    28.5  755.12    38.1  753.87    47.6  752.12    95.2  742.12
   161.8  727.36   209.3  718.21   248.5  713.69   277.9  711.62   287.7  709.63
   297.5  704.98   307.3  698.56   317.1  693.67   326.9   692.1   385.7  692.38
   405.3  694.36   464.2  702.52   483.8  704.91   503.4   705.8   542.6  706.34
     572  707.93   601.4  710.75   640.6   715.6   650.4  718.07     670  725.48
   679.9  728.18   689.7  729.09   699.5  731.34   709.4  736.31   758.5  765.62
#Mann= 3 , 0 , 0
       0      .1       0   317.1    .045       0   385.7     .08       0
Bank Sta=317.1,385.7
XS Rating Curve= 0 ,0
Exp/Cntr=0.3,0.1

Type RM Length L Ch R = 1 ,64052.2 ,498.2,515,531.6
XS GIS Cut Line= 3
     1592064.588      335446.081     1592702.074      334735.313
     1593118.741      334428.021
#Sta/Elev= 30
       0  727.23   136.4  717.99   253.3  704.66   292.3  710.52   428.7  708.98
   496.9  715.98   584.6  714.06   750.2  715.19   769.7  711.24   808.6  693.69
   857.3   691.8   896.3   692.6     906  696.14   925.5  709.43   935.3  714.13
   954.8  720.53   984.1  744.66  1042.7   797.1  1091.5     834  1111.1  832.85
  1257.6     793  1277.1  785.15  1306.4  763.69  1316.2  761.03    1326  762.76
  1345.5  772.33  1355.3  774.67  1374.8  773.26  1433.4  763.57  1472.5  760.76
#Mann= 3 , 0 , 0
       0     .07       0   808.6    .045       0   896.3      .1       0
Bank Sta=808.6,896.3
XS Rating Curve= 0 ,0
Exp/Cntr=0.3,0.1

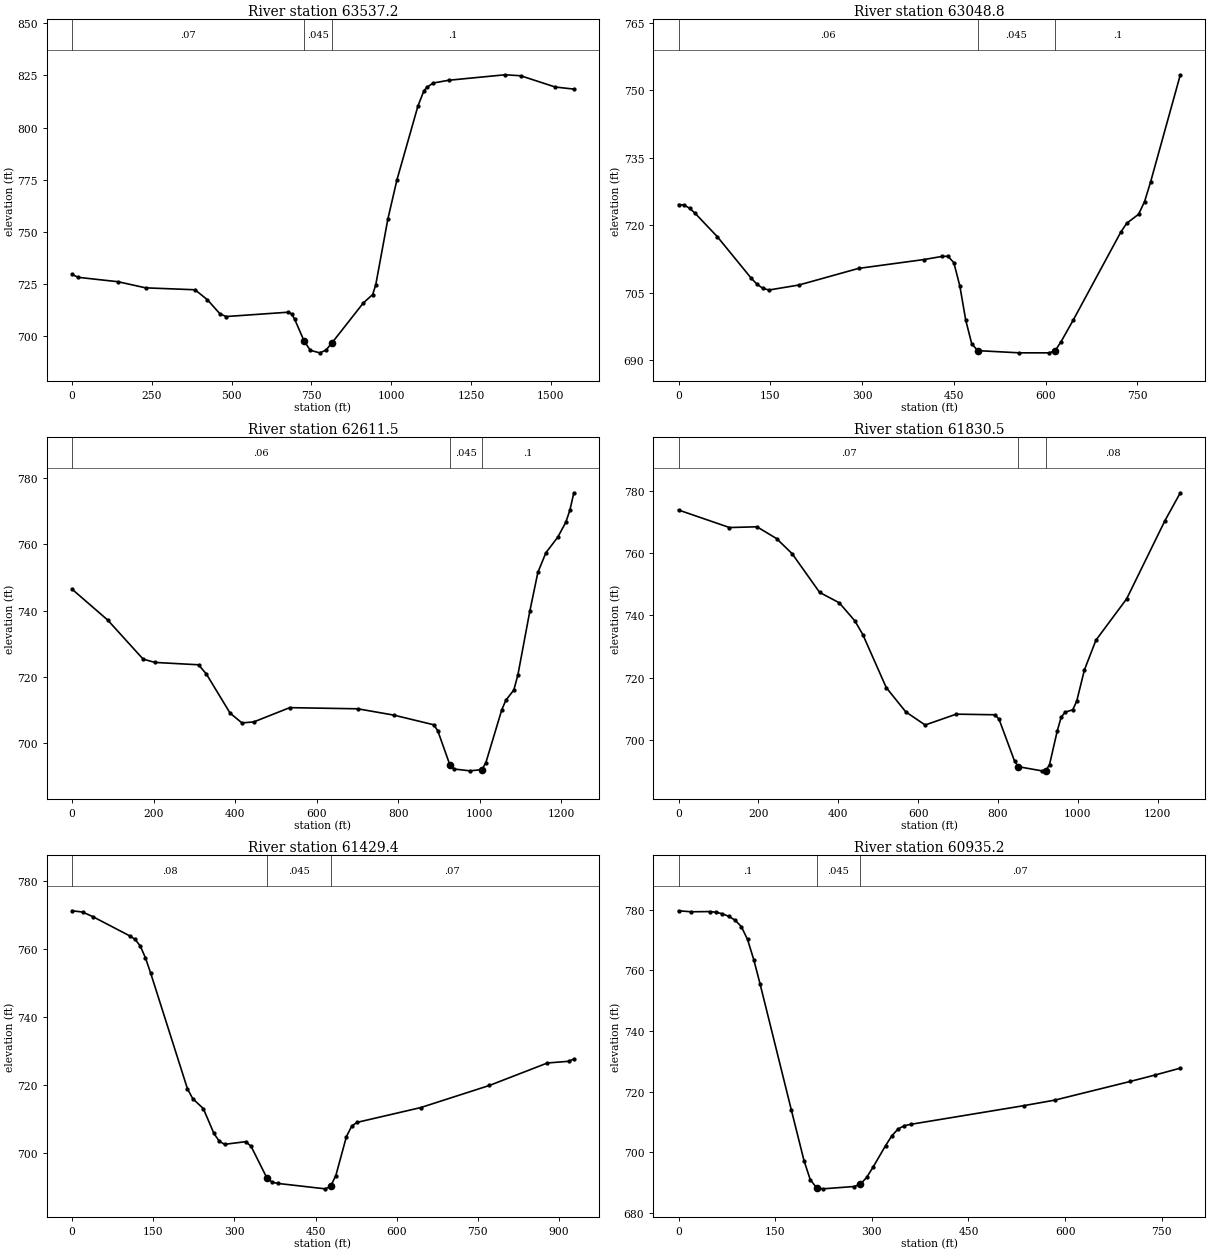
Type RM Length L Ch R = 1 ,63537.2 ,486.2,488.4,490.6
XS GIS Cut Line= 6
     1592206.548      335583.281     1592390.923      335387.584
     1592487.963      335279.224     1593032.602      335227.747
     1593181.795      335248.495     1593610.386      335416.696
#Sta/Elev= 30
       0  729.46    19.2  728.07     144  725.96   230.5  723.02   385.2   722.1
   424.1   717.3   463.2  710.58   482.7  709.24   678.1  711.33   687.9  710.51
   697.6  707.94   726.9  697.56   746.5  693.04   775.8  691.81   795.3  693.05
   814.9   696.7   912.6  715.74   941.9  719.81   951.6  724.45   989.6  756.08
  1017.9  774.81  1083.8  810.34  1102.6  817.66    1112  819.34  1131.6  821.38
  1180.6  822.72  1356.9  825.34  1405.9  824.87  1513.7  819.47  1572.4  818.46
#Mann= 3 , 0 , 0
       0     .07       0   726.9    .045       0   814.9      .1       0
Bank Sta=726.9,814.9
XS Rating Curve= 0 ,0
Exp/Cntr=0.3,0.1

Type RM Length L Ch R = 1 ,63048.8 ,425.3,437.3,449.2
XS GIS Cut Line= 3
     1592371.345         335665.     1592462.491      335724.896
     1593173.428        335727.5
#Sta/Elev= 30
       0  724.63     9.1  724.53    18.2  723.79    27.3  722.66    63.6  717.46
   118.8  708.27   128.5   706.9   138.3  705.99     148  705.66   196.7  706.76
   294.1  710.45   401.2  712.42   430.4  713.11   440.2  713.16   449.9  711.73
   459.7  706.53   469.4  698.91   479.1  693.73   488.9  692.19   557.1   691.7
   605.8   691.7   615.5  692.18   625.2   694.2   644.7   698.9   722.6  718.48
   732.4  720.48   751.8  722.47   761.6   725.3   771.3   729.6     820  753.45
#Mann= 3 , 0 , 0
       0     .06       0   488.9    .045       0   615.5      .1       0
Bank Sta=488.9,615.5
XS Rating Curve= 0 ,0
Exp/Cntr=0.3,0.1

Type RM Length L Ch R = 1 ,62611.5 ,767.8,781,793.9
XS GIS Cut Line= 3
     1592064.588      335617.956     1592431.241      335904.584
     1593090.095      336295.209
#Sta/Elev= 30
       0  746.46    87.3  737.17   174.5  725.36   203.6  724.38   310.3  723.67
   329.6  720.88   387.8  709.09   416.9  706.15     446  706.45   534.1  710.75
   701.1   710.4   789.4   708.5   887.6  705.58   897.5  703.74   926.9  693.54
   936.7  692.26     976   691.7  1005.5  692.06  1015.3  694.13  1054.6  710.17
  1064.4  712.97    1084  716.07  1093.9  720.59  1123.3  739.88    1143  751.52
  1162.6  757.42  1192.1  762.19  1211.7  766.68  1221.5  770.27  1231.3  775.52
#Mann= 3 , 0 , 0
       0     .06       0   926.9    .045       0  1005.5      .1       0
Bank Sta=926.9,1005.5
XS Rating Curve= 0 ,0
Exp/Cntr=0.3,0.1

Type RM Length L Ch R = 1 ,61830.5 ,404.9,401.1,397.3
XS GIS Cut Line= 4
     1591496.879       336170.04     1592017.178      336172.813
     1592236.463      336617.956     1592455.213      336716.915
#Sta/Elev= 30
       0  773.81   127.6  768.18   196.3  768.42   245.4  764.65   284.7  759.75
   353.4  747.34   402.5  744.02   441.8  738.18   461.4  733.83   520.3  716.76
     569     709   617.6  704.78   695.4  708.26   792.7  708.06   802.5  706.66
   841.4  693.22   851.1  691.39   909.5  690.06   919.2  690.08     929  692.04
   948.4  702.87   958.2  707.28   967.9  708.87   987.3  709.68   997.1  712.42
  1016.5   722.5  1045.3  732.02  1122.2  745.29  1218.2  770.42  1256.6  779.34
#Mann= 3 , 0 , 0
       0     .07       0   851.1    .045       0   919.2     .08       0
Bank Sta=851.1,919.2
XS Rating Curve= 0 ,0
Exp/Cntr=0.3,0.1

Type RM Length L Ch R = 1 ,61429.4 ,514.9,494.2,473.4
XS GIS Cut Line= 4
     1591630.198      336289.773     1591686.449      336485.313
      1591980.72      336888.959     1592189.053      336972.292
#Sta/Elev= 30
       0   771.1    19.4  770.73    38.8  769.34   106.6  763.72   116.3  762.72
     126  760.77   135.6  757.27   145.3  752.75   213.3  718.74   223.1  715.85
   242.6  712.95   262.2  705.63     272  703.38   281.8  702.44     321  703.23
   330.8  701.87   360.2  692.52     370  691.32   379.8  690.96   467.9  689.36
   477.7  690.08   487.5  693.27   507.1  704.74   516.9  707.81   526.7   708.9
   644.2  713.24   771.3  719.75   878.6  726.36   917.6  726.85   927.4  727.54
#Mann= 3 , 0 , 0
       0     .08       0   360.2    .045       0   477.7     .07       0
Bank Sta=360.2,477.7
XS Rating Curve= 0 ,0
Exp/Cntr=0.3,0.1

Type RM Length L Ch R = 1 ,60935.2 ,703.8,699.5,695
XS GIS Cut Line= 2
     1591363.532      337066.042     1592142.178      337081.667
#Sta/Elev= 30
       0  779.66    19.5  779.33    48.7   779.4    58.4  779.16    68.2  778.66
    77.9  777.82    87.6  776.59    97.4  774.46   107.1  770.19   116.8  763.49
   126.6  755.48   175.2  713.83   194.7  697.25   204.4  690.95   214.2  688.28
   223.9  687.91   272.6  688.68   282.3  689.46     292  691.69   301.8  695.03
   321.3  702.16     331  705.38   340.7  707.66   350.5  708.75   360.2  709.19
   535.4  715.34   584.1  717.19   700.9  723.34   739.9  725.48   778.8  727.74
#Mann= 3 , 0 , 0
       0      .1       0   214.2    .045       0   282.3     .07       0
Bank Sta=214.2,282.3
XS Rating Curve= 0 ,0
Exp/Cntr=0.3,0.1

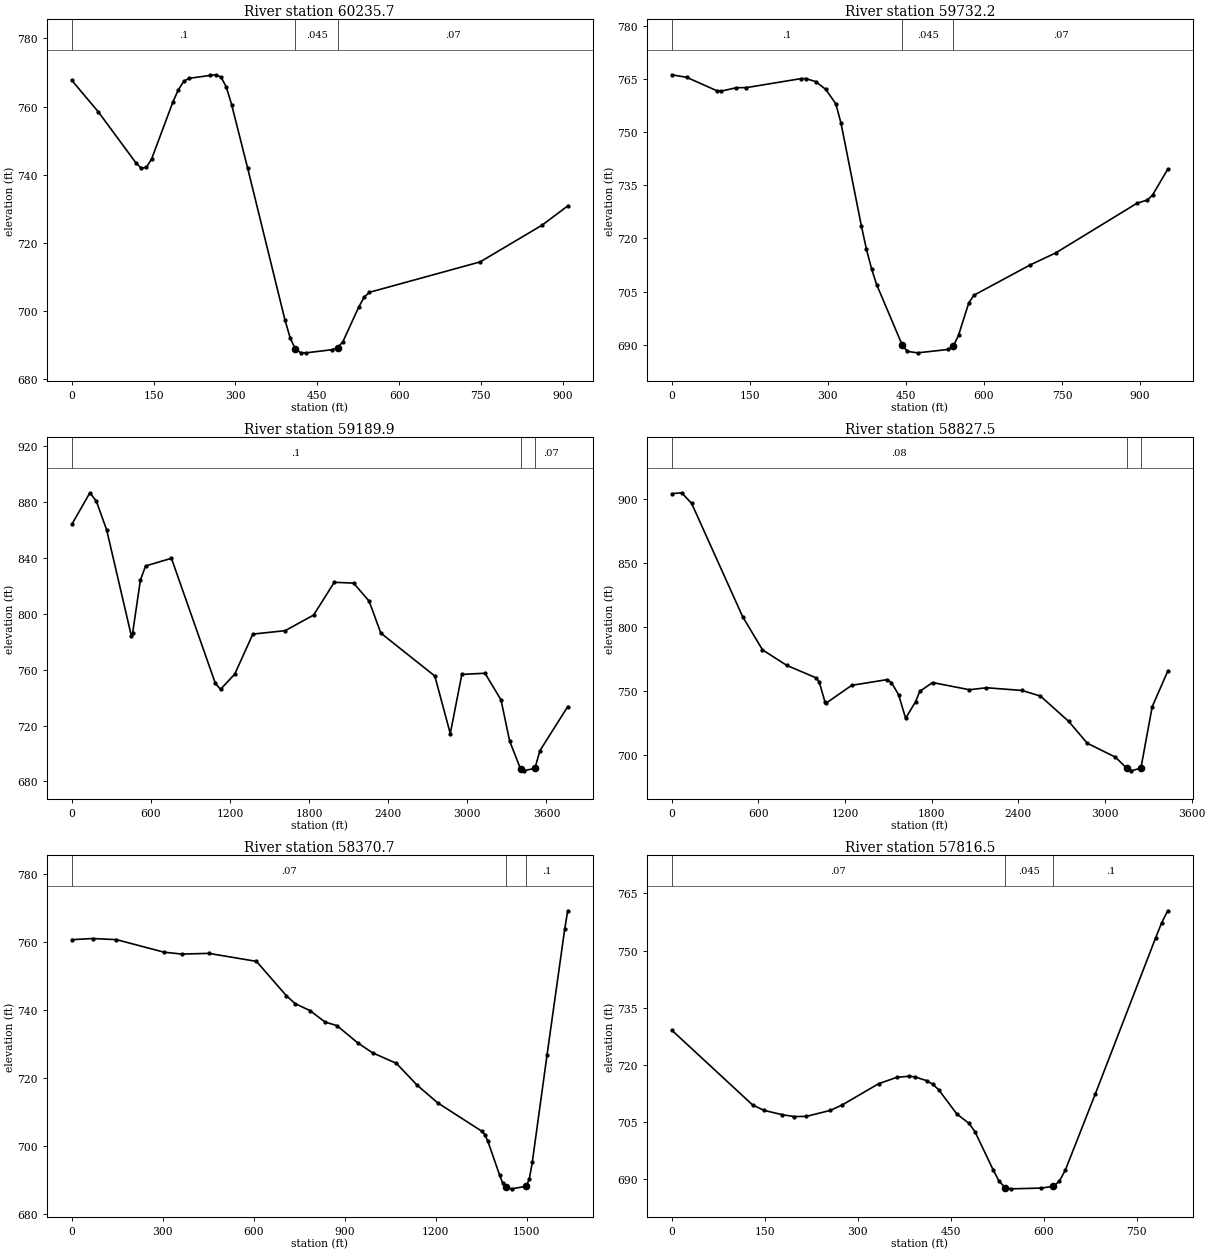
Type RM Length L Ch R = 1 ,60235.7 ,505.9,503.5,501.1
XS GIS Cut Line= 4
     1591335.059      337913.037     1591695.998      337763.525
     1592067.091       337696.25      1592205.98      337670.209
#Sta/Elev= 30
       0  767.69    48.8   758.4   117.2  743.55     127  741.93   136.7  742.11
   146.5  744.67   185.6  761.42   195.3   764.9   205.1  767.36   214.9  768.27
   253.9  769.13   263.7  769.31   273.5  768.63   283.2  765.76     293  760.56
   322.3  741.97   390.7  697.42   400.4  692.04     410  688.77   419.7  687.77
   429.4  687.72   477.7  688.65   487.4  689.25     497     691   526.1  701.18
   535.7     704   545.4  705.47   748.5   714.4     862  725.17   909.1  730.82
#Mann= 3 , 0 , 0
       0      .1       0     410    .045       0   487.4     .07       0
Bank Sta=410,487.4
XS Rating Curve= 0 ,0
Exp/Cntr=0.3,0.1

Type RM Length L Ch R = 1 ,59732.2 ,544.7,542.3,539.9
XS GIS Cut Line= 4
     1591674.417      338581.511     1591733.565      338281.994
      1592224.37      338139.787      1592356.51       338104.55
#Sta/Elev= 30
       0  766.23    28.6  765.51    85.9  761.77    95.4  761.63     124  762.58
   143.1   762.6   248.1  765.14   257.6  765.16   276.7  764.29   295.8  762.11
   315.1  758.05     325  752.64   364.3   723.5   374.1  716.92   383.9   711.4
   393.7  706.94   442.9  689.86   452.7  688.11   472.4   687.7   531.3  688.66
   541.1  689.63     551  692.69   570.6  701.79   580.4  703.96   688.5  712.52
   737.7  715.92   894.4  729.99     914  730.85   923.7  732.25     953  739.56
#Mann= 3 , 0 , 0
       0      .1       0   442.9    .045       0   541.1     .07       0
Bank Sta=442.9,541.1
XS Rating Curve= 0 ,0
Exp/Cntr=0.3,0.1

Type RM Length L Ch R = 1 ,59189.9 ,364.2,362.4,360.5
XS GIS Cut Line= 6
     1589642.713      337784.623      1590201.84      337807.736
     1591201.072      339285.719     1591767.178      338734.445
     1591917.352      338809.532     1592342.699       338635.92
#Sta/Elev= 30
       0  863.86   137.4  886.53   186.5  880.47   265.1   859.8   451.6  784.21
   461.4  786.12   520.3     824   559.6  834.15   755.7  839.68  1088.9  750.17
  1128.2  745.92    1236  756.82  1373.2  785.43  1618.3  787.88  1833.9  799.04
  1990.8  822.49  2137.8   821.9  2255.4  808.93  2343.7  786.16  2753.4  755.42
  2870.5  714.26  2958.2  756.56  3133.8  757.44  3255.1  738.42  3320.9  708.89
  3403.2 689.036  3426.2   687.6  3512.3   689.4  3550.6  702.07  3761.2  733.55
#Mann= 3 , 0 , 0
       0      .1       0  3403.2    .045       0  3512.3     .07       0
Bank Sta=3403.2,3512.3
XS Rating Curve= 0 ,0
Exp/Cntr=0.3,0.1

Type RM Length L Ch R = 1 ,58827.5 ,445.9,456.7,467.4
XS GIS Cut Line= 6
     1589627.088      339878.373     1591434.379      340050.248
     1591778.975       339420.67     1591943.393      339200.157
     1592388.272      338974.462      1592514.14      338954.931
#Sta/Elev= 30
       0  904.24    68.7  904.94   137.4  896.61   490.7     808     628  782.06
   794.9  769.98    1001  760.07  1020.6  756.98  1059.8  741.61  1069.6  740.43
  1246.3  754.33  1491.6  758.77    1521  756.42  1570.1  747.08  1619.2  728.53
  1687.9  741.46  1717.3   749.6  1805.6  756.47  2061.2  750.85  2179.2  752.41
    2425  750.28  2552.8  745.91  2749.3  726.01  2876.7  709.02  3072.3  698.09
  3150.6   689.4  3179.9   687.4  3248.4  689.47  3326.7  737.59  3434.4  765.37
#Mann= 3 , 0 , 0
       0     .08       0  3150.6    .045       0  3248.4      .1       0
Bank Sta=3150.6,3248.4
XS Rating Curve= 0 ,0
Exp/Cntr=0.3,0.1

Type RM Length L Ch R = 1 ,58370.7 ,554,554.2,554.4
XS GIS Cut Line= 4
       1591322.4      340265.468     1591985.387      339424.864
     1592064.921      339460.573     1592542.352      339464.914
#Sta/Elev= 30
       0  760.77    68.8  761.11   147.3  760.78   304.5  757.08   363.4  756.53
   451.8  756.74     609  754.38   707.2   744.3   736.6  741.92   785.8  739.88
   834.9  736.52   874.2  735.47   942.9  730.38     992  727.44  1070.6  724.34
  1138.4  717.95  1206.5  712.72  1352.6  704.33  1362.4  703.29  1372.1  701.35
  1411.1  691.34  1420.9   689.1  1430.6  687.81  1450.1   687.4  1498.8  688.15
  1508.6  690.36  1518.3  695.18    1567  726.81  1625.5  764.03  1635.2  769.28
#Mann= 3 , 0 , 0
       0     .07       0  1430.6    .045       0  1498.8      .1       0
Bank Sta=1430.6,1498.8
XS Rating Curve= 0 ,0
Exp/Cntr=0.3,0.1

Type RM Length L Ch R = 1 ,57816.5 ,506.1,505.5,504.5
XS GIS Cut Line= 3
     1591828.376      339951.025     1591965.095      340009.618
     1592616.137      340020.469
#Sta/Elev= 30
       0  729.07   130.2  709.45   148.8  708.01   177.9  706.88   197.3  706.39
   216.8  706.43   255.6     708   275.1  709.46   333.4     715   362.6  716.67
     382  716.98   391.7  716.81   411.1  715.82   420.9  714.87   430.6   713.4
   459.7  707.07   479.2  704.61   488.9  702.44     518  692.48   527.8  689.41
   537.5  687.75   547.2   687.4   595.8   687.6   615.2  688.04     625   689.4
   634.7  692.32   683.3  712.43   780.4  753.35   790.2  757.34   799.9  760.44
#Mann= 3 , 0 , 0
       0     .07       0   537.5    .045       0   615.2      .1       0
Bank Sta=537.5,615.2
XS Rating Curve= 0 ,0
Exp/Cntr=0.3,0.1