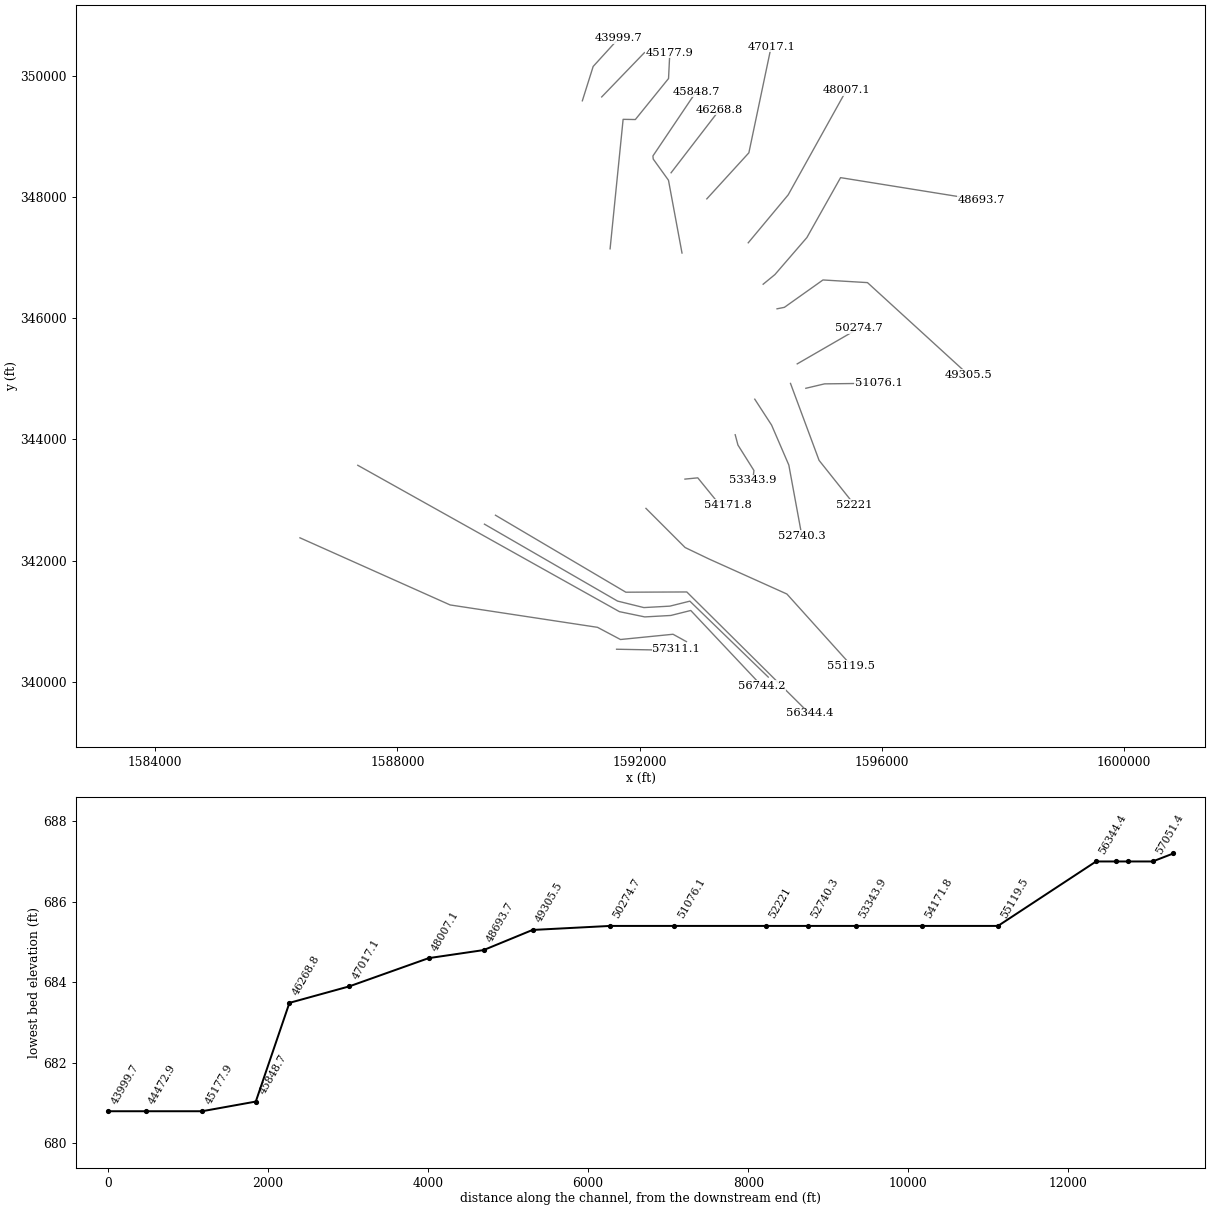
HEC-RAS study MDISLCRK_C.prj: MDISLCRK_C

--- MDISLCRK_C.g01 (geometry) --- (continued)

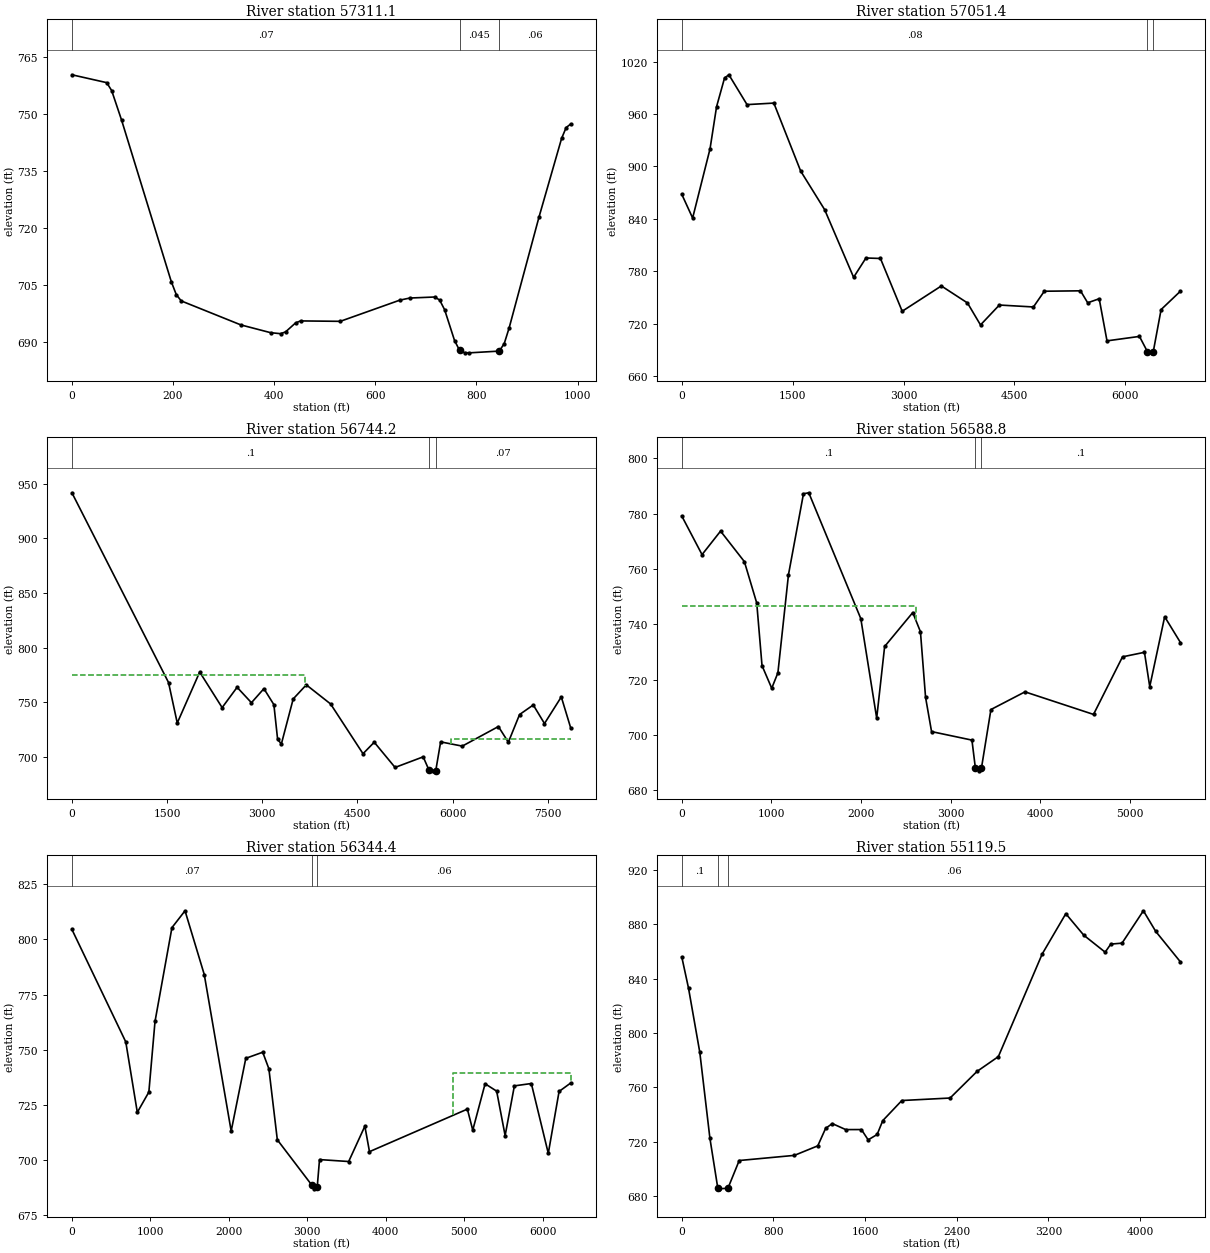
Type RM Length L Ch R = 1 ,57311.1 ,258.5,259.7,260.6
XS GIS Cut Line= 3
     1591620.893      340534.841     1592544.522      340517.431
     1592603.116      340539.132
#Sta/Elev= 30
       0  760.36    68.8  758.29    78.6  756.21    98.3   748.4   196.6   705.9
   206.4  702.52   216.2  700.86   334.1  694.55   393.1   692.5   412.8  692.24
   422.6  692.72   442.2  695.06   452.1   695.6   530.7  695.49   648.6  701.07
   668.3  701.62   717.4  701.89   727.2   701.1   737.1  698.54   756.7  690.44
   766.6  687.87   776.4  687.25   786.2   687.2   845.2  687.66     855  689.64
   864.8  693.81   923.8  722.96   968.4  743.61   977.4  746.47   986.3  747.39
#Mann= 3 , 0 , 0
       0     .07       0   766.6    .045       0   845.2     .06       0
Bank Sta=766.6,845.2
XS Rating Curve= 0 ,0
Exp/Cntr=0.3,0.1

Type RM Length L Ch R = 1 ,57051.4 ,306,307.2,308.5
XS GIS Cut Line= 6
     1586391.845      342374.843     1588872.229      341266.245
     1591305.634      340896.756     1591685.147      340695.382
     1592553.202      340782.188     1592774.557       340660.66
#Sta/Elev= 30
       0  868.27   147.1  841.12   382.5  920.21   470.8  968.34   578.7 1001.17
   637.5 1004.84   882.7  970.74  1245.6  972.49  1608.5  894.76  1932.2  850.72
  2324.5  773.32  2491.3  795.42  2687.4  794.87  2981.6  734.52  3511.1  763.46
  3864.2  744.05  4040.7  718.88  4295.6  741.65  4756.5  739.43  4903.6  757.42
    5393   757.9  5490.6   744.2  5646.1  748.84  5751.6   700.7  6190.6  705.78
  6297.9  688.44  6356.4     687    6376  687.64  6483.3  736.45  6745.5  757.54
#Mann= 3 , 0 , 0
       0     .08       0  6297.9    .045       0    6376     .06       0
Bank Sta=6297.9,6376
XS Rating Curve= 0 ,0
Exp/Cntr=0.3,0.1

Type RM Length L Ch R = 1 ,56744.2 ,155.5,155.4,155.4
XS GIS Cut Line= 6
     1587346.706       343572.76     1591667.598       341155.67
     1592086.623      341068.646      1592516.31      341092.518
     1592846.171      341174.983     1594016.726      339931.543
#Sta/Elev= 30
       0  941.85  1522.6  767.96  1660.2  730.84  2013.8  777.55  2367.4  744.96
  2603.2  763.58  2829.1  749.44  3025.6  762.32  3182.8  747.66  3241.7  715.87
  3300.7  711.62  3487.3   752.9  3693.6  765.82  4076.7  748.29  4587.5  702.69
  4764.4  713.22  5092.7  690.11  5535.8  699.83  5628.5  687.49  5695.7     687
  5734.1  687.25  5810.9  713.54  6151.8  709.66    6721   727.6    6878  713.23
  7054.7   738.6  7270.6  747.38  7447.3  730.35  7712.3  754.75  7859.5  726.53
#Mann= 3 , 0 , 0
       0      .1       0  5628.5    .045       0  5734.1     .07       0
#XS Ineff= 2 , 0
          3670.5  775.13 5980.51           716.2
Permanent Ineff=
       F       F
Bank Sta=5628.5,5734.1
XS Rating Curve= 0 ,0
Exp/Cntr=0.3,0.1

Type RM Length L Ch R = 1 ,56588.8 ,246.2,244.4,242.6
XS GIS Cut Line= 6
      1589438.72      342600.537     1591636.938      341330.108
     1592071.432      341222.726     1592501.119      341246.598
      1592830.98      341329.063      1594126.22      340074.496
#Sta/Elev= 30
       0  779.15   226.3  765.18     433  773.68   698.7  762.64   836.5  747.68
   895.5  725.04  1003.8  716.86  1072.6  722.44  1190.7  757.94    1358  787.19
  1417.1  787.54  1997.7  742.03  2174.8  706.06  2263.4  731.96  2577.1  744.23
  2662.8  737.31    2720  713.58  2786.9  701.19  3237.4  698.11  3275.8  688.03
  3320.5     687  3343.1  687.91  3449.2  709.16  3829.3  715.56  4593.8   707.4
  4917.2  728.22  5162.2  729.86    5221  717.45  5387.6  742.72    5564  733.37
#Mann= 3 , 0 , 0
       0      .1       0  3275.8    .045       0  3343.1      .1       0
#XS Ineff= 2 , 0
          2614.7  746.73 3842.34          715.36
Permanent Ineff=
       F       F
Bank Sta=3275.8,3343.1
XS Rating Curve= 0 ,0
Exp/Cntr=0.3,0.1

Type RM Length L Ch R = 1 ,56344.4 ,1242.4,1224.8,1206.8
XS GIS Cut Line= 4
     1589621.011      342748.107      1591773.77       341476.76
     1592780.733      341480.746     1594803.303      339475.537
#Sta/Elev= 30
       0  804.55   686.3  753.59   833.4  721.66   980.4  730.85  1058.9  762.85
  1274.6  805.37  1441.3  813.01  1686.4  784.13  2029.5  713.17  2215.8  746.15
  2431.5  748.91  2509.9  741.41  2617.5  709.22  3057.4  688.67  3086.7     687
  3125.8  687.77  3155.2  700.26  3526.8  699.38    3733   715.4  3791.9  703.85
  5039.2  723.13  5107.9  713.59  5265.1  734.61  5412.4  731.28  5520.4  711.14
  5638.3  733.66  5854.3  734.73  6070.4  703.07  6207.9  731.13  6355.2  734.94
#Mann= 3 , 0 , 0
       0     .07       0  3057.4    .045       0  3125.8     .06       0
#XS Ineff= 2 , 0
                         4854.74          739.64
Permanent Ineff=
       F       F
Bank Sta=3057.4,3125.8
XS Rating Curve= 0 ,0
Exp/Cntr=0.3,0.1

Type RM Length L Ch R = 1 ,55119.5 ,950.1,947.7,945.5
XS GIS Cut Line= 5
     1592106.154      342861.181     1592752.855      342214.479
      1593147.75      342025.091     1594434.205      341446.607
     1595497.747      340265.468
#Sta/Elev= 30
       0  856.05      59  833.01   157.4  785.82   245.8  722.53   314.7  685.83
   324.5   685.4   403.2  685.86   501.5  706.23   982.7  710.01  1187.1  717.03
  1255.2  729.83  1313.6  733.41  1430.9  728.98    1568     729  1626.8  721.43
  1705.2  725.38  1754.2  735.56  1920.7  750.36  2341.9   752.2    2577  771.78
  2763.1  782.66  3145.7  858.15  3351.7  887.78  3508.7  871.96  3695.1  859.48
  3744.2  865.42  3842.3  866.12  4028.7  889.93  4136.6  874.75  4352.5  852.28
#Mann= 3 , 0 , 0
       0      .1       0   314.7    .045       0   403.2     .06       0
Bank Sta=314.7,403.2
XS Rating Curve= 0 ,0
Exp/Cntr=0.3,0.1

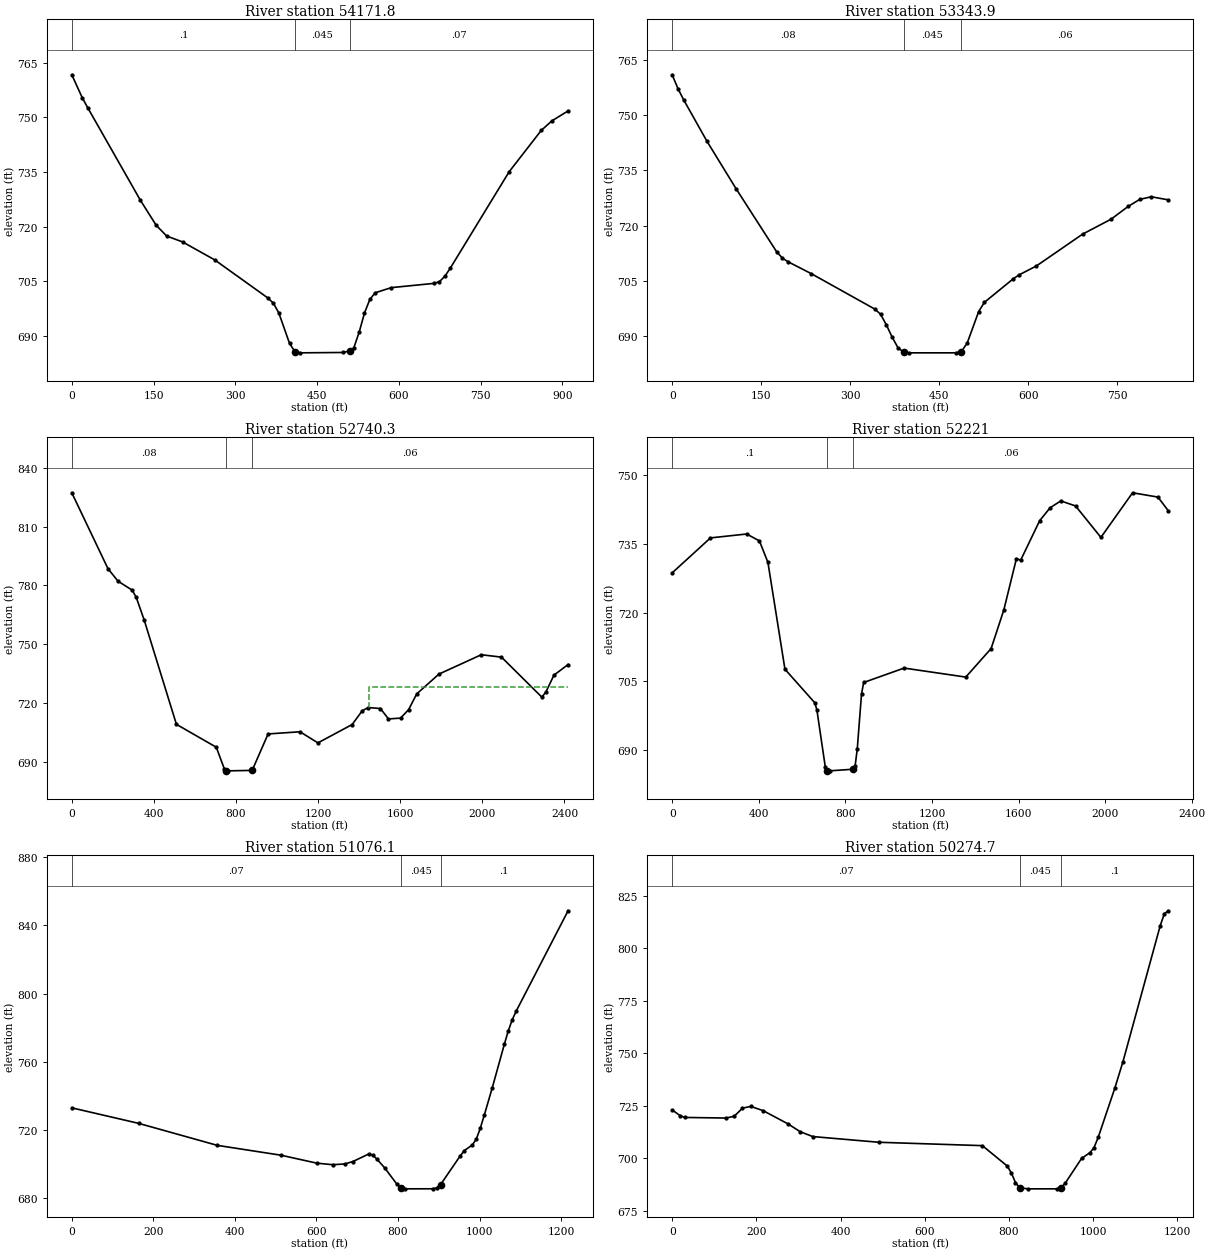
Type RM Length L Ch R = 1 ,54171.8 ,830.6,827.9,825.1
XS GIS Cut Line= 4
     1592750.251      343344.688     1592962.057      343365.521
     1593278.029      342976.632     1593465.529      342917.604
#Sta/Elev= 30
       0  761.68    19.4  755.32      29   752.7   125.8  727.27   154.8   720.4
   174.1  717.44   203.2  715.83     262  710.92   360.2   700.4     370  698.97
   379.8  696.36   399.5  687.98   409.3  685.74   419.2   685.4   497.8   685.5
   510.5685.9533   517.4  686.77   527.2  691.05     537  696.33   546.9  700.08
   556.7  701.88   586.2  703.29   664.8  704.46   674.6  704.94   684.4  706.39
   694.2  708.58   802.4  735.08   861.3  746.42     881  749.06   910.5  751.76
#Mann= 3 , 0 , 0
       0      .1       0   409.3    .045       0   510.5     .07       0
Bank Sta=409.3,510.5
XS Rating Curve= 0 ,0
Exp/Cntr=0.3,0.1

Type RM Length L Ch R = 1 ,53343.9 ,607,603.5,600.1
XS GIS Cut Line= 4
     1593580.112      344077.327     1593625.251      343907.188
      1593889.14      343487.049     1593871.779      343323.854
#Sta/Elev= 30
       0  761.01     9.8  757.21    19.6  754.12    58.7   742.9   107.6  730.04
     176  712.88   185.8  711.15   195.5  710.14   234.4  706.93   341.4   697.3
   351.1   695.9   360.9  693.01   370.6  689.68   380.3  686.85     390  685.54
   399.8   685.4   477.6   685.4   487.3  685.75   497.1  688.06   516.5  696.64
   526.2  699.15   574.9  705.55   584.6   706.6   613.8  709.03   691.5  717.67
   739.7  721.75   768.7  725.25     788  727.13   807.3  727.84   836.3  726.99
#Mann= 3 , 0 , 0
       0     .08       0     390    .045       0   487.3     .06       0
Bank Sta=390,487.3
XS Rating Curve= 0 ,0
Exp/Cntr=0.3,0.1

Type RM Length L Ch R = 1 ,52740.3 ,520.5,519.3,518.1
XS GIS Cut Line= 4
     1593903.129      344664.484     1594180.807      344237.049
     1594465.529      343577.327     1594680.907       342407.54
#Sta/Elev= 30
       0  827.23   176.4  788.49   225.4  782.13   294.1  777.56   313.7  773.97
   352.9  762.25   509.7  709.12   703.9  697.44   742.8  686.51   752.5  685.45
   762.2   685.4   878.7  685.62   956.4  704.22  1111.7  705.33  1199.1  699.66
  1365.9  709.03    1415  716.05  1444.5  717.68  1503.5  717.19  1542.8  711.87
  1601.8   712.3  1641.1  716.66  1680.4  724.65  1788.6  734.75    1995  744.62
  2093.3   743.4  2289.9  723.01  2309.6  725.59  2348.9   734.2  2417.7  739.62
#Mann= 3 , 0 , 0
       0     .08       0   752.5    .045       0   878.7     .06       0
#XS Ineff= 2 , 0
                         1445.97          728.37
Permanent Ineff=
       F       F
Bank Sta=752.5,878.7
XS Rating Curve= 0 ,0
Exp/Cntr=0.3,0.1

Type RM Length L Ch R = 1 ,52221   ,1117.2,1144.9,1172.5
XS GIS Cut Line= 3
     1594493.407      344924.901     1594965.529      343653.716
     1595548.963      342921.429
#Sta/Elev= 30
       0  728.67   176.9  736.31   343.9  737.16   402.9  735.65   442.2  730.95
   520.8  707.61   658.4  700.29   668.2  698.76   707.5  686.13   717.3  685.44
   727.2   685.4   835.2  685.75   845.1  686.53   854.9  690.23   874.5   702.2
   884.4  704.71  1071.1  707.86    1356  705.89  1473.1  712.13  1531.6  720.53
  1590.1   731.8  1609.6  731.43  1697.4  740.08  1746.2  742.92  1794.9  744.39
  1863.2  743.29  1980.2  736.42  2126.5  746.17  2243.6  745.23  2292.3  742.19
#Mann= 3 , 0 , 0
       0      .1       0   717.3    .045       0   835.2     .06       0
Bank Sta=717.3,835.2
XS Rating Curve= 0 ,0
Exp/Cntr=0.3,0.1

Type RM Length L Ch R = 1 ,51076.1 ,789.6,801.3,812.7
XS GIS Cut Line= 3
     1594746.779      344844.688     1595055.807      344917.604
     1595955.112      344928.021
#Sta/Elev= 30
       0  732.93   163.6  723.84   356.6  710.92     513  705.13     601  700.46
   640.1  699.56   669.4     700     689  701.39   728.1  705.84   737.9  705.16
   747.6  703.01   767.2  697.69   796.5  688.37   806.3  686.08   816.1   685.4
   884.5  685.43   894.3  685.88   904.1  687.84   952.9  704.89   962.7  707.86
   982.3   711.2     992  714.63  1001.8  721.06  1011.6  728.76  1031.1  744.76
  1060.5  770.11  1070.2  778.04    1080  784.61  1089.8  789.74  1216.9  848.56
#Mann= 3 , 0 , 0
       0     .07       0   806.3    .045       0   904.1      .1       0
Bank Sta=806.3,904.1
XS Rating Curve= 0 ,0
Exp/Cntr=0.3,0.1

Type RM Length L Ch R = 1 ,50274.7 ,967.1,969.3,971.3
XS GIS Cut Line= 2
     1594604.518      345247.817     1595625.251      345837.743
#Sta/Elev= 30
       0  722.96    19.6  720.11    29.5  719.38   127.7   719.1   147.4  719.96
     167   723.8   186.7  724.63   216.1  722.61   275.1  716.31   304.6  712.54
     334  710.28   491.2  707.56   736.8  705.96   795.8  696.28   805.6  692.97
   815.4   688.4   825.3  685.92   844.9   685.4   913.7   685.4   923.5  685.91
   933.3     688   972.6  699.91   992.3   702.6  1002.1  705.04  1011.9  709.87
  1051.2  733.16  1070.9  746.01  1159.3  810.66  1169.1  816.36  1178.9  817.75
#Mann= 3 , 0 , 0
       0     .07       0   825.3    .045       0   923.5      .1       0
Bank Sta=825.3,923.5
XS Rating Curve= 0 ,0
Exp/Cntr=0.3,0.1

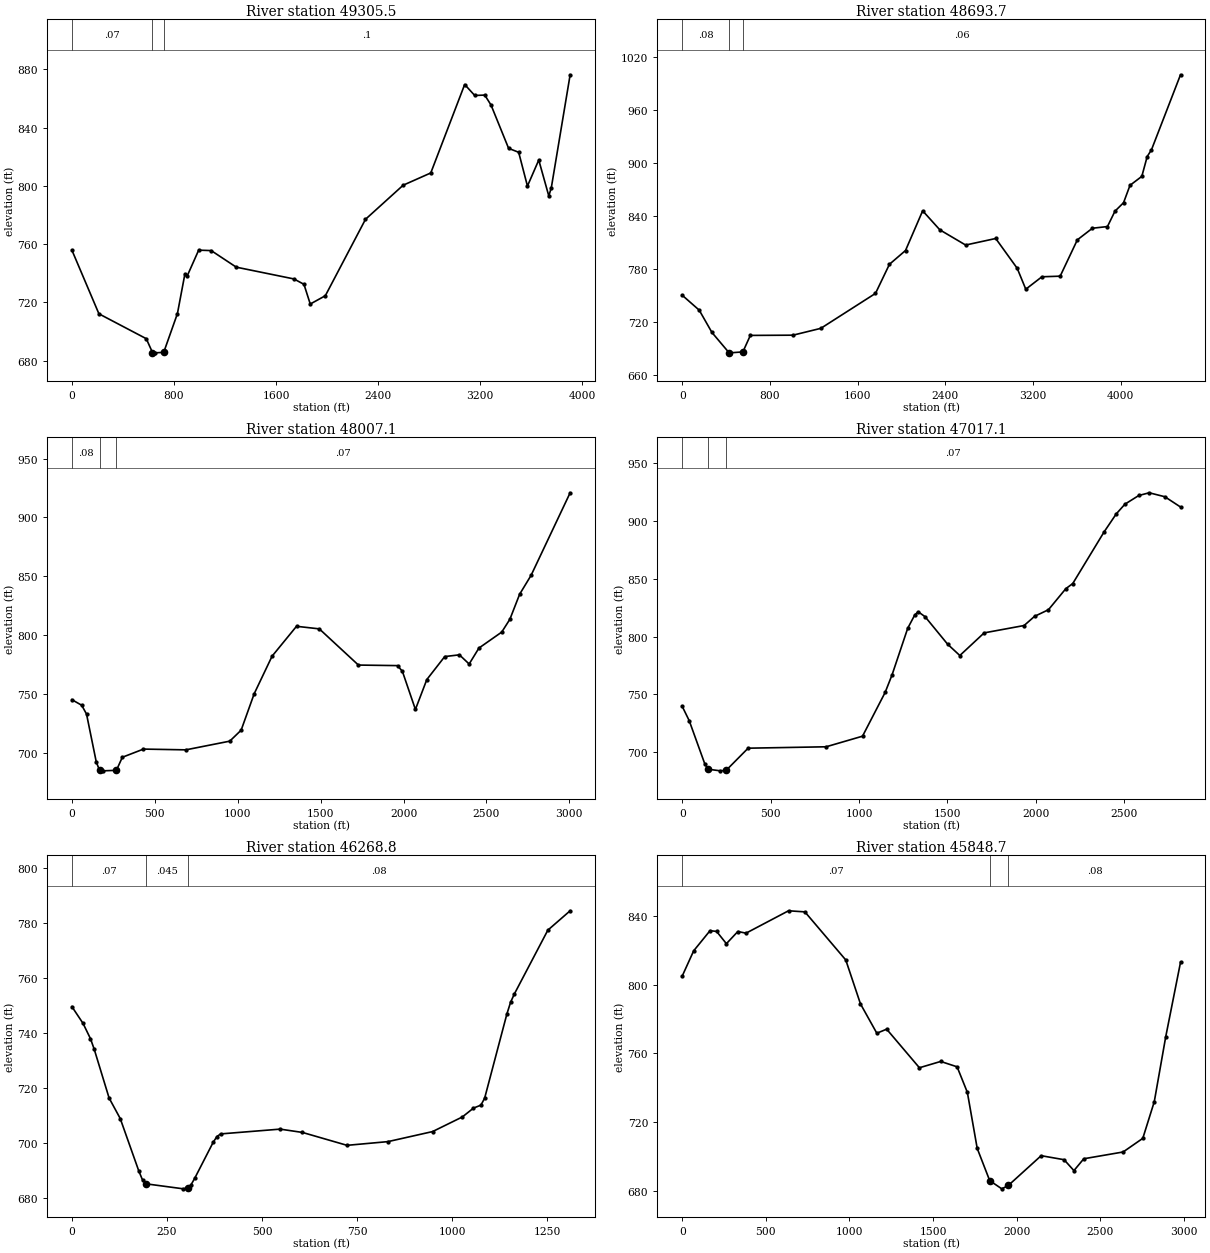
Type RM Length L Ch R = 1 ,49305.5 ,606.4,611.8,617.2
XS GIS Cut Line= 5
     1594271.084      346157.188     1594392.612      346181.493
      1595029.53      346633.606     1595764.654      346589.824
     1597435.247       345063.79
#Sta/Elev= 30
       0  755.84   211.8   712.1   582.8  695.02   631.6  685.51   651.2   685.3
   719.5  685.64   826.9  712.24   885.5  739.48     905  738.37   993.4  755.82
  1091.6  755.52    1288  744.14  1739.8  736.05  1818.5  732.35  1867.7  718.82
  1985.8  724.51  2300.6  777.01  2595.7  800.42  2812.1  808.84  3077.7  869.58
  3156.4  862.06  3235.1  862.31  3284.3  855.47    3422  825.73  3500.8  823.04
  3569.6  799.82  3658.2  817.71  3736.9  793.05  3756.5  798.64  3904.1  876.26
#Mann= 3 , 0 , 0
       0     .07       0   631.6    .045       0   719.5      .1       0
Bank Sta=631.6,719.5
XS Rating Curve= 0 ,0
Exp/Cntr=0.3,0.1

Type RM Length L Ch R = 1 ,48693.7 ,685.8,686.5,687.2
XS GIS Cut Line= 5
     1594041.918      346563.438     1594236.362       346723.16
      1594764.14      347334.271     1595320.284        348323.5
     1597643.581      347950.074
#Sta/Elev= 30
       0  749.92   154.8  733.09   271.1  707.82   426.8  684.97   436.5   684.8
   553.2  685.86   621.3  704.52  1010.5  704.78  1264.6  712.51  1763.5  752.05
  1890.7  784.96  2037.4  800.55    2194  845.48  2350.8  823.95  2586.1  806.76
  2860.7  814.16  3056.8  780.43  3135.2  756.77  3282.3  770.85  3448.9  771.53
  3605.8  812.64  3743.1  825.76  3880.4  827.67    3949  845.04  4027.4  854.67
  4086.2   874.3  4194.1  884.44  4243.1  906.88  4282.3  914.54  4547.1  999.37
#Mann= 3 , 0 , 0
       0     .08       0   426.8    .045       0   553.2     .06       0
Bank Sta=426.8,553.2
XS Rating Curve= 0 ,0
Exp/Cntr=0.3,0.1

Type RM Length L Ch R = 1 ,48007.1 ,991.1,990,988.6
XS GIS Cut Line= 3
      1593795.39      347247.466     1594455.112      348039.132
     1595414.848       349764.31
#Sta/Elev= 30
       0  745.07    58.9  740.38    88.3  732.86   147.2  692.03   166.8  685.12
   186.5   684.6   268.5685.0421   304.2  696.14   431.8  703.09     687  702.44
     952  709.83  1020.7  719.17  1099.3  750.12  1207.3  782.07  1354.6  807.46
  1492.1  805.27  1727.9  774.51  1963.6  774.04    1993   769.2  2071.6  736.78
  2140.4  762.17  2248.4  781.73  2336.8   783.2  2395.7  775.41  2454.7  788.96
  2592.2  802.54  2641.3  813.43  2700.2  834.73    2769  850.72  3004.7  920.95
#Mann= 3 , 0 , 0
       0     .08       0   166.8    .045       0   268.5     .07       0
Bank Sta=166.8,268.5
XS Rating Curve= 0 ,0
Exp/Cntr=0.3,0.1

Type RM Length L Ch R = 1 ,47017.1 ,746.3,748.3,750.1
XS GIS Cut Line= 3
     1593111.362       347973.16     1593805.807      348733.577
     1594173.529      350484.797
#Sta/Elev= 30
       0  739.56    39.2  727.33   127.5  689.94   147.1  685.28   215.8   683.9
     249684.4307   372.7  703.48     814  704.69    1020  713.86  1147.8  751.63
  1187.1  766.84  1275.6  807.09  1314.9  818.46  1334.6  821.44  1373.9  817.14
  1501.7  793.33  1570.6  783.58  1708.2  803.15  1934.3  809.51  1993.3  817.43
    2072  823.16  2170.3  841.36  2209.6  845.81  2386.6  890.36  2455.4  905.94
  2504.6  914.39  2583.2   921.9  2642.2  924.25  2730.7  920.82  2819.2  911.95
#Mann= 3 , 0 , 0
       0     .07       0   147.1    .045       0     249     .07       0
Bank Sta=147.1,249
XS Rating Curve= 0 ,0
Exp/Cntr=0.3,0.1

Type RM Length L Ch R = 1 ,46268.8 ,418.6,420.1,421.5
XS GIS Cut Line= 2
     1592521.084      348403.716     1593319.696       349441.91
#Sta/Elev= 30
       0  749.71    29.3  743.62    48.9  738.04    58.6  734.26    97.8   716.5
   127.1  709.03     176  689.94   185.7  686.71   195.5   685.3   293.2  683.49
   305.1683.9271   312.8  684.87   322.6  687.25   371.4   700.4   381.2  702.48
     391  703.45   547.4  705.19     606  703.99   723.3   699.3   830.9  700.65
   948.2   704.3  1026.4  709.61  1055.7  712.83  1075.2  713.91    1085  716.41
  1143.6  747.07  1153.4  751.35  1163.2  754.32  1251.2   777.5  1309.8  784.54
#Mann= 3 , 0 , 0
       0     .07       0   195.5    .045       0   305.1     .08       0
Bank Sta=195.5,305.1
XS Rating Curve= 0 ,0
Exp/Cntr=0.3,0.1

Type RM Length L Ch R = 1 ,45848.7 ,671.7,670.8,670
XS GIS Cut Line= 5
     1592701.306      347078.547     1592478.163      348280.352
     1592226.285      348630.313     1592221.251      348681.659
     1592932.932      349739.153
#Sta/Elev= 30
       0   805.1    68.4  819.78   166.2  831.51   205.4  831.07     264  823.92
   332.5  831.02   381.4  830.05   635.6   843.1   733.4  842.46   977.9  814.43
  1065.9  788.82  1163.7  771.73  1222.4   774.1  1418.3  751.61  1545.7  755.29
  1643.7  752.16  1705.1  737.26    1764  704.61  1838.7685.8399    1911  681.04
  1950.2  683.03  2146.4  700.36  2283.6  698.02  2342.4  691.66  2401.3  698.57
  2636.6  702.52  2754.3  710.47  2822.9  731.81  2891.5  769.72  2979.8  813.03
#Mann= 3 , 0 , 0
       0     .07       0  1838.7    .045       0  1950.2     .08       0
Bank Sta=1838.7,1950.2
XS Rating Curve= 0 ,0
Exp/Cntr=0.3,0.1

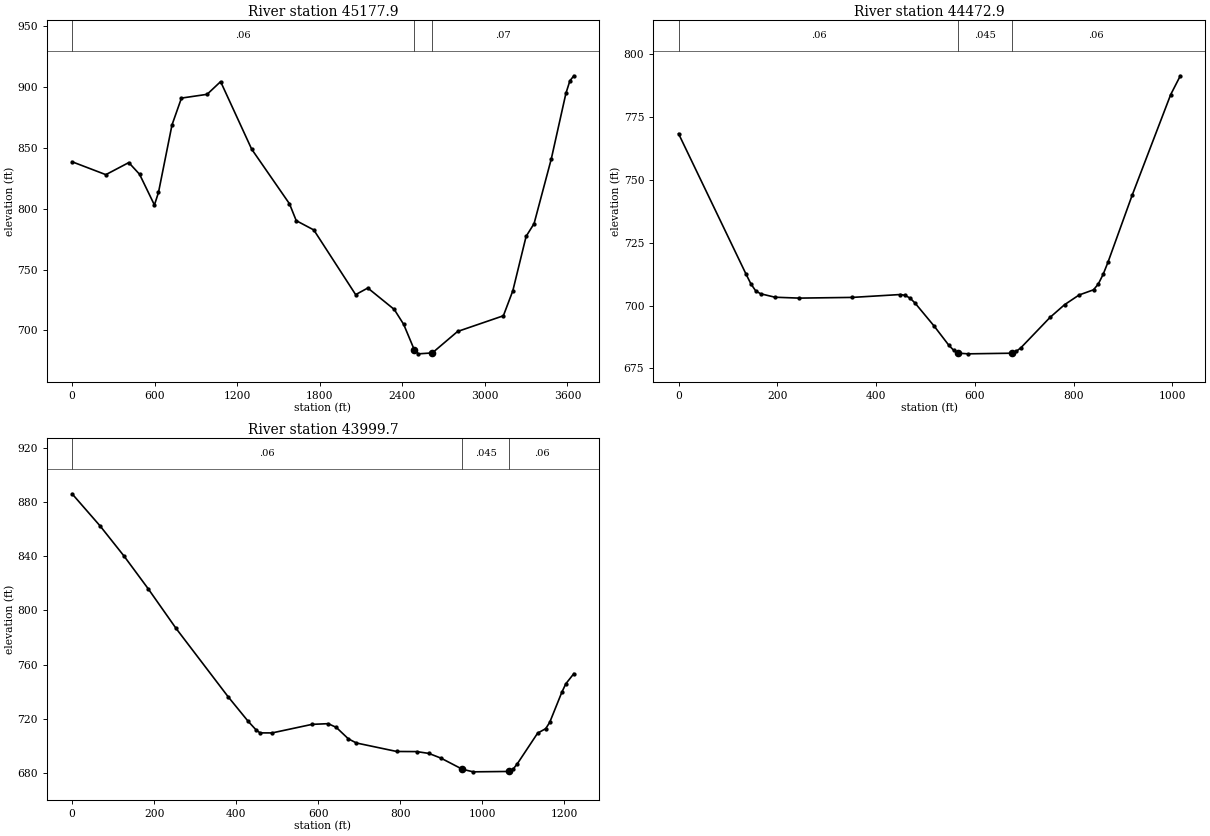
Type RM Length L Ch R = 1 ,45177.9 ,707.4,705,702.4
XS GIS Cut Line= 5
     1591513.806      347147.991     1591728.961       349286.42
     1591930.807      349283.056     1592479.084      349960.491
     1592499.917      350384.102
#Sta/Elev= 30
       0  838.62   245.4  828.02   412.2  837.94   490.7   828.3   598.6  803.07
   628.1  813.44   726.2  868.87   794.9  890.93   981.4  894.02  1079.5  904.46
  1305.2  848.98    1580  804.08  1629.1  790.23  1756.7  782.59  2060.9  729.44
  2149.2  734.89  2341.5  717.27  2409.8  705.04  2488.2  683.82  2517.6   680.8
  2618.2681.5646  2801.5  699.17  3134.5  712.08    3203  732.57  3299.7  777.32
  3357.6   787.8  3482.9  841.05  3588.9  894.82  3617.8  905.13  3646.7  909.26
#Mann= 3 , 0 , 0
       0     .06       0  2488.2    .045       0  2618.2     .07       0
Bank Sta=2488.2,2618.2
XS Rating Curve= 0 ,0
Exp/Cntr=0.3,0.1

Type RM Length L Ch R = 1 ,44472.9 ,473.1,473.2,473.1
XS GIS Cut Line= 2
     1591375.251       349656.32     1592080.546      350387.657
#Sta/Elev= 30
       0   768.4   136.8  712.46   146.5  708.64   156.3  705.84   166.1   704.7
   195.4  703.32   244.2  702.97   351.7  703.25   449.4   704.4   459.2  704.04
   468.9  702.94   478.7  701.04   517.8  691.78   547.1  684.26   556.9  682.25
   566.6  681.07   586.2   680.8   674.5681.0515   683.9  681.79   693.6   683.3
   752.2   695.3   781.6  700.35   810.9   704.2   840.2  706.27   849.9  708.58
   859.7  712.41   869.5  717.24   918.3  743.81   996.5  783.94    1016  791.42
#Mann= 3 , 0 , 0
       0     .06       0   566.6    .045       0   674.5     .06       0
Bank Sta=566.6,674.5
XS Rating Curve= 0 ,0
Exp/Cntr=0.3,0.1

Type RM Length L Ch R = 1 ,43999.7 ,335.7,337.1,338.4
XS GIS Cut Line= 3
     1591055.473      349592.435     1591234.192      350159.792
     1591657.369      350624.202
#Sta/Elev= 30
       0  885.98    68.3  862.26   126.8  839.97   185.3     816   253.5  786.63
   380.3  736.24   429.1  718.12   448.6  711.71   458.3  709.54   487.6  709.52
   585.1  715.84   624.3  716.34   643.9  713.63   673.4  705.17     693  702.09
   791.2  695.83   840.3  695.73   869.7  694.39   899.2  690.91   951.3682.7067
   977.7   680.8  1066.1  681.09  1075.9  683.11  1085.7  686.94  1134.8  709.36
  1154.4  712.66  1164.2  717.28  1193.7  739.47  1203.5  745.77  1223.1  753.29
#Mann= 3 , 0 , 0
       0     .06       0   951.3    .045       0  1066.1     .06       0
Bank Sta=951.3,1066.1
XS Rating Curve= 0 ,0
Exp/Cntr=0.3,0.1