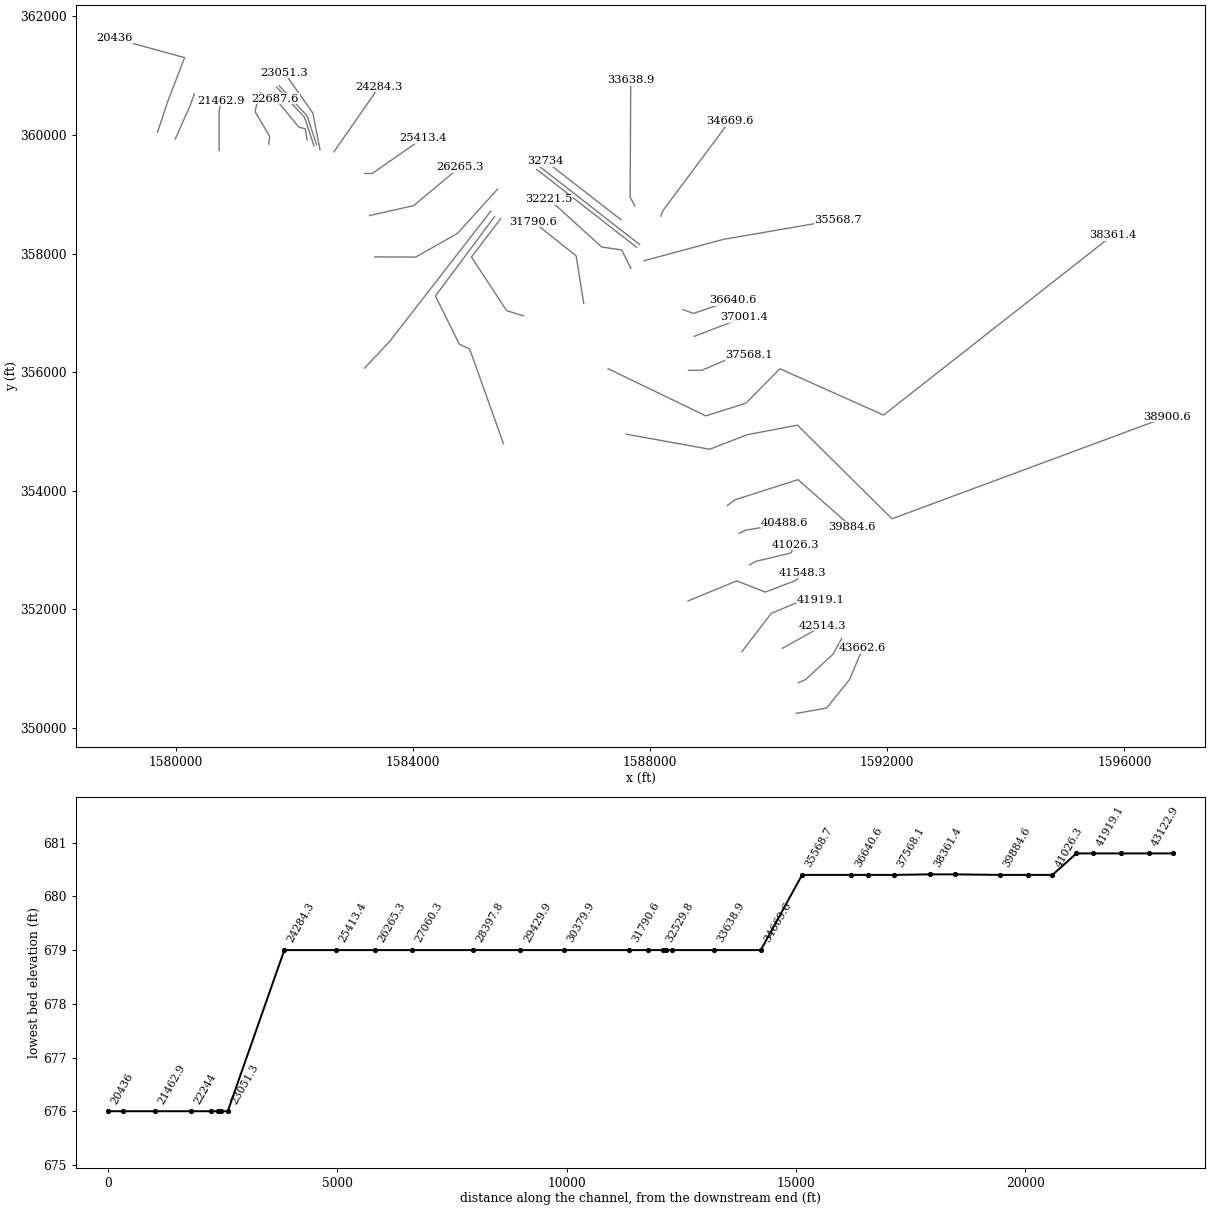
HEC-RAS study MDISLCRK_C.prj: MDISLCRK_C

--- MDISLCRK_C.g01 (geometry) --- (continued)

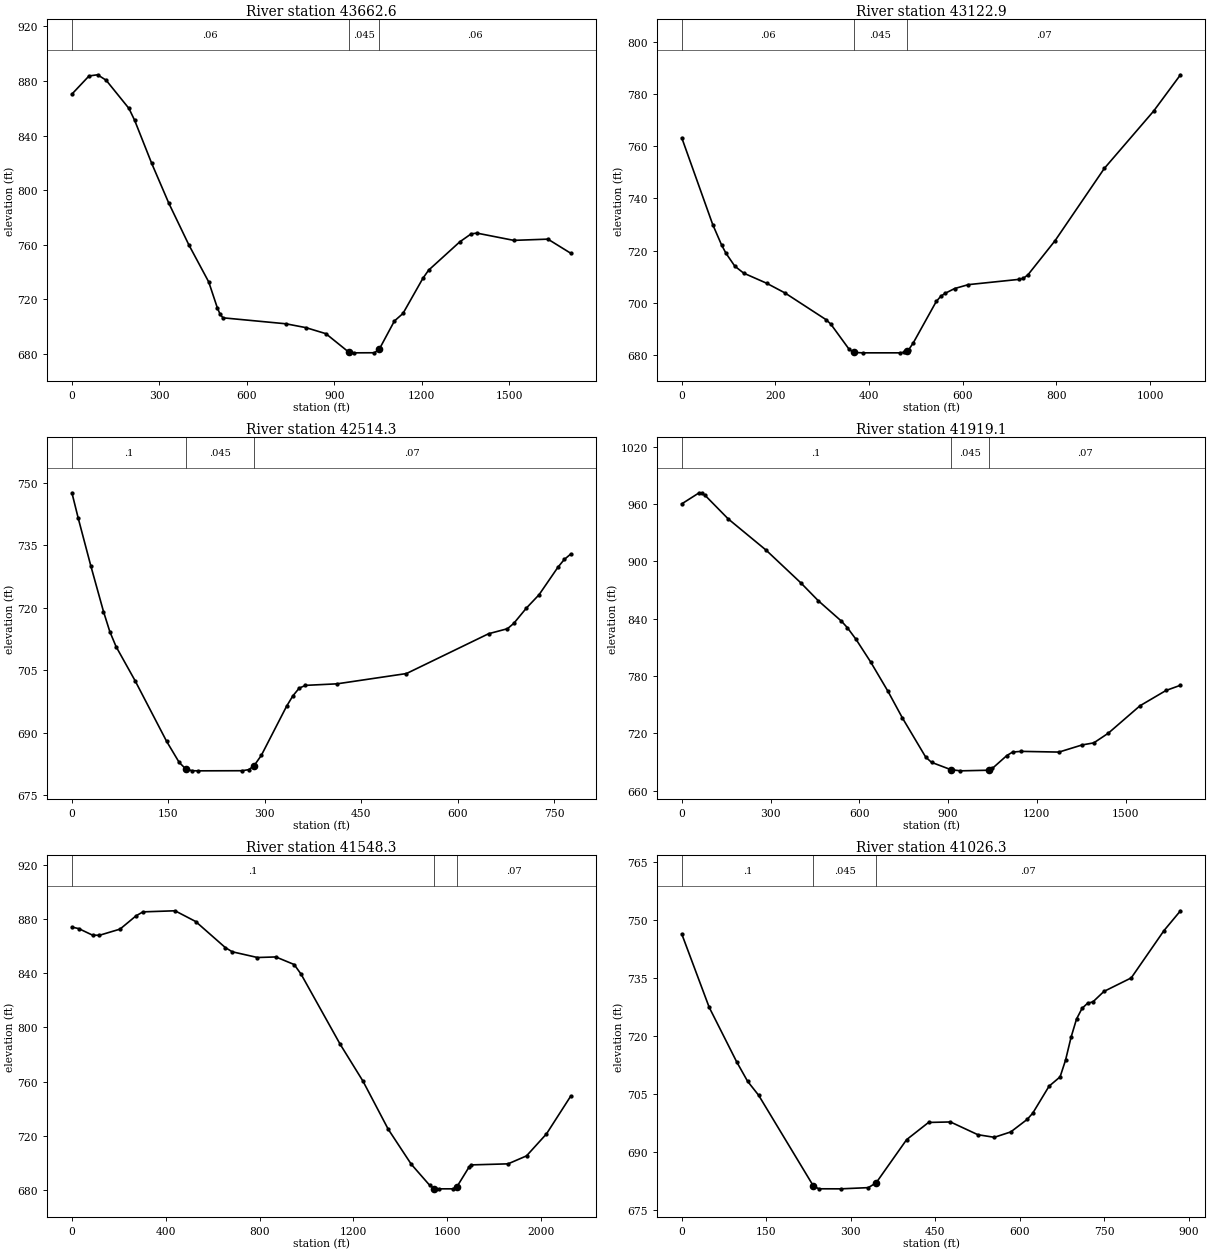
Type RM Length L Ch R = 1 ,43662.6 ,543.5,539.7,536.5
XS GIS Cut Line= 4
     1590465.195      350245.213     1590975.946      350333.403
     1591363.296      350814.316     1591585.755      351344.688
#Sta/Elev= 30
       0  870.37    58.7  883.67      88  884.53   117.4  880.55   195.6  859.88
   215.2  851.16   273.8  819.58   332.5   790.4     401  759.98   469.4  732.72
   498.8  713.83   508.5     709   518.3  706.46     734  702.09   802.6  699.28
   871.2  694.85   949.6  681.35   969.2   680.8  1037.8  680.86  1054.2683.3406
  1106.4  704.13  1135.8  709.65    1204  735.36  1223.6  741.34  1330.8  762.14
  1369.8  767.98  1389.3  768.52    1516   763.2    1633  764.11    1711  753.81
#Mann= 3 , 0 , 0
       0     .06       0   949.6    .045       0  1054.2     .06       0
Bank Sta=949.6,1054.2
XS Rating Curve= 0 ,0
Exp/Cntr=0.3,0.1

Type RM Length L Ch R = 1 ,43122.9 ,613.4,608.6,603.2
XS GIS Cut Line= 4
     1590500.685      350763.091     1590622.213      350815.174
     1591082.282      351240.521     1591232.022      351507.448
#Sta/Elev= 30
       0  763.29    66.1  730.01      85  722.18    94.4  718.99   113.3  714.04
   132.2  711.37   181.2   707.5   220.3  703.78   308.4  693.49   318.2  691.82
   357.4  682.15   367.2  680.95   386.8   680.8   465.1   680.8   474.9  680.96
   481.4681.6763   484.7  682.04   494.4  684.65   543.4   700.5   553.2  702.53
     563  703.69   582.6  705.46   611.9  706.96   719.6  708.97   729.4   709.4
   739.2  710.74     797  723.81   902.2  751.54  1007.5  773.53  1064.8  787.45
#Mann= 3 , 0 , 0
       0     .06       0   367.2    .045       0   481.4     .07       0
Bank Sta=367.2,481.4
XS Rating Curve= 0 ,0
Exp/Cntr=0.3,0.1

Type RM Length L Ch R = 1 ,42514.3 ,597.9,595.2,593
XS GIS Cut Line= 2
     1590231.588      351342.518     1590908.671      351720.122
#Sta/Elev= 30
       0  747.59     9.8  741.49    29.4  730.02    49.1  719.06    58.9  714.25
    68.7  710.62    98.1  702.48   147.2  687.89   166.8  682.81   176.6  681.32
   186.4  680.83   196.3   680.8     265  680.83   274.8  681.09   282.9681.9744
   294.4   684.5   333.7  696.31   343.5  698.81   353.3  700.66   363.1  701.33
   412.2   701.7   520.1  704.17   647.7  713.73   677.1  714.94   686.9  716.22
   706.6  719.91   726.2   723.1   755.6  729.72   765.4  731.57   775.3  732.85
#Mann= 3 , 0 , 0
       0      .1       0   176.6    .045       0   282.9     .07       0
Bank Sta=176.6,282.9
XS Rating Curve= 0 ,0
Exp/Cntr=0.3,0.1

Type RM Length L Ch R = 1 ,41919.1 ,371.4,370.8,369.7
XS GIS Cut Line= 4
     1589548.529       351286.88     1590044.956      351932.795
     1590596.171       352162.83     1590869.609       352162.83
#Sta/Elev= 30
       0  960.04    58.9  971.63    68.7  971.11    78.5  969.05     157   944.3
   284.6  911.74   402.4  877.42   461.3  858.75   539.8  837.31   559.5  830.59
   588.9  818.34     638  794.85   696.9  763.97   745.9     736   824.4  695.17
     844   689.7   909.3682.0428   941.9   680.8  1039.3681.4485  1049.6  683.33
  1098.6   696.8  1118.2  700.45  1147.6  701.16  1274.8  700.42  1353.2  707.91
  1392.4  710.04  1441.2   720.1  1548.6  748.86  1636.5  764.85  1685.4  770.31
#Mann= 3 , 0 , 0
       0      .1       0   909.3    .045       0  1039.3     .07       0
Bank Sta=909.3,1039.3
XS Rating Curve= 0 ,0
Exp/Cntr=0.3,0.1

Type RM Length L Ch R = 1 ,41548.3 ,524.8,521.9,519
XS GIS Cut Line= 5
     1588638.806      352141.047     1589460.303      352479.628
     1589942.959      352290.868     1590457.282      352486.181
     1590561.449      352618.559
#Sta/Elev= 30
       0  874.15    29.3     873    87.9  868.19   117.2  868.09     205  872.64
   273.4  882.47   302.7  885.38   439.4  886.19   527.3  878.27   654.2  858.94
   683.5  855.89   790.9  851.67     869  852.09   947.2  846.49   976.5   839.4
  1142.8  787.71  1240.6  760.28  1348.1   724.8  1446.1  698.99  1524.7  683.42
  1544.3  680.96    1564   680.8  1622.9   680.8  1639.4681.9633  1691.7  696.67
  1701.5  698.48  1858.7  699.26  1937.3  705.13  2022.5   721.4  2125.4  749.18
#Mann= 3 , 0 , 0
       0      .1       0  1544.3    .045       0  1639.4     .07       0
Bank Sta=1544.3,1639.4
XS Rating Curve= 0 ,0
Exp/Cntr=0.3,0.1

Type RM Length L Ch R = 1 ,41026.3 ,539.3,537.8,536.3
XS GIS Cut Line= 4
     1589678.202      352748.768     1589769.348      352805.191
     1590374.817      352950.591     1590444.262      353089.479
#Sta/Elev= 30
       0  746.47    48.7  727.45    97.4  713.34   116.9  708.27   136.4  704.67
   233.7  681.12   243.4  680.41   282.3   680.4     331  680.71   344.9681.9331
   399.1  693.15     438  697.61   476.9  697.74   525.6  694.43   554.8  693.76
   583.9  695.15   613.1   698.4   622.9     700     652  707.02   671.5  709.42
   681.2  713.76     691   719.7   700.7  724.42   710.4  727.16   720.2   728.5
   729.9  728.88   749.3  731.57   797.8  735.08     856  747.36   885.2  752.48
#Mann= 3 , 0 , 0
       0      .1       0   233.7    .045       0   344.9     .07       0
Bank Sta=233.7,344.9
XS Rating Curve= 0 ,0
Exp/Cntr=0.3,0.1

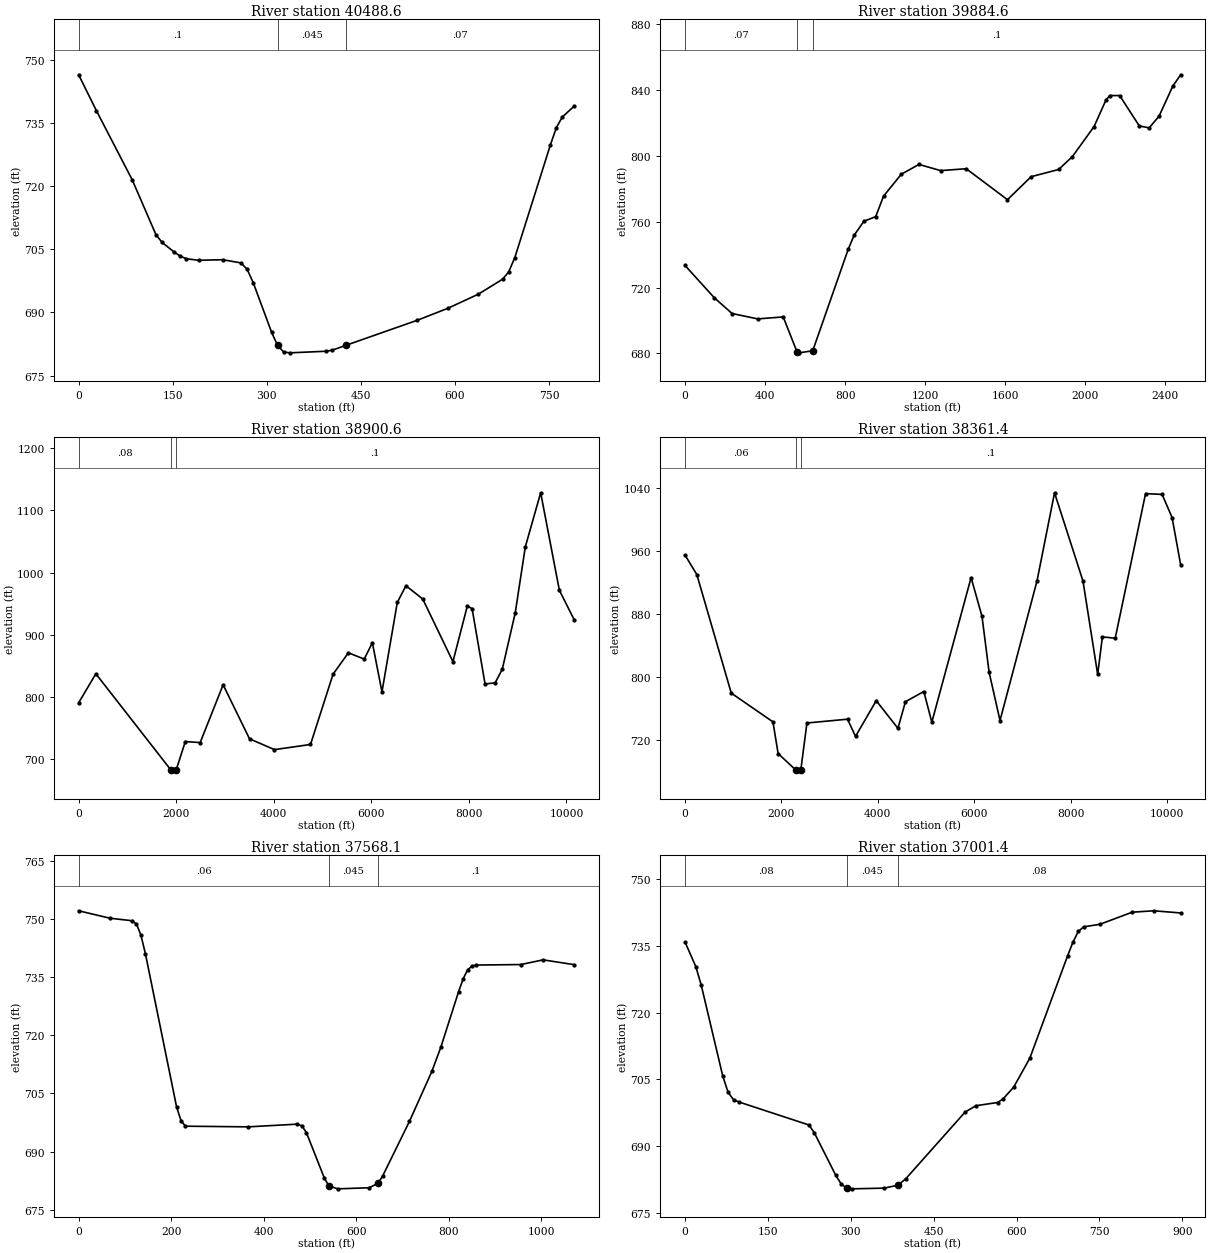
Type RM Length L Ch R = 1 ,40488.6 ,600.7,603.9,607.2
XS GIS Cut Line= 4
     1589502.421      353280.452     1589613.098      353334.705
     1590177.334      353430.191      1590266.31      353462.743
#Sta/Elev= 30
       0  746.43    28.4  737.89    85.3  721.53   123.3  708.46     133  706.63
   152.4  704.33   162.1  703.35   171.8  702.75   191.2  702.38     230  702.51
     259  701.75   268.8  700.21   278.4  697.06   307.6  685.33   317.2  682.17
   326.9  680.61   336.6   680.4   394.8  680.78   404.5  681.04   425.8682.1616
   540.3  688.15   588.8  690.98   637.3  694.32   676.1  697.89   685.8  699.62
   695.5  702.99   752.4  729.82   761.8  733.89   771.3   736.4   790.3     739
#Mann= 3 , 0 , 0
       0      .1       0   317.2    .045       0   425.8     .07       0
Bank Sta=317.2,425.8
XS Rating Curve= 0 ,0
Exp/Cntr=0.3,0.1

Type RM Length L Ch R = 1 ,39884.6 ,982.6,984.1,985.3
XS GIS Cut Line= 4
     1589302.768      353751.372     1589437.317      353849.028
     1590495.365      354186.606     1591393.802      353392.336
#Sta/Elev= 30
       0  733.47   146.7   713.8     235   704.3   362.8  701.02   490.6  702.22
   559.4  680.99   569.2   680.4     638  681.66   814.9  743.22   844.4  751.76
   893.6  760.35   952.5  763.15   991.8  775.61  1080.3  788.89  1168.7  794.88
  1276.8  791.11  1404.6  792.26    1611  773.46    1729  787.42  1866.6   791.8
  1935.4  799.66  2043.5  817.89  2102.5  833.88  2122.2  836.73  2171.3   836.7
  2269.6  818.25  2318.8  817.09  2367.9  824.12  2436.7  842.42    2476  849.34
#Mann= 3 , 0 , 0
       0     .07       0   559.4    .045       0     638      .1       0
Bank Sta=559.4,638
XS Rating Curve= 0 ,0
Exp/Cntr=0.3,0.1

Type RM Length L Ch R = 1 ,38900.6 ,540.5,539.2,537.6
XS GIS Cut Line= 6
      1587597.14      354953.547     1589004.374      354699.506
     1589637.187      354944.297     1590485.277      355105.756
     1592079.082       353526.61     1596714.666      355245.432
#Sta/Elev= 30
       0  790.02   352.6  836.82  1892.2   681.7  1921.9  680.41  2000.3  682.04
    2187  727.62  2491.1  725.92    2962  819.06  3503.2  731.99  4014.9  714.59
    4753  722.88  5215.4  836.14    5530  870.63  5854.3  860.48  6021.4  886.88
    6218  807.63  6532.5  951.77  6709.5  978.67  7053.5  957.37  7672.7  856.33
  7967.6  945.98  8065.9  941.79  8331.2  820.48  8537.6  822.12  8685.1  844.29
  8950.5  935.21  9156.9 1041.44  9471.4 1128.48  9854.7  971.41 10159.4   923.7
#Mann= 3 , 0 , 0
       0     .08       0  1892.2    .045       0  2000.3      .1       0
Bank Sta=1892.2,2000.3
XS Rating Curve= 0 ,0
Exp/Cntr=0.3,0.1

Type RM Length L Ch R = 1 ,38361.4 ,791,793.3,795.5
XS GIS Cut Line= 6
     1587291.584      356057.713     1588940.138      355262.006
     1589612.881      355474.679     1590190.138      356056.276
     1591937.093      355275.859     1595797.999      358307.932
#Sta/Elev= 30
       0  954.35   244.8  929.59   959.7  779.07  1824.3  742.59  1931.7  702.34
    2304  681.14  2344.3  680.41    2402  681.28  2529.4  741.16  3371.8  745.99
  3537.7  724.16    3968   769.5  4417.6  734.41    4574   768.2  4955.2  781.12
  5121.3  742.14  5936.2   925.8  6162.5  876.56    6310  805.59  6536.3  744.32
  7303.7  921.42  7667.7 1033.46    8258  921.44    8563  802.88  8661.3  850.53
    8927  848.77  9556.6 1032.39  9900.9 1031.37 10107.5 1001.92 10284.6  942.19
#Mann= 3 , 0 , 0
       0     .06       0    2304    .045       0    2402      .1       0
Bank Sta=2304,2402
XS Rating Curve= 0 ,0
Exp/Cntr=0.3,0.1

Type RM Length L Ch R = 1 ,37568.1 ,567.6,566.7,565.9
XS GIS Cut Line= 4
      1588649.34      356030.235     1588870.694      356030.235
     1589387.187      356251.589     1589673.645      356286.311
#Sta/Elev= 30
       0  752.13    67.4  750.22   115.5  749.56   125.1  748.72   134.7  745.85
   144.4  741.06   211.7  701.61   221.4  697.98     231  696.56   366.7  696.39
   473.2  697.09   482.9  696.65   492.6   694.9   531.4  683.17   541.1  681.17
   560.4   680.4   628.3  680.68   647.6  681.84   657.3  683.67   715.5  697.82
   763.9  710.69   783.3  716.93   821.8  731.29   831.4  734.52     841  736.87
   850.6  737.87   860.2  738.13   956.4  738.26  1004.5  739.47  1071.8  738.23
#Mann= 3 , 0 , 0
       0     .06       0   541.1    .045       0   647.6      .1       0
Bank Sta=541.1,647.6
XS Rating Curve= 0 ,0
Exp/Cntr=0.3,0.1

Type RM Length L Ch R = 1 ,37001.4 ,361.5,360.8,360
XS GIS Cut Line= 2
     1588744.826      356603.151     1589582.499      356924.332
#Sta/Elev= 30
       0  735.86    19.5  730.35    29.2  726.24    68.3  705.74      78  702.06
    87.8  700.44    97.5  699.92   224.3  694.75     234     693     273   683.4
   282.8  681.48   292.5  680.57   302.3   680.4   360.8  680.56   385.5681.2308
   399.8   682.7   507.1  697.67   526.6  699.08   565.6   699.8   575.3  700.56
   594.8  703.23   624.1  709.76   692.4  732.73   702.1  735.83   711.9  738.24
   721.6  739.28   750.9  739.85   809.4  742.57   848.4  742.89   897.1   742.4
#Mann= 3 , 0 , 0
       0     .08       0   292.5    .045       0   385.5     .08       0
Bank Sta=292.5,385.5
XS Rating Curve= 0 ,0
Exp/Cntr=0.3,0.1

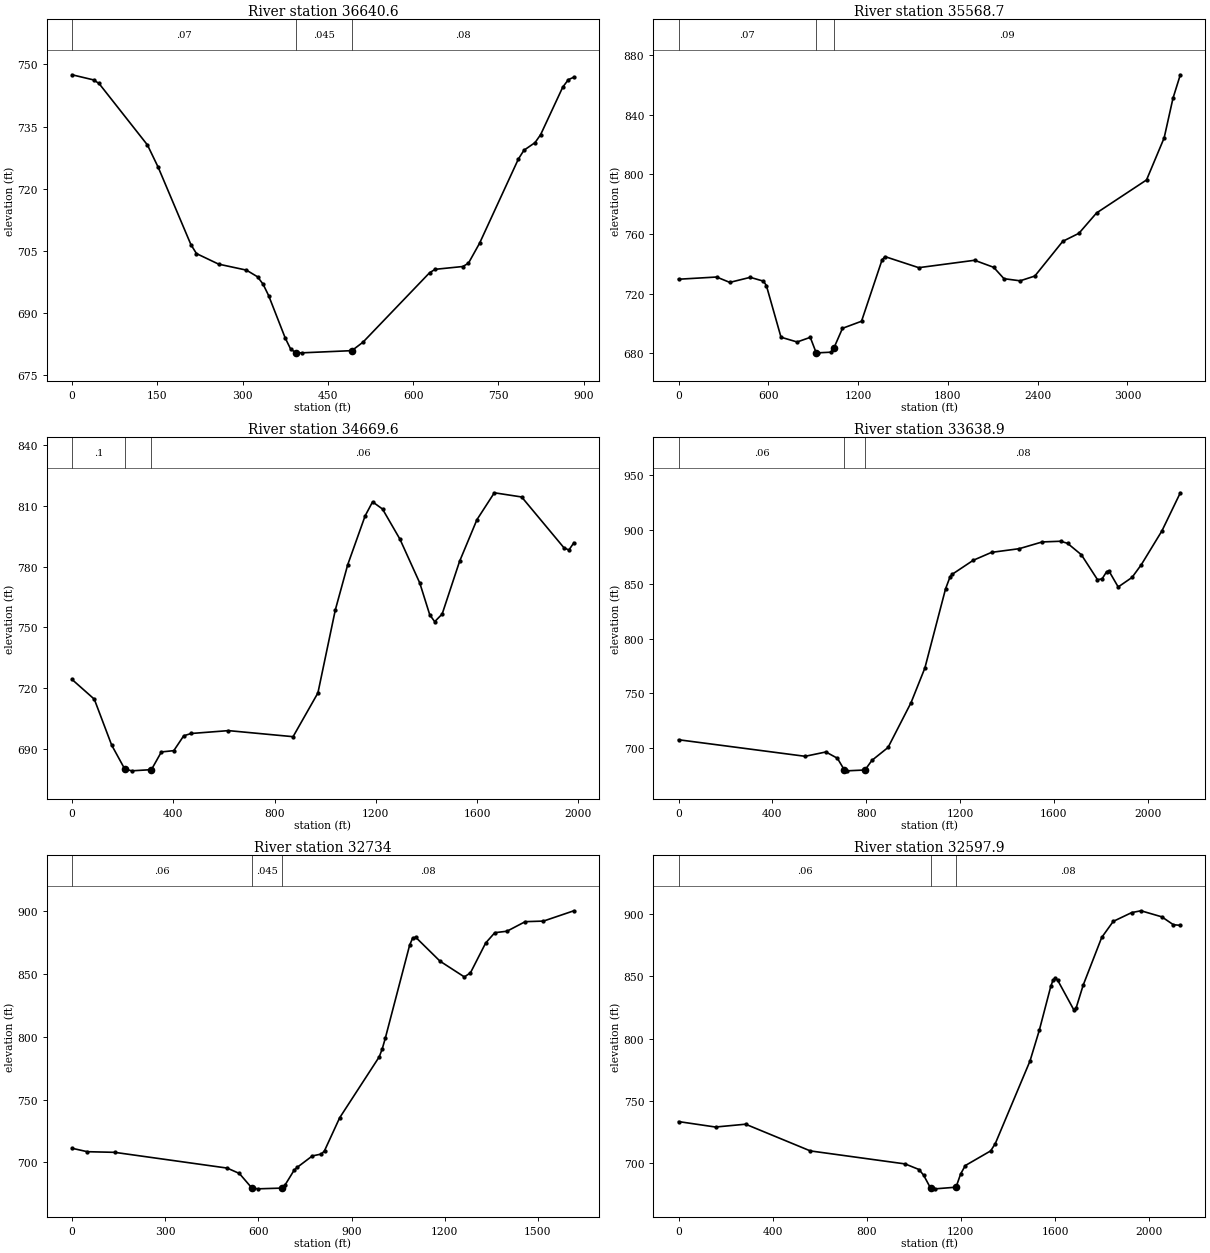
Type RM Length L Ch R = 1 ,36640.6 ,1073.2,1071.8,1070.1
XS GIS Cut Line= 3
     1588553.854       357054.54     1588731.805      356989.436
     1589387.187      357215.131
#Sta/Elev= 30
       0  747.49    37.9  746.25    47.4  745.39   132.6  730.55   151.6  725.14
     209  706.52   218.8  704.35   257.8   701.8   306.6  700.36   326.2  698.75
   335.9  696.98   345.7  694.23     375  683.95   384.7  681.24   394.5  680.42
   404.3   680.4   492.1  680.93   511.7  682.97   628.8  699.72   638.6  700.55
   687.4  701.23   697.2  702.03   716.7  706.83     785  727.16   794.8  729.28
   814.3  731.12   824.1  733.03   863.1  744.52   872.9  746.31   882.6  746.91
#Mann= 3 , 0 , 0
       0     .07       0   394.5    .045       0   492.1     .08       0
Bank Sta=394.5,492.1
XS Rating Curve= 0 ,0
Exp/Cntr=0.3,0.1

Type RM Length L Ch R = 1 ,35568.7 ,883.4,899.2,917
XS GIS Cut Line= 3
     1587898.355      357878.026     1589239.617      358239.436
     1591175.265       358572.47
#Sta/Elev= 30
       0  729.71   254.3  731.19   342.4  727.59   479.3  730.98   567.4  728.42
   586.9   725.5   684.8  690.87   792.4  687.67   880.4  690.78   919.6  680.49
   929.3   680.4  1017.4  680.83  1036.9  683.33  1095.6  696.83  1222.8  701.56
  1359.8   742.6  1379.3  744.88  1605.2  737.45  1978.3  742.41    2106  737.69
  2174.7  730.07  2282.8  728.65    2381  731.85  2567.6   755.1  2675.6  760.48
  2793.4  774.11  3127.3  796.21  3245.2  824.42  3304.1  850.94  3353.2  866.67
#Mann= 3 , 0 , 0
       0     .07       0   919.6    .045       0  1036.9     .09       0
Bank Sta=919.6,1036.9
XS Rating Curve= 0 ,0
Exp/Cntr=0.3,0.1

Type RM Length L Ch R = 1 ,34669.6 ,1017,1030.7,1042.1
XS GIS Cut Line= 3
      1588180.59      358630.061     1588215.312      358721.207
     1589341.497      360232.626
#Sta/Elev= 30
       0   724.2    87.8  714.46   156.4  691.74   207.7 679.983     235     679
   313.5  679.59   352.8  688.35   401.9  688.99   441.1  696.34   470.6  697.48
   617.8   698.9   873.1   695.9   971.2  717.53    1040  758.63    1089  780.99
  1157.8  805.18  1187.2   812.1  1226.5  808.54  1295.2  793.66  1373.7  771.94
    1413  756.24  1432.6   752.8  1462.1  756.59  1530.8  782.62  1599.5  803.28
  1668.2  816.59  1776.2  814.51  1943.1   789.4  1962.8  788.26  1982.4  791.86
#Mann= 3 , 0 , 0
       0      .1       0   207.7    .045       0   313.5     .06       0
Bank Sta=207.7,313.5
XS Rating Curve= 0 ,0
Exp/Cntr=0.3,0.1

Type RM Length L Ch R = 1 ,33638.9 ,884,904.9,925.3
XS GIS Cut Line= 3
     1587742.222      358803.672     1587664.097      358951.242
     1587673.555      360923.765
#Sta/Elev= 30
       0  707.47   539.9  692.31   628.2  696.28   677.3  690.53     707679.8143
   716.5     679     795  679.77   824.5  688.58   893.2  700.38   991.3  741.41
  1050.2  773.08  1138.5  845.67  1158.2  856.97    1168  859.17  1256.3   871.8
  1334.8  879.09  1452.6  882.45  1550.7  888.63  1629.2  889.26  1658.6  887.36
  1717.5  876.91  1786.2  854.14  1805.9  854.76  1825.5  861.49  1835.3  861.96
  1874.6  847.39  1933.4  856.09  1972.7  867.65    2061  898.73  2139.5  933.65
#Mann= 3 , 0 , 0
       0     .06       0     707    .045       0     795     .08       0
Bank Sta=707,795
XS Rating Curve= 0 ,0
Exp/Cntr=0.3,0.1

Type RM Length L Ch R = 1 ,32734   ,136.3,136.2,136.2
XS GIS Cut Line= 2
     1587512.344      358567.719     1586236.303      359559.473
#Sta/Elev= 30
       0  711.31      49  708.58   137.1  708.07   499.5  695.53   538.7  691.26
   577.9  679.99   597.5     679   675.8  679.59   685.6  681.91     715  693.78
   724.8  696.06   773.8  705.21   803.2  706.73     813  709.34   861.9  735.62
   989.3  784.13   999.1  790.59  1008.8  798.94  1087.2  873.07    1097  878.78
  1106.8  879.35  1185.2  860.28  1263.5  847.76  1283.1  851.05  1332.1   874.8
  1361.5  883.01  1400.6  884.16  1459.4  891.78  1518.2  892.24  1616.1  900.45
#Mann= 3 , 0 , 0
       0     .06       0   577.9    .045       0   675.8     .08       0
Bank Sta=577.9,675.8
XS Rating Curve= 0 ,0
Exp/Cntr=0.3,0.1

Type RM Length L Ch R = 1 ,32597.9 ,68,68,68
XS GIS Cut Line= 2
     1587824.136      358151.029     1586142.305      359462.394
#Sta/Elev= 30
       0  733.16   157.2  728.77     285  731.05   560.2  709.54   963.1  699.06
  1022.1  694.55  1041.8  689.96  1071.2  679.56  1090.9     679  1179.4  680.33
    1199  690.99  1218.7  697.74  1326.8  709.58  1346.4   715.5  1493.8  781.96
  1533.2   806.6  1582.3  842.17  1592.1  847.27    1602  848.58  1611.8  846.86
  1680.6  822.92  1690.4  824.99  1719.9  843.07  1798.5  881.42  1847.6  894.37
  1926.3  901.48  1965.6  902.91    2054  898.03  2103.2  891.67  2132.7   891.2
#Mann= 3 , 0 , 0
       0     .06       0  1071.2    .045       0  1179.4     .08       0
Bank Sta=1071.2,1179.4
XS Rating Curve= 0 ,0
Exp/Cntr=0.3,0.1

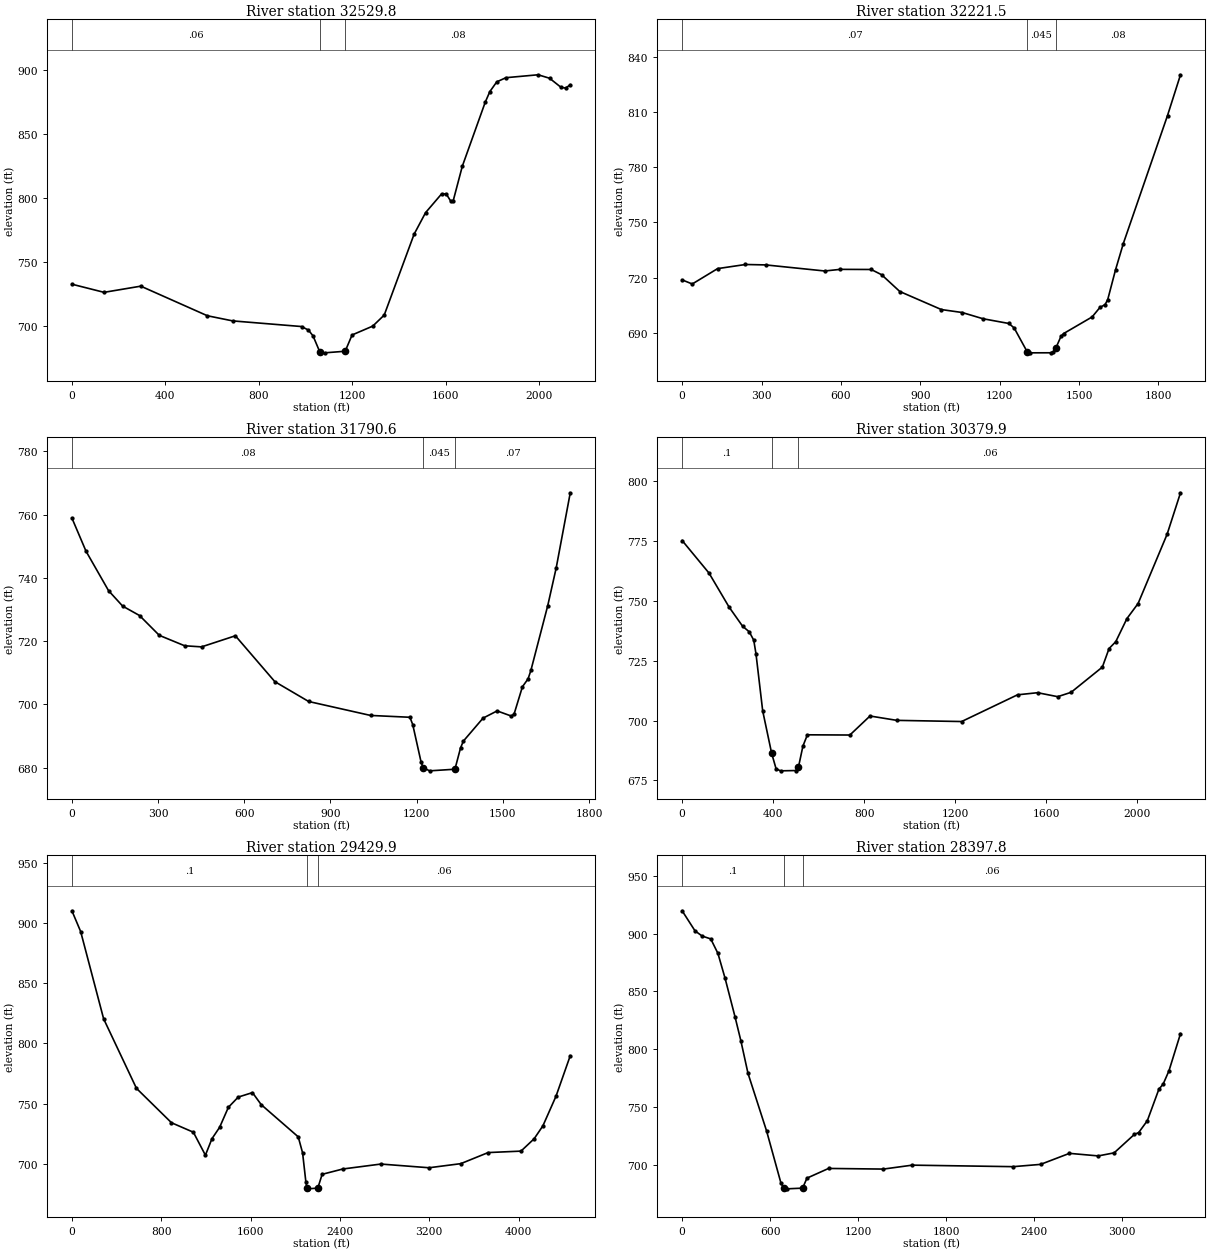
Type RM Length L Ch R = 1 ,32529.8 ,310.1,308.4,306.7
XS GIS Cut Line= 2
     1587772.053      358105.456     1586090.221      359416.821
#Sta/Elev= 30
       0  732.55   137.6   726.2   294.8  731.02   579.8  707.93     688  703.92
   982.8  699.52  1012.3  696.74  1031.9  692.24  1061.4   679.5  1081.1     679
  1169.5  680.24    1199  692.94  1287.5  699.86  1336.6  708.47  1464.4  771.55
  1513.5  788.37  1582.3  803.04    1602  802.95  1621.6  797.22  1631.4  797.38
  1670.8  824.61    1769  874.61  1788.7  882.85  1818.2  890.41  1857.5  893.66
  1995.1  895.93  2044.2  893.23  2093.4   886.1    2113  885.57  2132.7  888.14
#Mann= 3 , 0 , 0
       0     .06       0  1061.4    .045       0  1169.5     .08       0
Bank Sta=1061.4,1169.5
XS Rating Curve= 0 ,0
Exp/Cntr=0.3,0.1

Type RM Length L Ch R = 1 ,32221.5 ,429.4,430.9,432.4
XS GIS Cut Line= 4
     1587675.105      357751.747     1587521.396      358060.256
     1587184.653       358109.82     1586297.067      358914.941
#Sta/Elev= 30
       0  718.72    38.3   716.5     134  724.86   239.4  727.11     316  726.88
   539.2  723.57   597.5  724.46   714.5  724.39   753.8  721.54   822.6   712.4
   979.7  702.57  1058.3  700.96  1136.9  697.57  1235.1  694.98  1254.8  692.54
  1303.9   679.6  1313.7     679  1392.3  679.03  1402.1  679.46  1411.9  681.46
  1431.6  687.94  1441.4  689.48  1549.4  698.55  1578.9  703.71  1598.5  705.29
  1608.4  708.01  1637.8  724.17  1667.3  738.52  1834.3  808.22  1883.4  830.42
#Mann= 3 , 0 , 0
       0     .07       0  1303.9    .045       0  1411.9     .08       0
Bank Sta=1303.9,1411.9
XS Rating Curve= 0 ,0
Exp/Cntr=0.3,0.1

Type RM Length L Ch R = 1 ,31790.6 ,1417.7,1410.6,1403.3
XS GIS Cut Line= 3
     1586881.428       357157.54     1586752.638      357961.658
     1586032.152      358534.575
#Sta/Elev= 30
       0  758.95    49.1  748.46   127.6  735.98   176.6   731.1   235.5  728.11
   304.2  721.85   392.5  718.55   451.3   718.2   569.1  721.71   706.4  707.21
   824.2  700.93  1039.6  696.52  1176.7  695.94  1186.5  693.64  1215.9  681.64
  1223.1680.0016  1245.2     679  1333.4  679.51    1353  686.26  1362.8   688.4
  1431.3  695.67  1480.3  697.95  1529.2  696.34    1539  696.85  1568.4   705.6
    1588  708.08  1597.8  710.74  1656.5  731.24  1685.9  743.15  1734.9  766.93
#Mann= 3 , 0 , 0
       0     .08       0  1223.1    .045       0  1333.4     .07       0
Bank Sta=1223.1,1333.4
XS Rating Curve= 0 ,0
Exp/Cntr=0.3,0.1

Type RM Length L Ch R = 1 ,30379.9 ,952.8,950,947.3
XS GIS Cut Line= 4
     1585862.881      356950.374     1585580.763      357037.179
      1584987.33      357940.542      1585481.08      358588.459
#Sta/Elev= 30
       0  775.28   118.1  761.67   206.6  747.42   265.6  739.47   295.2   737.1
   314.8   733.6   324.6  727.94   354.1  704.06   393.4  686.36   413.1  679.81
   432.7     679   501.5  679.13   511.3  680.58     531  689.36   550.6  694.06
   737.3  693.97   825.8  701.92   943.7   700.1  1228.6  699.61  1474.2  710.78
  1562.5  711.66  1650.8     710  1709.7  711.82  1847.1  722.36  1876.6  730.12
    1906  732.98  1955.1  742.64  2004.2  748.94  2131.7  777.88  2190.6  795.23
#Mann= 3 , 0 , 0
       0      .1       0   393.4    .045       0   511.3     .06       0
Bank Sta=393.4,511.3
XS Rating Curve= 0 ,0
Exp/Cntr=0.3,0.1

Type RM Length L Ch R = 1 ,29429.9 ,1057.1,1032,1006.6
XS GIS Cut Line= 5
     1585527.721      354791.821     1584958.085      356388.642
     1584782.152      356472.943     1584380.449      357284.633
      1585376.22      358621.081
#Sta/Elev= 30
       0  910.45    78.4  893.19   284.2   820.5   578.2  762.64   891.8  734.02
  1087.8  726.13  1195.6     707  1254.4  720.76    1323  730.24  1401.4  746.88
  1489.6  755.39    1617   759.1  1695.4  749.07  2026.8  722.28  2065.8  708.97
    2095  684.91  2104.7  680.03  2114.4     679  2202.1  679.62    2241  691.09
  2426.1  695.52  2766.9  699.63  3198.1  696.55  3482.4  699.96  3727.5  709.19
  4021.6   710.4  4139.2  720.66  4217.7  731.42  4335.3  756.12  4462.8  789.83
#Mann= 3 , 0 , 0
       0      .1       0  2104.7    .045       0  2202.1     .06       0
Bank Sta=2104.7,2202.1
XS Rating Curve= 0 ,0
Exp/Cntr=0.3,0.1

Type RM Length L Ch R = 1 ,28397.8 ,1358.2,1337.5,1316.9
XS GIS Cut Line= 3
     1583187.444      356069.598     1583614.617      356525.026
      1585313.72      358714.831
#Sta/Elev= 30
       0  919.89    87.8  902.49   136.6  897.98   195.1  895.52   243.9  882.96
   292.7  861.39     361  827.74     400  807.39   448.8  779.06   575.6  729.08
   673.6   683.9   693.2  679.58   712.9     679     821  679.61   850.5  688.27
   997.9  696.67  1371.4  696.12    1568  699.52    2256  698.21  2442.7  700.19
  2639.3  709.74  2835.9  707.52    2944  710.18  3081.6  726.14  3111.1  727.76
    3170  738.01  3248.7  765.26  3278.2  769.82  3317.5  781.26  3396.1  813.44
#Mann= 3 , 0 , 0
       0      .1       0   693.2    .045       0     821     .06       0
Bank Sta=693.2,821
XS Rating Curve= 0 ,0
Exp/Cntr=0.3,0.1

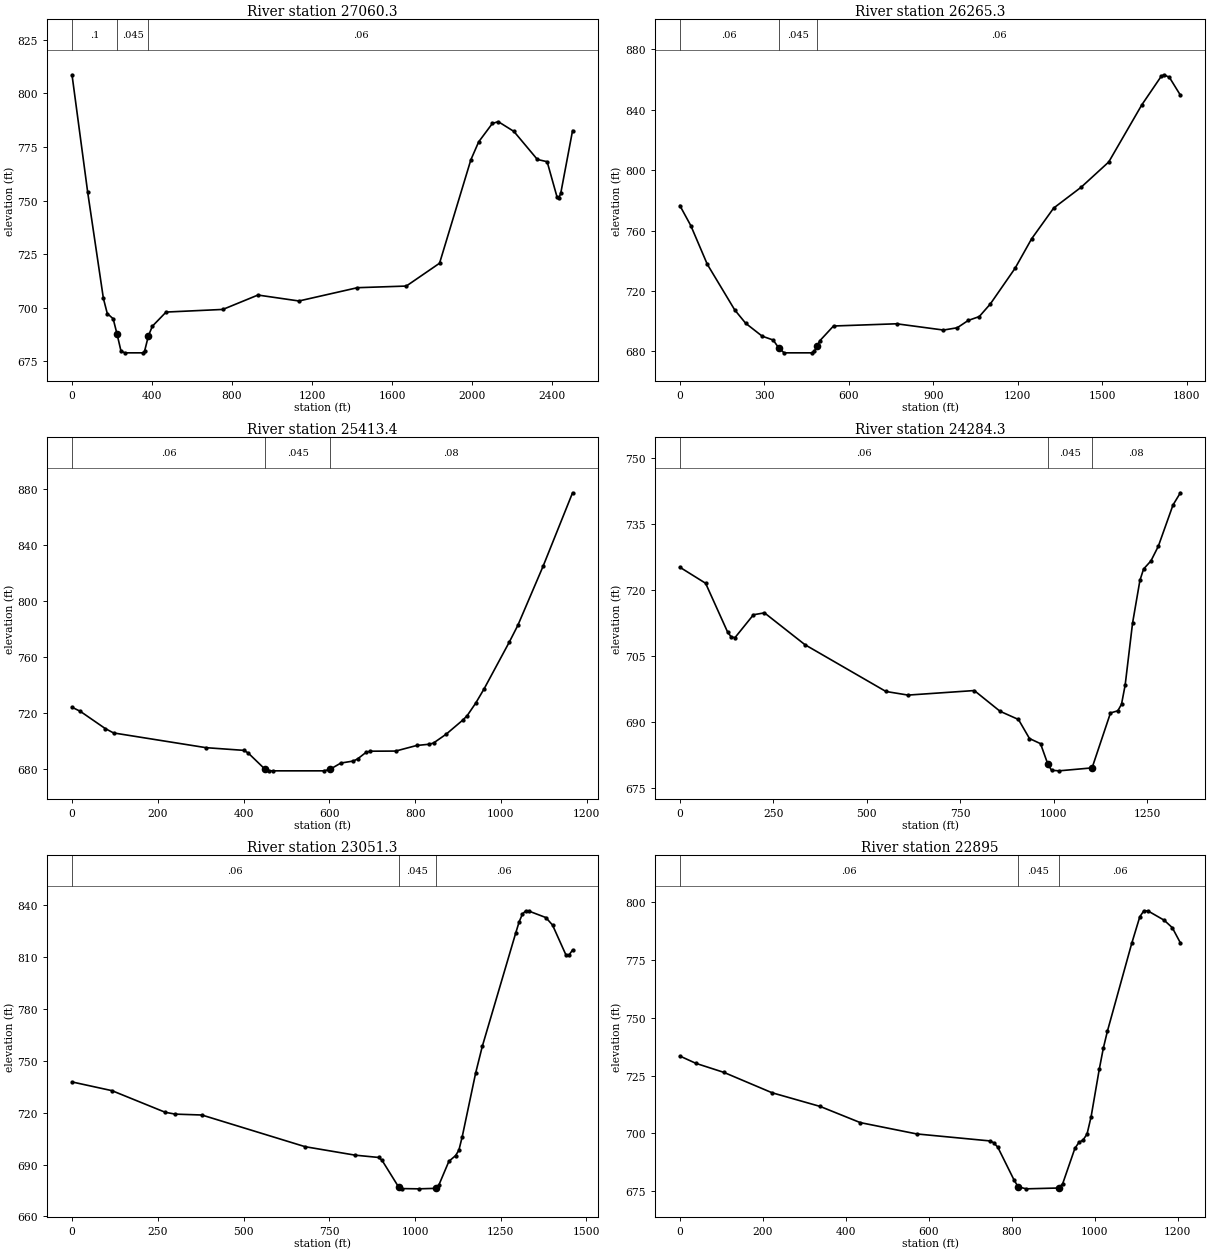
Type RM Length L Ch R = 1 ,27060.3 ,789.6,795,799.8
XS GIS Cut Line= 4
     1583358.858       357943.32     1584044.622      357939.848
     1584749.483      358337.417     1585426.219       359083.25
#Sta/Elev= 30
       0  808.71    78.4   753.9   156.8  704.42   176.3  697.34   205.7   694.9
   225.3  687.67   244.9  679.81   264.5     679   352.7     679   362.5  679.67
   382.1  686.98   401.7  691.43   470.2  698.02     754  699.25   929.5  705.96
  1134.3  703.19  1426.8  709.39    1671  710.15  1837.2   720.8  1993.7  769.05
  2032.8  777.42  2101.2  785.99  2130.6  786.85  2208.8  782.29  2326.1  769.21
    2375  768.16  2423.9  751.88  2433.7  751.12  2443.4  753.61  2502.1  782.68
#Mann= 3 , 0 , 0
       0      .1       0   225.3    .045       0   382.1     .06       0
Bank Sta=225.3,382.1
XS Rating Curve= 0 ,0
Exp/Cntr=0.3,0.1

Type RM Length L Ch R = 1 ,26265.3 ,841.3,851.9,863.1
XS GIS Cut Line= 3
     1583270.432      358640.542     1584012.099      358807.209
     1584793.349      359459.292
#Sta/Elev= 30
       0  776.62      39  763.29    97.5  737.69   194.9  707.46   233.9  698.58
   292.4  690.05   331.4   687.5   350.8  682.42   370.3     679   467.8     679
   477.5  679.95   487.3  683.23     497  686.96   545.8  696.78     770  698.25
   936.3   694.1   985.2  695.61  1024.4  700.47  1063.5  703.03  1102.6  711.34
  1190.7  735.05  1249.4  754.55  1327.7  774.92  1425.5  788.76  1523.4  805.47
  1640.8  843.32  1709.3  862.11  1719.1  863.24  1738.6  861.59  1777.8  849.74
#Mann= 3 , 0 , 0
       0     .06       0   350.8    .045       0   487.3     .06       0
Bank Sta=350.8,487.3
XS Rating Curve= 0 ,0
Exp/Cntr=0.3,0.1

Type RM Length L Ch R = 1 ,25413.4 ,1122.9,1129.1,1134.6
XS GIS Cut Line= 3
      1583189.27      359350.547     1583315.138      359350.547
     1584170.173      359945.165
#Sta/Elev= 30
       0  724.39    19.4  721.43    77.5  709.17    96.8  706.04   312.6  695.52
     401   693.6   410.8  691.74   450.1  680.15   459.9  679.02   469.8     679
   587.6     679   601.9680.1306     627  684.56   656.4  686.01   666.2  687.57
   685.9  692.23   695.7  693.01   754.7   693.1   803.8  697.09   833.3  697.99
   843.1  698.86   872.6  705.16   911.9  715.36   921.7  718.44   941.4   727.3
     961  737.49    1020     771  1039.6  782.74  1098.6  824.98  1167.3  877.35
#Mann= 3 , 0 , 0
       0     .06       0   450.1    .045       0   601.9     .08       0
Bank Sta=450.1,601.9
XS Rating Curve= 0 ,0
Exp/Cntr=0.3,0.1

Type RM Length L Ch R = 1 ,24284.3 ,1205.3,1233,1260.4
XS GIS Cut Line= 2
     1582667.886      359714.831     1583432.326      360813.221
#Sta/Elev= 30
       0  725.16    68.9  721.52   127.9  710.43   137.8  709.31   147.6  709.21
   196.8  714.38   226.3  714.81   334.6  707.59     551  696.99   610.1  696.17
   787.2   697.2   856.1   692.5   905.3  690.64   934.8  686.32   964.3  685.16
     984  680.48   993.8  679.13  1013.5     679  1102.1  679.67  1151.3  692.12
  1170.9  692.61  1180.8  694.09  1190.6  698.47  1210.3  712.47    1230  722.17
  1239.8  724.75  1259.5  726.59  1279.2  729.91  1318.5  739.27  1338.2  742.03
#Mann= 3 , 0 , 0
       0     .06       0     984    .045       0  1102.1     .08       0
Bank Sta=984,1102.1
XS Rating Curve= 0 ,0
Exp/Cntr=0.3,0.1

Type RM Length L Ch R = 1 ,23051.3 ,153.3,156.3,159.2
XS GIS Cut Line= 3
     1582433.511       359751.29     1582312.534      360370.512
     1581835.104      361047.596
#Sta/Elev= 30
       0  737.87   116.5  732.82   271.8  720.31   300.9  719.24   378.6  718.73
   679.7  700.39   825.9  695.48   894.1  694.16   903.8  692.54     952677.1392
   962.3  676.14  1011.1     676  1059.8  676.28  1069.5  678.17  1098.8  691.93
  1118.3  695.23    1128   698.4  1137.8  706.26  1176.8     743  1196.2  758.47
  1293.7  824.09  1303.5  830.44  1313.2  835.04    1323  836.93  1332.7   836.7
  1381.4  833.02  1400.9   828.7  1439.9  811.45  1449.7  811.52  1459.4  814.23
#Mann= 3 , 0 , 0
       0     .06       0     952    .045       0  1059.8     .06       0
Bank Sta=952,1059.8
XS Rating Curve= 0 ,0
Exp/Cntr=0.3,0.1

Type RM Length L Ch R = 1 ,22895   ,46.6,46.6,46.6
XS GIS Cut Line= 3
      1582376.06      359834.068     1582215.469      360320.179
     1581744.549      360830.161
#Sta/Elev= 30
       0  733.46    38.6   730.3   106.2  726.38   222.2  717.57   338.1  711.65
   434.7  704.66   570.6  699.76   746.6  696.74   756.4  695.94   766.2  693.99
   805.2  679.86     815  676.91   834.6     676   912.8  676.36   922.6  678.28
   951.9  693.51   961.7  696.11   971.5   697.1   981.2  699.71     991  707.22
  1010.6   727.7  1020.3  736.75  1030.1  744.11  1088.8  782.16  1108.3   793.7
  1118.1   796.3  1127.9  796.25    1167  792.22  1186.6  788.99  1206.1  782.41
#Mann= 3 , 0 , 0
       0     .06       0     815    .045       0   912.8     .06       0
Bank Sta=815,912.8
XS Rating Curve= 0 ,0
Exp/Cntr=0.3,0.1

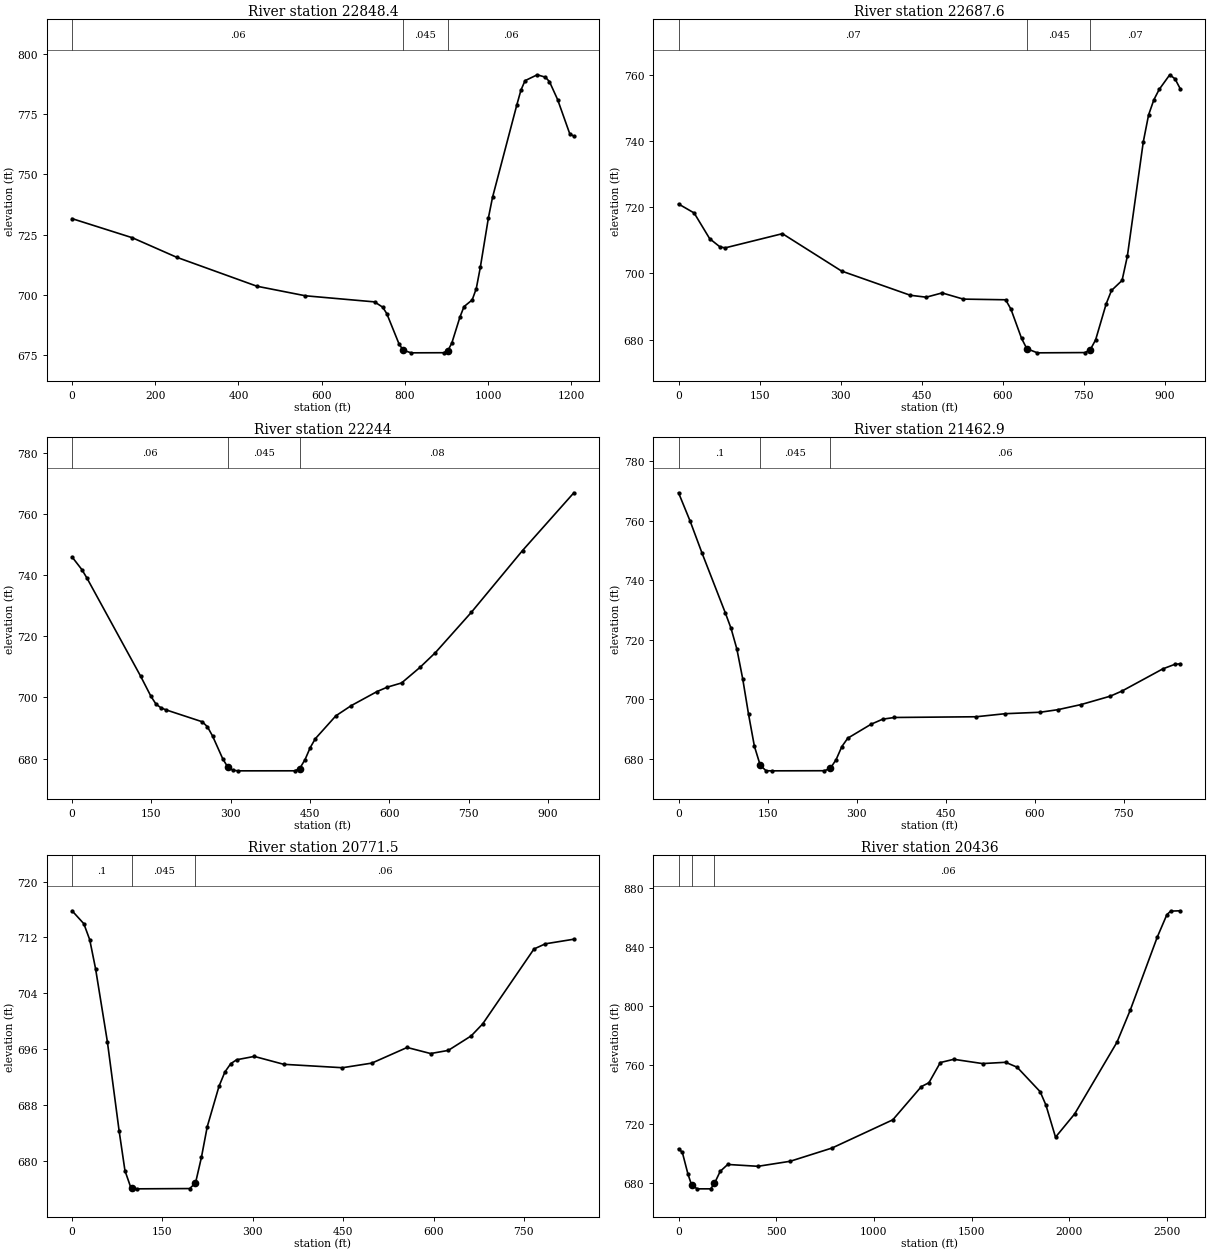
Type RM Length L Ch R = 1 ,22848.4 ,162,160.7,159.5
XS GIS Cut Line= 3
     1582332.657      359812.366     1582172.067      360298.477
     1581701.147       360808.46
#Sta/Elev= 30
       0  731.62   144.9   723.7   251.2  715.63   444.3  703.61   560.8  699.65
     727  697.12   746.6  694.93   756.4  692.27   785.7  679.77   795.5  677.12
     815     676   893.2  676.05     903  676.83   912.8  680.07   932.4  690.89
   942.1  695.16   961.7  697.93   971.5   702.6   981.2  711.38  1000.8  732.04
  1010.6  740.45  1069.2  778.88    1079  784.94  1088.8  788.81  1118.1  791.25
  1137.7  790.25  1147.4  788.42    1167     781  1196.3  766.76  1206.1  765.81
#Mann= 3 , 0 , 0
       0     .06       0   795.5    .045       0     903     .06       0
Bank Sta=795.5,903
XS Rating Curve= 0 ,0
Exp/Cntr=0.3,0.1

Type RM Length L Ch R = 1 ,22687.6 ,447.1,443.7,440.2
XS GIS Cut Line= 4
      1582217.64      359914.363     1582185.291      360104.024
     1582078.751      360129.207     1581679.445      360613.148
#Sta/Elev= 30
       0  720.97    28.9  718.25    57.7  710.48      77  707.97    86.6  707.72
   192.4     712   301.9  700.71   429.3  693.39   458.7  692.81   488.1   694.1
   527.4  692.23   605.8  692.03   615.6  689.19   635.2   680.4     645  677.26
   664.6     676   752.8  676.08   762.6  676.97   772.4  679.91     792  690.81
   801.8  694.84   821.4  697.87   831.2  705.19   860.7  739.73   870.5  747.86
   880.3  752.45   890.1  755.56   909.7     760   919.5  758.76   929.3  755.72
#Mann= 3 , 0 , 0
       0     .07       0     645    .045       0   762.6     .07       0
Bank Sta=645,762.6
XS Rating Curve= 0 ,0
Exp/Cntr=0.3,0.1

Type RM Length L Ch R = 1 ,22244   ,793.1,781.1,769
XS GIS Cut Line= 5
      1581568.35      359845.881     1581585.711      359974.354
     1581342.656      360384.076     1581346.128      360436.159
     1581432.933      360713.937
#Sta/Elev= 30
       0  745.94    18.5  741.81    27.8  739.13   129.6  706.98   149.1  700.41
   158.8  697.81   168.5  696.57   178.2  695.91   246.3  692.04     256  690.43
   265.8  687.39   285.2  679.88   294.9  677.14   304.6  676.19   314.4     676
   421.3  676.01   430.4676.6854   440.8   679.7   450.5  683.58   460.2  686.51
   499.1     694   528.2  697.33   576.9  701.92   596.3  703.36   623.4  704.74
   658.2  709.83   687.3  714.64   755.2   727.8   852.2  748.04   949.3  766.92
#Mann= 3 , 0 , 0
       0     .06       0   294.9    .045       0   430.4     .08       0
Bank Sta=294.9,430.4
XS Rating Curve= 0 ,0
Exp/Cntr=0.3,0.1

Type RM Length L Ch R = 1 ,21462.9 ,700.8,691.4,682
XS GIS Cut Line= 3
     1580732.673      359736.832     1580732.673      360405.235
     1580767.395      360578.846
#Sta/Elev= 30
       0  769.43    19.7  759.82    39.3  749.31    78.6  729.19    88.5  723.86
    98.3  716.91   108.1  706.94     118  694.95   127.8  684.27   137.6   677.9
   147.4  676.03   157.3     676   245.7  676.04   255.6   676.8   265.4  679.74
   275.2  684.17   285.1  686.97   324.4  691.66     344  693.36   363.7  693.93
   501.3  694.17   550.4   695.2   609.4  695.69   638.9  696.54   678.2  698.27
   727.4  701.09   747.1  702.81   815.9  710.26   835.6  711.75   845.4  711.98
#Mann= 3 , 0 , 0
       0      .1       0   137.6    .045       0   255.6     .06       0
Bank Sta=137.6,255.6
XS Rating Curve= 0 ,0
Exp/Cntr=0.3,0.1

Type RM Length L Ch R = 1 ,20771.5 ,333.3,335.5,337.7
XS GIS Cut Line= 3
     1579991.961      359929.215     1580248.906      360509.076
     1580314.878      360696.576
#Sta/Elev= 30
       0  715.81    19.5  713.96    29.3  711.67      39  707.52    58.6  697.07
    78.1   684.3    87.8   678.6    97.6  676.16    99.2676.1336   107.3     676
   195.2  676.04   204.9  676.83   214.7  680.49   224.4   684.9   243.9  690.68
   253.7  692.73   263.4  693.92   273.2  694.48   302.5  694.96   351.3  693.83
   448.8  693.34   497.6     694   556.2  696.24   595.2  695.37   624.5  695.82
   662.6   697.9   681.6  699.61   766.8  710.34   785.7  711.08     833  711.74
#Mann= 3 , 0 , 0
       0      .1       0    99.2    .045       0   204.9     .06       0
Bank Sta=99.2,204.9
XS Rating Curve= 0 ,0
Exp/Cntr=0.3,0.1

Type RM Length L Ch R = 1 ,20436   ,709.9,753.3,796.4
XS GIS Cut Line= 4
      1579693.35      360043.798     1579866.961      360568.104
     1580150.525      361303.373     1578965.629      361628.894
#Sta/Elev= 30
       0  703.13    19.4   700.8    48.4  685.93    67.8  678.28    96.9     676
   164.7     676   184.1  679.74   213.2  687.86   251.9  692.55     407   691.3
   571.8  694.72   785.8   703.7  1097.1  722.86  1243.1  745.39    1282  748.02
  1340.4  761.73  1409.2  763.93  1556.6  761.03  1674.6   761.9  1733.6  758.56
  1851.5  741.94    1881  732.89  1930.2  711.06  2028.5  726.92  2244.8  775.52
  2313.6  797.58  2451.2  846.89  2500.3  862.11    2520  864.52  2569.2  864.75
#Mann= 3 , 0 , 0
       0      .1       0    67.8    .045       0   184.1     .06       0
Bank Sta=67.8,184.1
XS Rating Curve= 0 ,0
Exp/Cntr=0.3,0.1