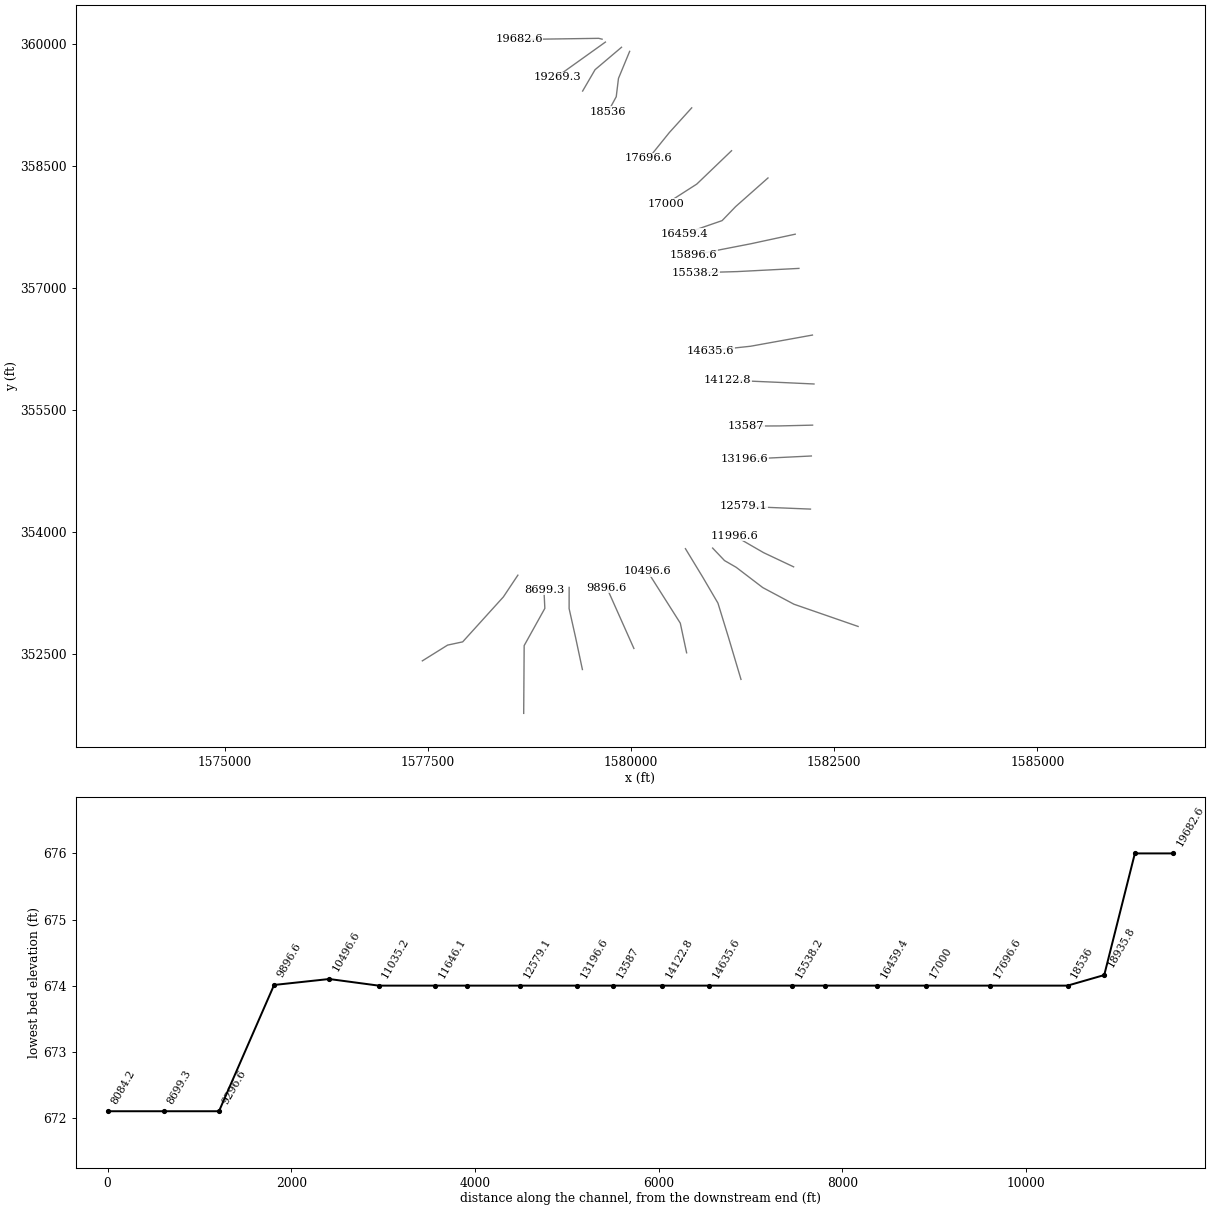
HEC-RAS study MDISLCRK_C.prj: MDISLCRK_C

--- MDISLCRK_C.g01 (geometry) --- (continued)

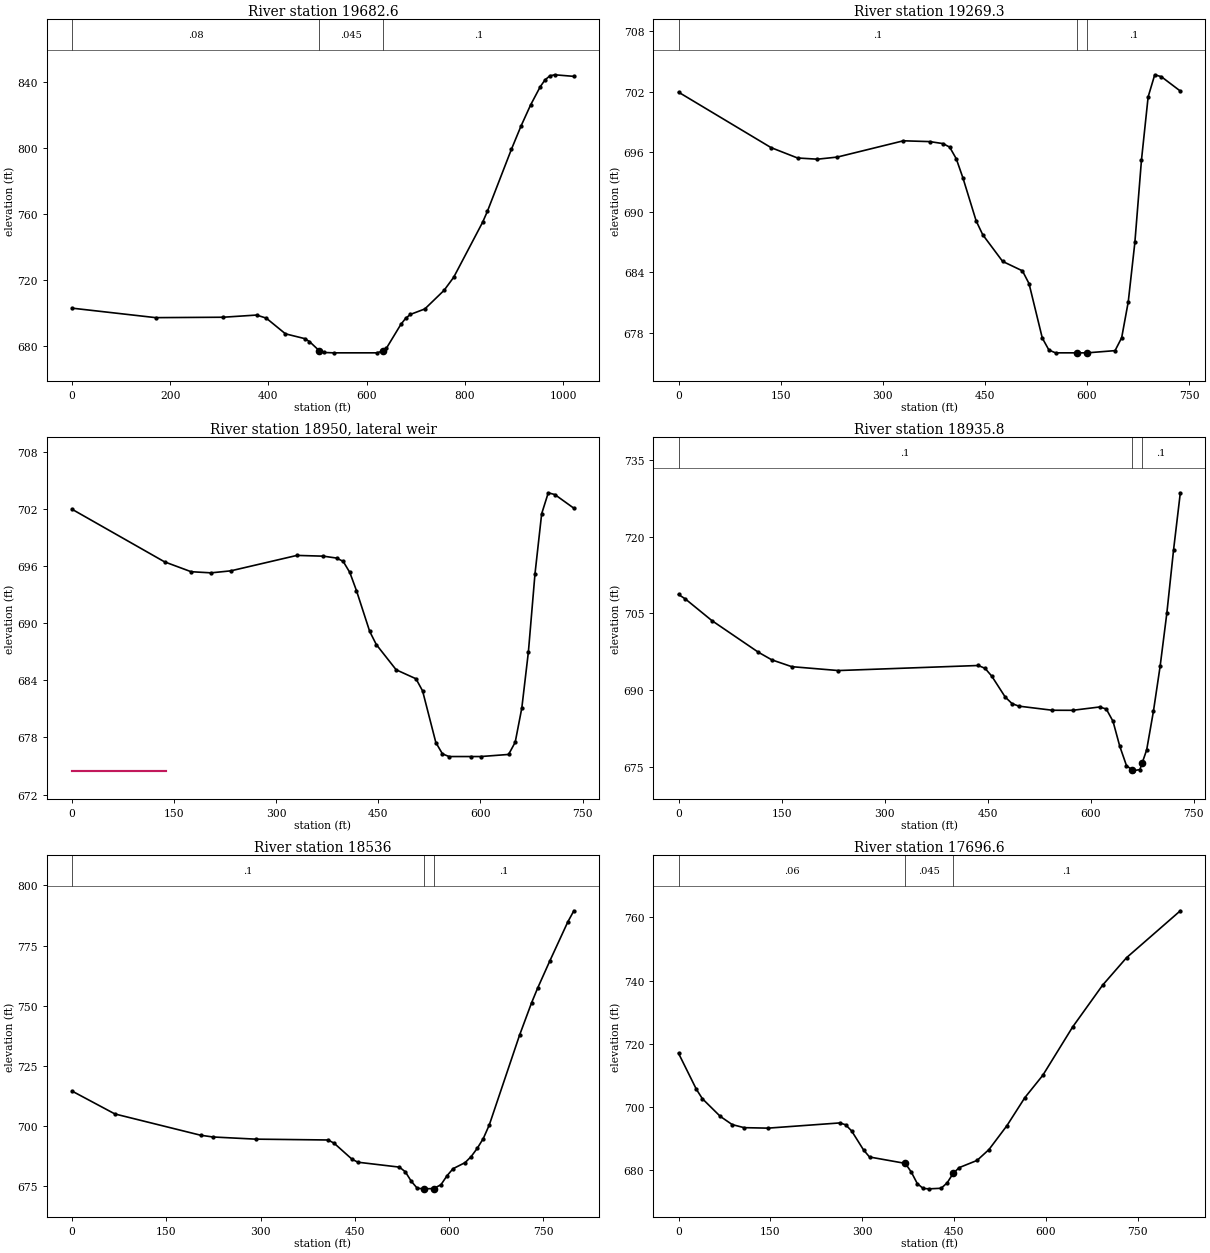
Type RM Length L Ch R = 1 ,19682.6 ,399.7,413.3,427.7
XS GIS Cut Line= 3
     1579644.739      360057.687     1579603.072      360068.104
     1578623.906      360054.215
#Sta/Elev= 30
       0  703.01   170.2  697.28   307.4  697.52   375.9  698.84   395.5     697
   434.7  687.49   473.8  684.61   483.6  682.83   503.1677.4066     513  676.22
   532.6     676   620.7     676   633.1677.1116   640.3  678.75   669.7  693.16
   679.5  696.86   689.3  699.24   718.6  702.53   757.8  713.78   777.4  721.68
   836.2  754.87     846   761.5   894.9  798.98   914.5  813.07   934.1  825.87
   953.7  836.87   963.5  841.02   973.2  843.42     983   844.1  1022.2  843.14
#Mann= 3 , 0 , 0
       0     .08       0   503.1    .045       0   633.1      .1       0
Bank Sta=503.1,633.1
XS Rating Curve= 0 ,0
Exp/Cntr=0.3,0.1

Type RM Length L Ch R = 1 ,19269.3 ,323.4,333.5,342.9
XS GIS Cut Line= 3
     1579685.451       360022.09     1579108.194      359609.763
     1579088.566      359589.929
#Sta/Elev= 30
       0  701.94     136  696.42   174.9  695.39   204.1  695.27   233.2  695.48
   330.4   697.1   369.3  697.02   388.7  696.82   398.4  696.47   408.1  695.31
   417.9   693.4   437.3  689.13     447  687.75   476.2   685.1   505.3  684.16
     515  682.89   534.5  677.47   544.2  676.28   553.9     676   585.6     676
   600.6     676   641.4  676.22   651.1   677.5   660.8  681.08   670.5  686.98
   680.2  695.18     690  701.47   699.7  703.67   709.4  703.48   737.3  702.05
#Mann= 3 , 0 , 0
       0      .1       0   585.6    .045       0   600.6      .1       0
Bank Sta=585.6,600.6
XS Rating Curve= 0 ,0
Exp/Cntr=0.3,0.1

Type RM Length L Ch R = 6 ,18950   ,,,
Node Photo=Middle_Island_Creek_Jug_bridge.jpg
BEGIN DESCRIPTION:
weir across main reach:
top of weir from terrain data; width and other data assumed per the information found from link below:
https://en.wikipedia.org/wiki/The_Jug
END DESCRIPTION:
Lateral Weir Pos= 3
Lateral Weir Distance=31.5
Lateral Weir TW Multiple XS=0
Lateral Weir WD=10
Lateral Weir Coef=2
Lateral Weir WSCriteria=-1
Lateral Weir Flap Gates= 0
Lateral Weir Hagers EQN= 0 ,,,,,
Lateral Weir SS=0.05,0.05,
Lateral Weir Type= 0
Lateral Weir Connection Pos and Dist= 0 ,
Lateral Weir SE= 2
       0   674.5     138   674.5
Lateral Weir HW RS Station=19269.3 ,-31.5
Lateral Weir TW RS Station=,0
LW Div RC= 0 ,False,

Type RM Length L Ch R = 1 ,18935.8 ,390.6,399.8,407.5
XS GIS Cut Line= 3
     1579883.802      359958.287     1579558.281       359682.68
     1579405.286      359420.093
#Sta/Elev= 30
       0  708.71     9.7  707.86    48.5   703.6   116.3  697.39   135.7  695.91
   164.8  694.57   232.6  693.81   436.3   694.8   446.1  694.25   455.9  692.72
   475.5  688.62   485.4  687.34   495.2  686.84   544.2  686.03   573.6  686.02
   612.8  686.67   622.6  686.28   632.4  683.87   642.2     679     652  675.19
   659.6  674.39   661.8  674.16   671.6  674.42   674.6   675.6   681.4  678.26
   691.2  685.79     701  694.65   710.8  705.08   720.6  717.51   730.4  728.64
#Mann= 3 , 0 , 0
       0      .1       0   659.6    .045       0   674.6      .1       0
Bank Sta=659.6,674.6
XS Rating Curve= 0 ,0
Exp/Cntr=0.3,0.1

Type RM Length L Ch R = 1 ,18536   ,853,839.3,828.4
XS GIS Cut Line= 4
     1579983.802      359908.027     1579846.128      359575.048
     1579818.744      359350.057      1579717.41      359164.357
#Sta/Elev= 30
       0   714.6    68.2   705.1   204.5  696.27     224  695.54   292.2  694.64
   407.5  694.29     417  692.95   445.3  686.34   454.8  685.06   520.9  683.02
   530.3  681.08   539.8  677.15   549.2  674.27   558.6     674   560.4     674
   575.4  674.12     587  675.71   596.6  679.42   606.2  682.36   625.4  684.89
     635  687.38   644.7  690.81   654.3  694.85   663.9  700.53     712  737.76
   731.2  751.26   740.8  757.33     760  768.52   788.9  784.88   798.5  789.49
#Mann= 3 , 0 , 0
       0      .1       0   560.4    .045       0   575.4      .1       0
Bank Sta=560.4,575.4
XS Rating Curve= 0 ,0
Exp/Cntr=0.3,0.1

Type RM Length L Ch R = 1 ,17696.6 ,698.2,696.6,693.8
XS GIS Cut Line= 3
     1580747.256      359213.475     1580472.337      358910.118
     1580214.749      358591.031
#Sta/Elev= 30
       0  716.94    29.2  705.51      39  702.54    68.2  696.95    87.7  694.35
   107.2  693.38   146.2  693.23   263.2  694.88   272.9   694.3   282.7  692.34
   302.2  686.31   311.9  684.09  370.41682.0572   380.2  679.29   389.9  675.67
   399.6  674.11   409.4     674   428.9  674.18   438.7   675.9  448.45678.8694
   458.2  680.71   487.5     683     507  686.45   536.3  694.01   565.6   702.9
   594.9  709.97   643.7   725.3   692.6  738.53   731.6  747.22   819.5  762.09
#Mann= 3 , 0 , 0
       0     .06       0  370.41    .045       0  448.45      .1       0
Bank Sta=370.41,448.45
XS Rating Curve= 0 ,0
Exp/Cntr=0.3,0.1

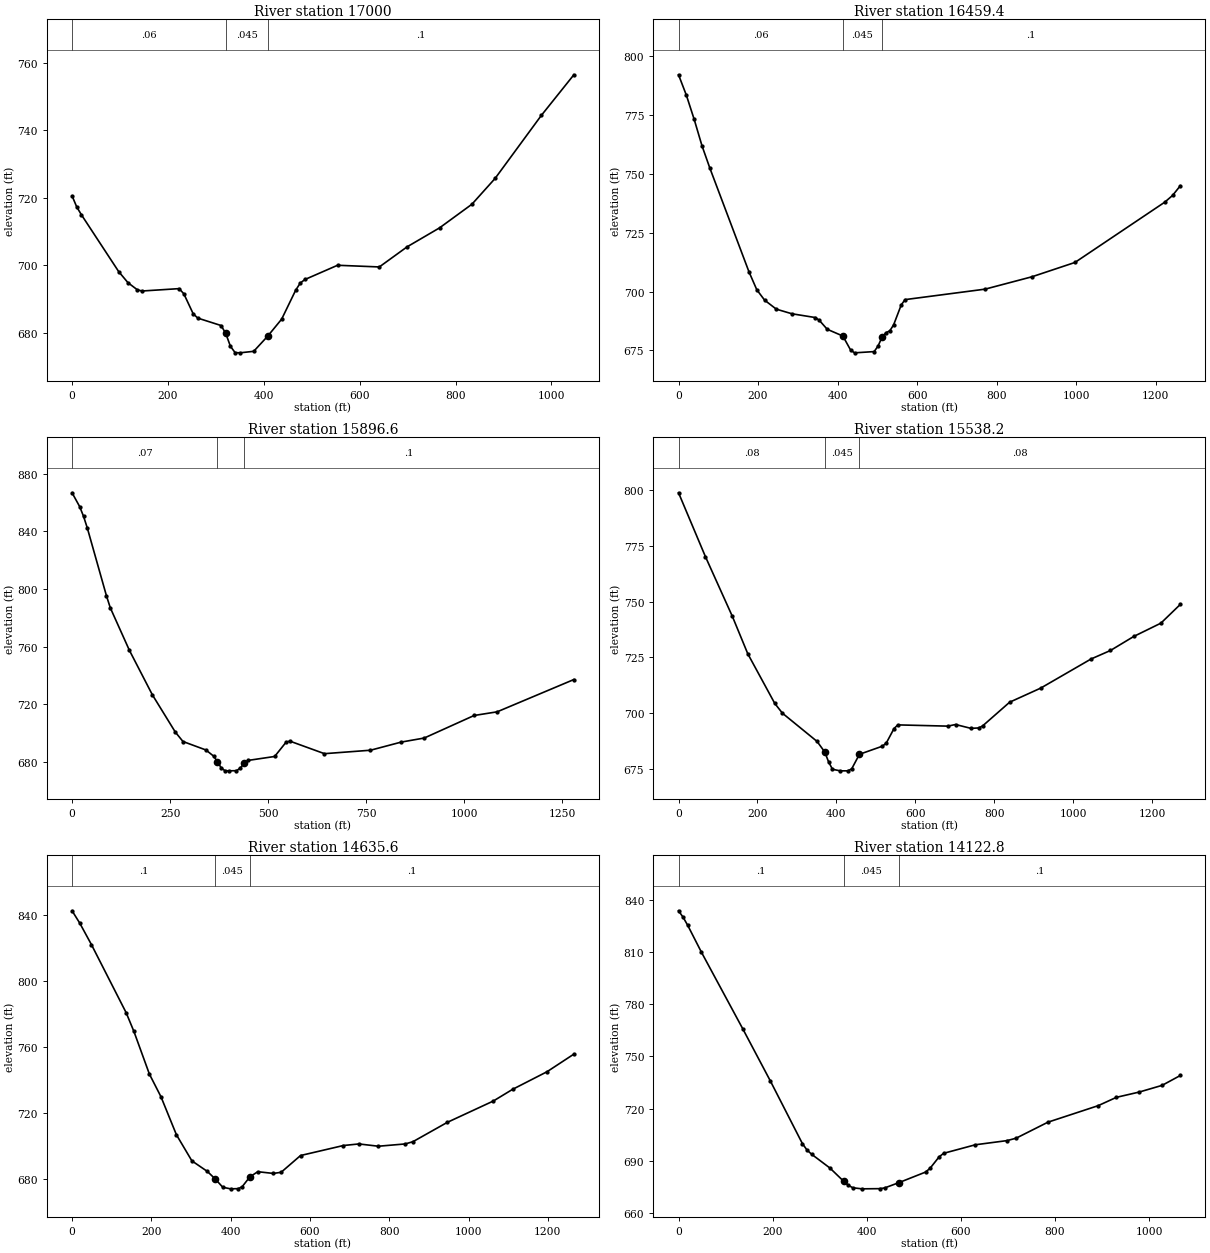
Type RM Length L Ch R = 1 ,17000   ,541.4,540.6,539.7
XS GIS Cut Line= 3
     1581237.549      358686.579     1580809.747      358276.458
     1580427.479      358031.487
#Sta/Elev= 30
       0  720.57     9.7  717.29    19.4  714.98    97.2  698.11   116.6  694.81
     136  692.72   145.7  692.34   223.4  693.05   233.2   691.5   252.6   685.6
   262.3   684.3   310.9   682.1   320.6  679.75   330.3  675.95     340  674.08
   349.8     674   378.9  674.45  408.04678.9462   437.2     684   466.3  692.54
     476  694.71   485.8  695.76   553.8  699.98   640.9  699.48   698.9  705.45
   766.5  711.07   834.1  718.09   882.4  725.74     979  744.46  1046.7  756.49
#Mann= 3 , 0 , 0
       0     .06       0   320.6    .045       0  408.04      .1       0
Bank Sta=320.6,408.04
XS Rating Curve= 0 ,0
Exp/Cntr=0.3,0.1

Type RM Length L Ch R = 1 ,16459.4 ,574.3,562.8,551.2
XS GIS Cut Line= 4
     1581685.651      358351.649     1581287.734      357999.565
     1581121.135      357827.178      1580657.18      357666.675
#Sta/Elev= 30
       0  792.18    19.7   783.5    39.4   773.2      59     762    78.7  752.54
   177.1  708.46   196.8  700.82   216.5  696.39     246  692.56   285.3   690.6
   344.4  688.99   354.2  687.79   373.9  684.02  413.25681.1449   432.9  675.15
   442.8     674     492  674.53   501.8   676.9  511.64680.5779   521.5  682.53
   531.3  683.36   540.9  685.87   560.1  694.37   569.7  696.62     771  701.07
   888.9  706.33   996.9  712.41  1222.7  738.02  1242.4  740.89    1262  745.01
#Mann= 3 , 0 , 0
       0     .06       0  413.25    .045       0  511.64      .1       0
Bank Sta=413.25,511.64
XS Rating Curve= 0 ,0
Exp/Cntr=0.3,0.1

Type RM Length L Ch R = 1 ,15896.6 ,362,358.4,354.8
XS GIS Cut Line= 4
     1582020.749      357660.265     1581620.341       357574.08
     1581477.713      357543.233     1580766.896      357405.045
#Sta/Elev= 30
       0  866.78    19.5  857.13    29.3  850.42      39  842.24    87.8  795.24
    97.5  787.01   146.3  757.49   204.8  726.69   263.3  700.86   282.8  694.34
   341.3  688.46   360.8  684.24  370.57680.4417   380.3  676.03   390.1  674.07
   399.8     674   419.3  674.11     429  675.88  438.83679.3259   448.5  681.21
   516.6  683.96   545.8  693.89   555.5  694.59   643.6   685.9     761  688.29
   839.3  693.93     898  696.74  1025.2  712.37  1083.9  714.91  1279.6   737.3
#Mann= 3 , 0 , 0
       0     .07       0  370.57    .045       0  438.83      .1       0
Bank Sta=370.57,438.83
XS Rating Curve= 0 ,0
Exp/Cntr=0.3,0.1

Type RM Length L Ch R = 1 ,15538.2 ,899.7,902.6,905.6
XS GIS Cut Line= 4
     1582066.366      357239.767     1581657.409      357218.687
     1581307.131      357200.632     1580796.435      357185.613
#Sta/Elev= 30
       0   798.9    68.2  770.18   136.5  743.33   175.5  726.55   243.8  704.28
   263.2  699.89     351   687.2   370.5  682.45   380.2  677.99     390   674.7
   409.5     674     429     674   438.7   674.9  458.25681.4244   516.7  685.09
   526.4  686.52   545.9  692.99   555.6  694.64   682.3  694.08   701.8  694.81
   740.8  693.08   760.2  693.27   770.1  694.14   838.8  704.83   917.4  711.15
  1045.2  724.25  1094.3  728.07  1153.3  734.37    1222  740.34  1271.2  748.76
#Mann= 3 , 0 , 0
       0     .08       0   370.5    .045       0  458.25     .08       0
Bank Sta=370.5,458.25
XS Rating Curve= 0 ,0
Exp/Cntr=0.3,0.1

Type RM Length L Ch R = 1 ,14635.6 ,517.8,512.8,507.7
XS GIS Cut Line= 4
     1582232.578      356420.367     1581829.606       356347.54
       1581472.3      356282.966     1580982.108      356229.819
#Sta/Elev= 30
       0   842.7    19.5  835.16    48.8   822.2   136.5  780.82     156  769.49
     195  743.65   224.2  729.89   263.2  706.82   302.2  690.98   341.2  684.57
  360.75680.0728   380.2  674.95   399.8     674   419.3  674.12   429.1  675.31
   448.5681.2639   468.4   684.4   507.6  683.35   527.3  684.03   576.3  694.21
   684.3  700.28   723.5  701.24   772.6  699.85   840.3  701.24   859.6  702.58
   946.6  714.35  1062.6  727.28    1111  734.34    1198  745.05  1265.7  755.73
#Mann= 3 , 0 , 0
       0      .1       0  360.75    .045       0   448.5      .1       0
Bank Sta=360.75,448.5
XS Rating Curve= 0 ,0
Exp/Cntr=0.3,0.1

Type RM Length L Ch R = 1 ,14122.8 ,534.4,535.8,536.9
XS GIS Cut Line= 4
     1582251.874      355818.832     1581842.903      355837.706
     1581496.775      355852.868      1581186.77      355871.133
#Sta/Elev= 30
       0  833.58     9.8  829.84    19.5  825.23    48.7  809.78   136.5  765.84
     195  735.98   263.2  699.97   272.9  696.32   282.7  693.88   321.7  685.95
  350.92678.3453   360.7  676.05   370.4  674.61   389.9     674   428.6  674.11
   438.3  674.55  467.92677.5173   524.9  683.61   534.5  685.79   553.8  692.36
   563.4  694.39   630.8  699.29   698.1  701.68   717.4  703.06     785  712.25
   891.7  721.72   930.6  726.52   979.1  729.55  1027.6  733.38  1066.4  739.05
#Mann= 3 , 0 , 0
       0      .1       0  350.92    .045       0  467.92      .1       0
Bank Sta=350.92,467.92
XS Rating Curve= 0 ,0
Exp/Cntr=0.3,0.1

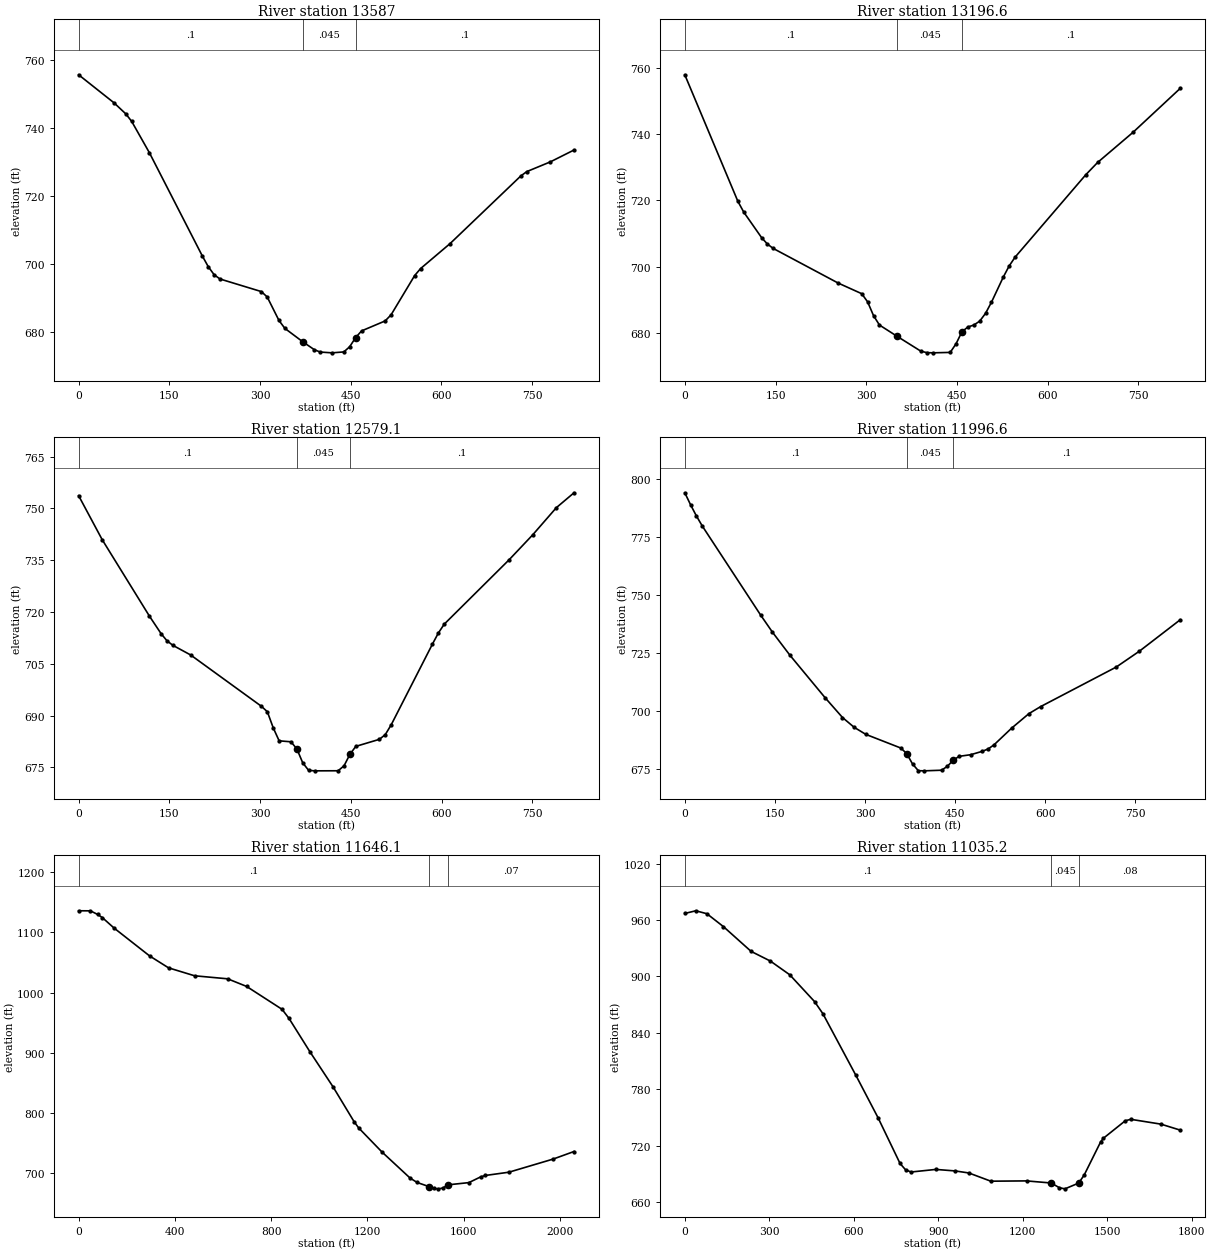
Type RM Length L Ch R = 1 ,13587   ,389.6,390.4,391.3
XS GIS Cut Line= 3
     1582234.546      355312.871     1581825.262      355303.246
     1581415.295      355301.703
#Sta/Elev= 30
       0  755.65    58.5  747.42      78  744.18    87.7  741.98     117  732.78
   204.7  702.41   214.4  699.31   224.2  696.92   233.9  695.68   302.2  691.99
   311.9  690.41   331.4   683.5   341.2  681.17  370.41677.2887   389.9  674.92
   399.6  674.23   419.2     674   438.7  674.27   448.4  675.81   458.2  678.48
     468  680.44     507  683.37   516.8  685.16   555.8  696.69   565.6  698.74
   614.4  706.08   731.5  725.96   741.3  727.22   780.3  730.08   819.4  733.56
#Mann= 3 , 0 , 0
       0      .1       0  370.41    .045       0   458.2      .1       0
Bank Sta=370.41,458.2
XS Rating Curve= 0 ,0
Exp/Cntr=0.3,0.1

Type RM Length L Ch R = 1 ,13196.6 ,619.6,617.6,615.5
XS GIS Cut Line= 3
     1582219.275      354933.676     1581810.261      354913.724
     1581401.247      354893.772
#Sta/Elev= 30
       0  757.83    87.8  719.65    97.5  716.41   126.8  708.77   136.5   706.8
   146.2  705.47   253.5  695.04   292.5  691.83   302.2  689.38     312  685.22
   321.8  682.38     351  678.98     390  674.53   399.8  674.07   409.5     674
   438.8  674.13   448.5  676.75  458.25680.3773     468  681.79   477.8  682.38
   487.5  683.55   497.2  685.91     507  689.27   526.5  696.83   536.2  700.18
     546  702.84     663  727.71   682.5   731.4     741  740.48     819  753.72
#Mann= 3 , 0 , 0
       0      .1       0     351    .045       0  458.25      .1       0
Bank Sta=351,458.25
XS Rating Curve= 0 ,0
Exp/Cntr=0.3,0.1

Type RM Length L Ch R = 1 ,12579.1 ,591.5,582.4,571.5
XS GIS Cut Line= 3
     1582208.399      354280.766     1581799.235      354297.355
     1581390.071      354313.944
#Sta/Elev= 30
       0  753.67      39  740.92     117  718.81   136.5  713.68   146.2  711.63
     156  710.32   185.2  707.55   302.2  692.69     312  691.11   321.8  686.42
   331.5  682.69     351  682.41  360.75680.3704   370.5  676.32   380.2  674.15
     390     674     429  674.02   438.8  675.46   448.5  678.77   458.2  681.08
   497.2  683.12     507  684.49   516.8  687.34     585  710.72   594.8  713.93
   604.5  716.48   711.8  735.13   750.8  742.35   789.8   750.2     819  754.51
#Mann= 3 , 0 , 0
       0      .1       0  360.75    .045       0   448.5      .1       0
Bank Sta=360.75,448.5
XS Rating Curve= 0 ,0
Exp/Cntr=0.3,0.1

Type RM Length L Ch R = 1 ,11996.6 ,355.3,350.5,347.6
XS GIS Cut Line= 3
     1582001.093      353570.881     1581631.838      353745.059
     1581271.211      353953.342
#Sta/Elev= 30
       0  794.12     9.7  788.89    19.4  784.07    29.2  779.72   126.4  741.23
   145.8  733.94     175  723.94   233.3  705.67   262.5  697.04   281.9  692.81
   301.3  689.76   359.7  683.84  369.39681.4525   379.1  676.97   388.8  674.06
   398.6     674   427.6  674.27   437.3  676.02  447.01678.6217   456.7  680.26
   476.1  680.98   495.4  682.44   505.1  683.48   514.8  685.24   543.9   692.4
   572.9  698.72   592.3  701.74   718.2  718.83   756.9  725.71   824.7  739.25
#Mann= 3 , 0 , 0
       0      .1       0  369.39    .045       0  447.01      .1       0
Bank Sta=369.39,447.01
XS Rating Curve= 0 ,0
Exp/Cntr=0.3,0.1

Type RM Length L Ch R = 1 ,11646.1 ,621.5,610.8,599
XS GIS Cut Line= 6
     1582794.522      352838.084     1582004.592      353111.522
     1581621.332      353315.913     1581294.794      353564.843
     1581150.697      353648.177     1581004.531      353801.652
#Sta/Elev= 30
       0 1135.72    49.2 1135.62    78.7 1129.69    98.3 1124.49   147.5 1106.97
     295 1060.76   373.7 1040.98   481.9 1027.79   619.6 1022.74   698.2 1010.12
   845.6  972.11   874.5  957.03   961.4  901.66  1057.9  843.19  1144.8  785.69
  1164.1  775.18  1260.6  735.33  1377.8   691.9  1407.1  684.58    1456  677.78
  1475.6  674.66  1495.1     674  1514.7  675.35  1534.2   680.6  1622.2  684.34
  1671.1  693.85  1690.7   696.2  1788.6  701.62  1972.6  723.44  2059.3     736
#Mann= 3 , 0 , 0
       0      .1       0    1456    .045       0  1534.2     .07       0
Bank Sta=1456,1534.2
XS Rating Curve= 0 ,0
Exp/Cntr=0.3,0.1

Type RM Length L Ch R = 1 ,11035.2 ,537.9,538.6,539
XS GIS Cut Line= 5
     1581353.454      352187.212     1581199.429      352704.142
     1581070.072      353124.871     1580882.718      353444.536
     1580669.985      353794.286
#Sta/Elev= 30
       0  967.06    39.2  969.89    78.5  966.75   137.3     953   235.4  926.69
     304  916.36   372.7   901.8   460.9  873.23   490.4  860.37   607.9  794.61
   686.1  749.79   764.4  701.02   783.9  694.29   803.5  691.91   891.5  694.66
     960  693.06  1008.8  690.89  1086.8  682.14  1213.6  682.45  1301.3  680.21
  1330.6  675.14  1350.1     674  1398.8  680.12  1418.3  688.64  1476.8  723.92
  1486.5  727.79  1564.5  746.47    1584  747.97  1691.2  742.84  1759.4  736.49
#Mann= 3 , 0 , 0
       0      .1       0  1301.3    .045       0  1398.8     .08       0
Bank Sta=1301.3,1398.8
XS Rating Curve= 0 ,0
Exp/Cntr=0.3,0.1

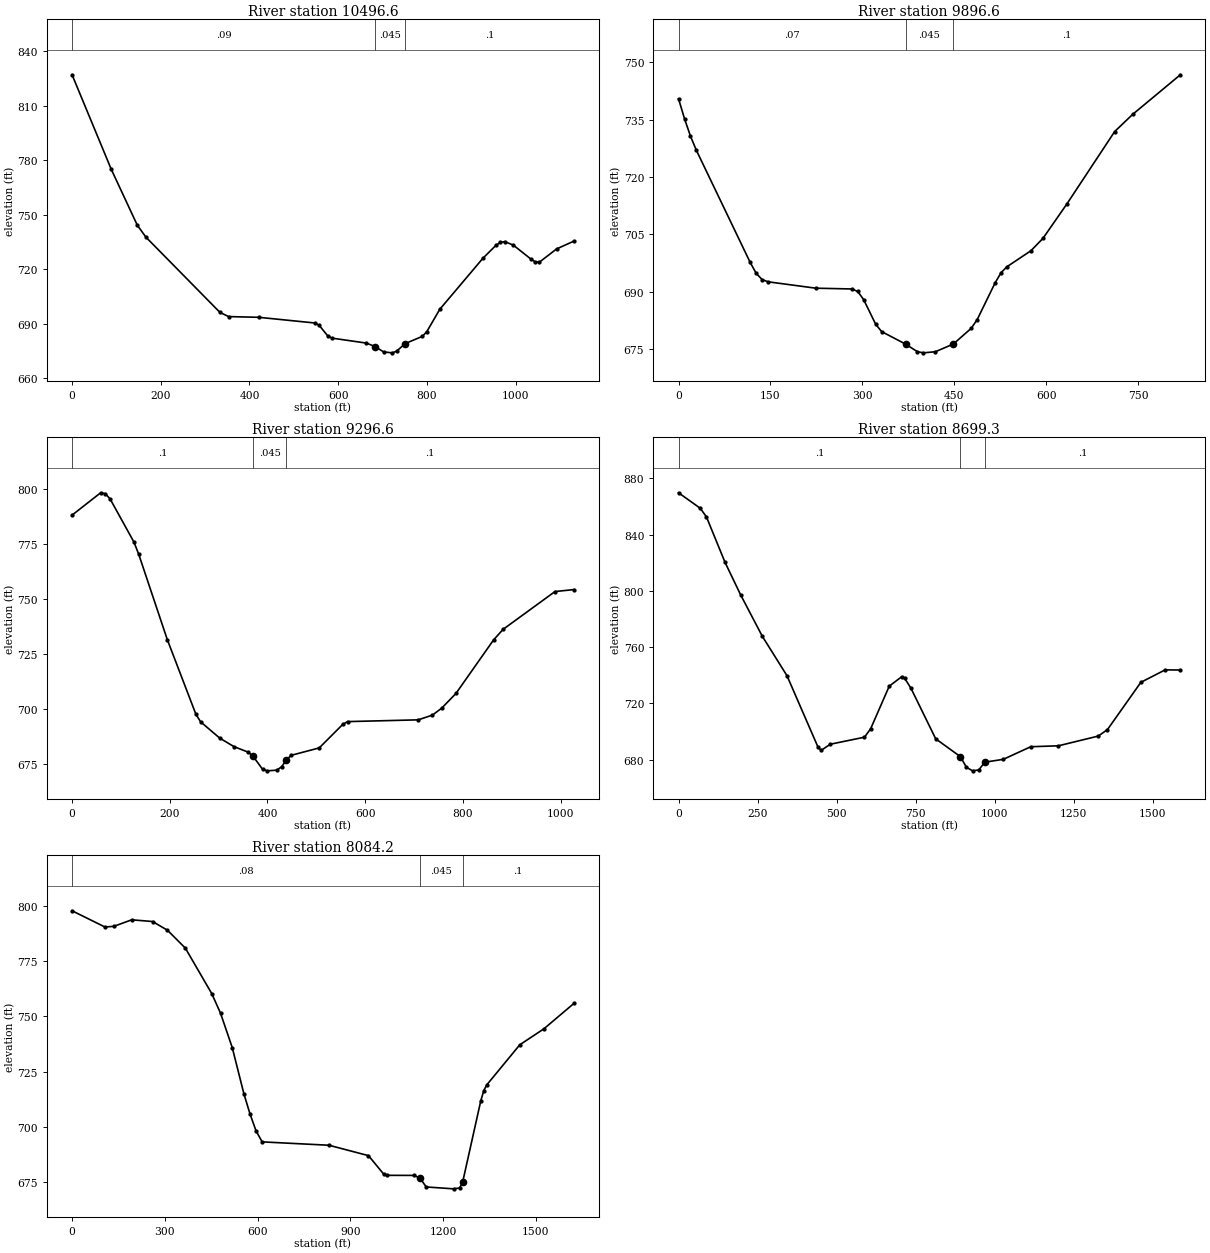
Type RM Length L Ch R = 1 ,10496.6 ,603.2,600,596.7
XS GIS Cut Line= 4
     1580684.609      352514.249     1580606.804       352878.66
     1580419.771      353173.598     1580200.466      353519.424
#Sta/Elev= 30
       0  826.89    88.2  775.04   147.1  744.22   166.7  737.62   333.4  696.33
     353  694.02   421.1  693.62   547.2  690.51     557  689.27   576.4  683.44
     586  682.19   663.7  679.45   683.1  677.57   702.5   674.6   721.9   674.1
   731.6  674.99   751.1  679.18   790.1  683.19   799.9  685.78   829.1  698.03
   926.6  726.13   955.9  733.23   965.6  734.78   975.4  735.22   994.9   733.3
  1033.9  725.75  1043.6   724.2  1053.4  723.87  1092.4  731.18  1131.4  735.48
#Mann= 3 , 0 , 0
       0     .09       0   683.1    .045       0   751.1      .1       0
Bank Sta=683.1,751.1
XS Rating Curve= 0 ,0
Exp/Cntr=0.3,0.1

Type RM Length L Ch R = 1 ,9896.6  ,604.7,600,595.5
XS GIS Cut Line= 3
     1580035.909      352567.663     1579869.007      352941.607
     1579702.104      353315.551
#Sta/Elev= 30
       0  740.44     9.8  735.19    19.5  730.66    29.2  726.93     117  697.63
   126.8  694.78   136.5  693.16   146.2  692.58   224.2  690.91   282.8  690.71
   292.5  690.06   302.2  687.91   321.8  681.48   331.5  679.56   370.5   676.3
     390   674.3   399.8  674.01   419.2   674.3   448.5  676.31   477.8  680.43
   487.5  682.72   516.8  692.34   526.5  694.98   536.2  696.54   575.2  700.71
   594.8  703.94   633.8  712.93   711.8  731.86     741  736.33     819  746.71
#Mann= 3 , 0 , 0
       0     .07       0   370.5    .045       0   448.5      .1       0
Bank Sta=370.5,448.5
XS Rating Curve= 0 ,0
Exp/Cntr=0.3,0.1

Type RM Length L Ch R = 1 ,9296.6  ,613.6,597.4,581.2
XS GIS Cut Line= 4
     1579402.491      352308.661     1579317.138      352709.162
     1579239.049      353057.386     1579239.313      353318.129
#Sta/Elev= 30
       0  788.19    58.5  798.34    68.2  797.92      78  795.48   126.8   775.9
   136.5  770.37     195  731.63   253.5  697.76   263.2  694.33   302.2  686.97
   331.5  683.08   360.8  680.56   370.5   678.7     390   672.8   399.7   672.1
   419.1  672.41   428.8  673.94  438.75676.9802   448.1  679.12     506  682.52
   554.2  693.22   563.8  694.45   708.5  695.25   737.4  697.38   756.7  700.58
   785.7  707.22   862.9  731.58   882.2  736.33   988.5   753.5  1027.1  754.39
#Mann= 3 , 0 , 0
       0      .1       0   370.5    .045       0  438.75      .1       0
Bank Sta=370.5,438.75
XS Rating Curve= 0 ,0
Exp/Cntr=0.3,0.1

Type RM Length L Ch R = 1 ,8699.3  ,620.1,615.1,610
XS GIS Cut Line= 4
     1578680.184      351769.447     1578685.978      352602.674
       1578940.4      353060.332     1578929.155        353290.7
#Sta/Elev= 30
       0  869.75    68.6  858.77    88.2  852.64     147  820.36   196.1  797.35
   264.7  767.88   343.1  739.72   441.1  689.04   450.9  686.62   480.3  691.03
   588.2  696.01   607.8  702.02   666.6  732.28   705.8  738.97   715.6  737.83
   735.2  730.86   813.6  694.86   891.4  682.24   910.8  674.64   930.2   672.1
   949.6  672.72     969  678.26  1027.2  680.26  1114.4  689.24  1201.7  689.89
  1327.8  696.81  1356.9   701.4  1462.6  735.01  1539.5  743.86  1587.5  743.78
#Mann= 3 , 0 , 0
       0      .1       0   891.4    .045       0     969      .1       0
Bank Sta=891.4,969
XS Rating Curve= 0 ,0
Exp/Cntr=0.3,0.1

Type RM Length L Ch R = 1 ,8084.2  ,403.1,417.2,431.3
XS GIS Cut Line= 5
     1577433.221      352415.083     1577744.194      352608.916
     1577929.388      352648.584     1578430.773      353201.806
     1578608.547      353468.467
#Sta/Elev= 30
       0  797.63   106.1  790.32     135   790.6   192.9  793.55   260.4  792.78
   308.6  788.84   366.4  780.76   451.7  760.26   480.1   751.4     518   735.9
   555.8  714.97   575.5  705.91   595.1  698.23   614.8   693.3   830.9  691.78
   958.6  687.09  1007.7  678.78  1017.6   678.2    1106  678.16  1125.6  676.92
  1145.3  672.95  1233.7   672.1  1253.3  672.47  1263.2  675.13  1321.9  711.86
  1331.6  716.45  1341.3  719.04  1448.1  737.14  1525.8  744.32  1622.9  755.79
#Mann= 3 , 0 , 0
       0     .08       0  1125.6    .045       0  1263.2      .1       0
Bank Sta=1125.6,1263.2
XS Rating Curve= 0 ,0
Exp/Cntr=0.3,0.1