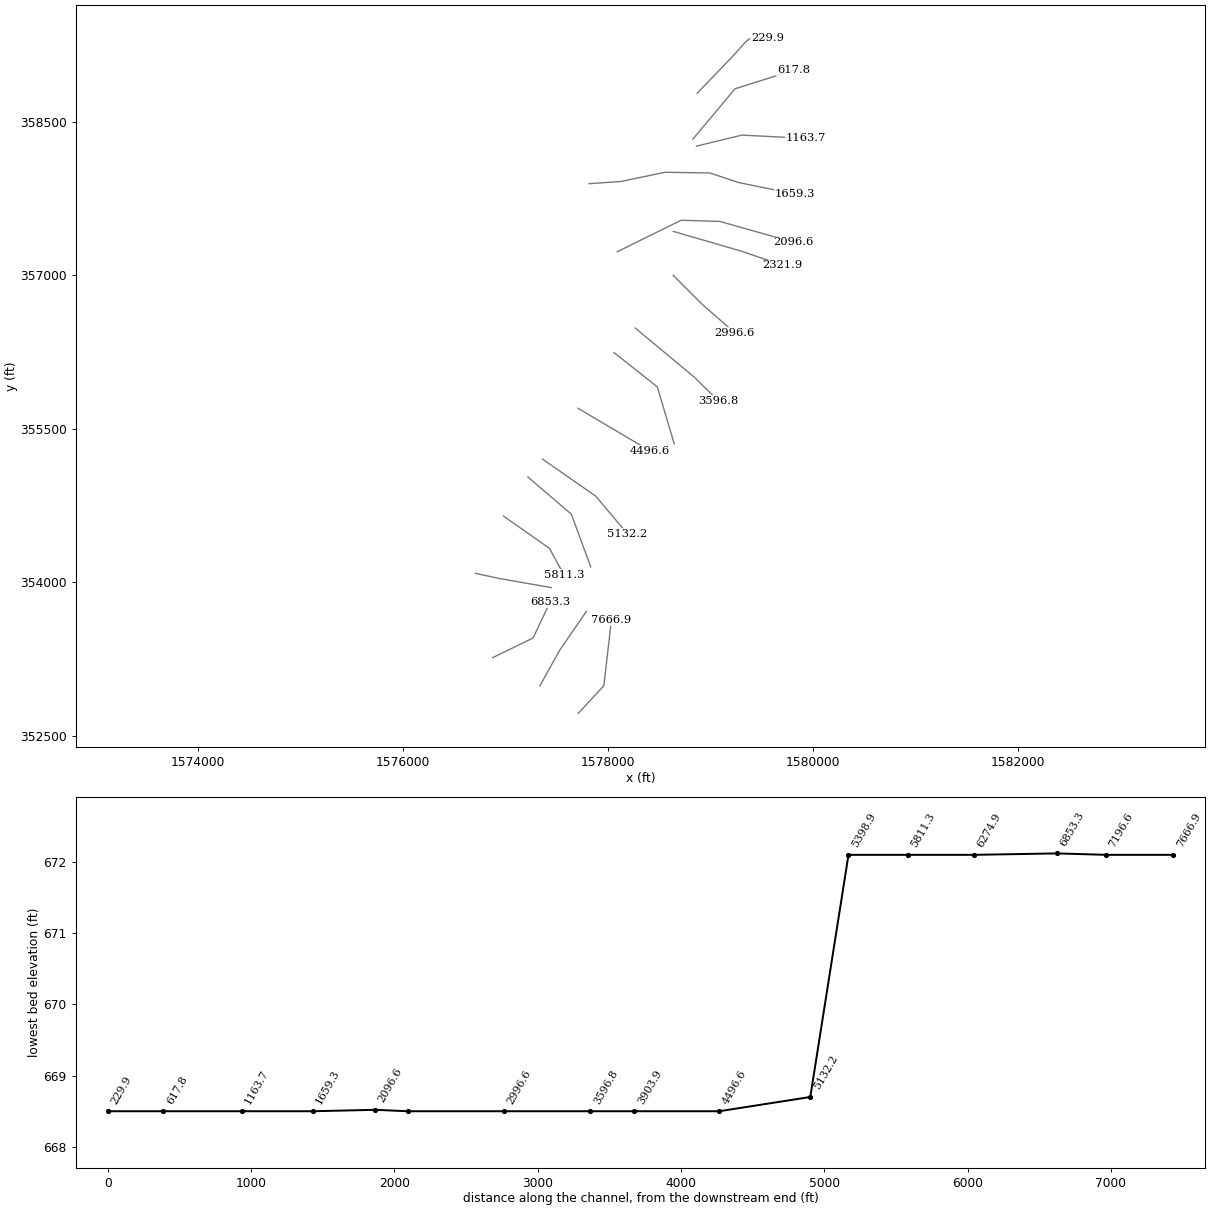
HEC-RAS study MDISLCRK_C.prj: MDISLCRK_C

--- MDISLCRK_C.g01 (geometry) --- (continued)

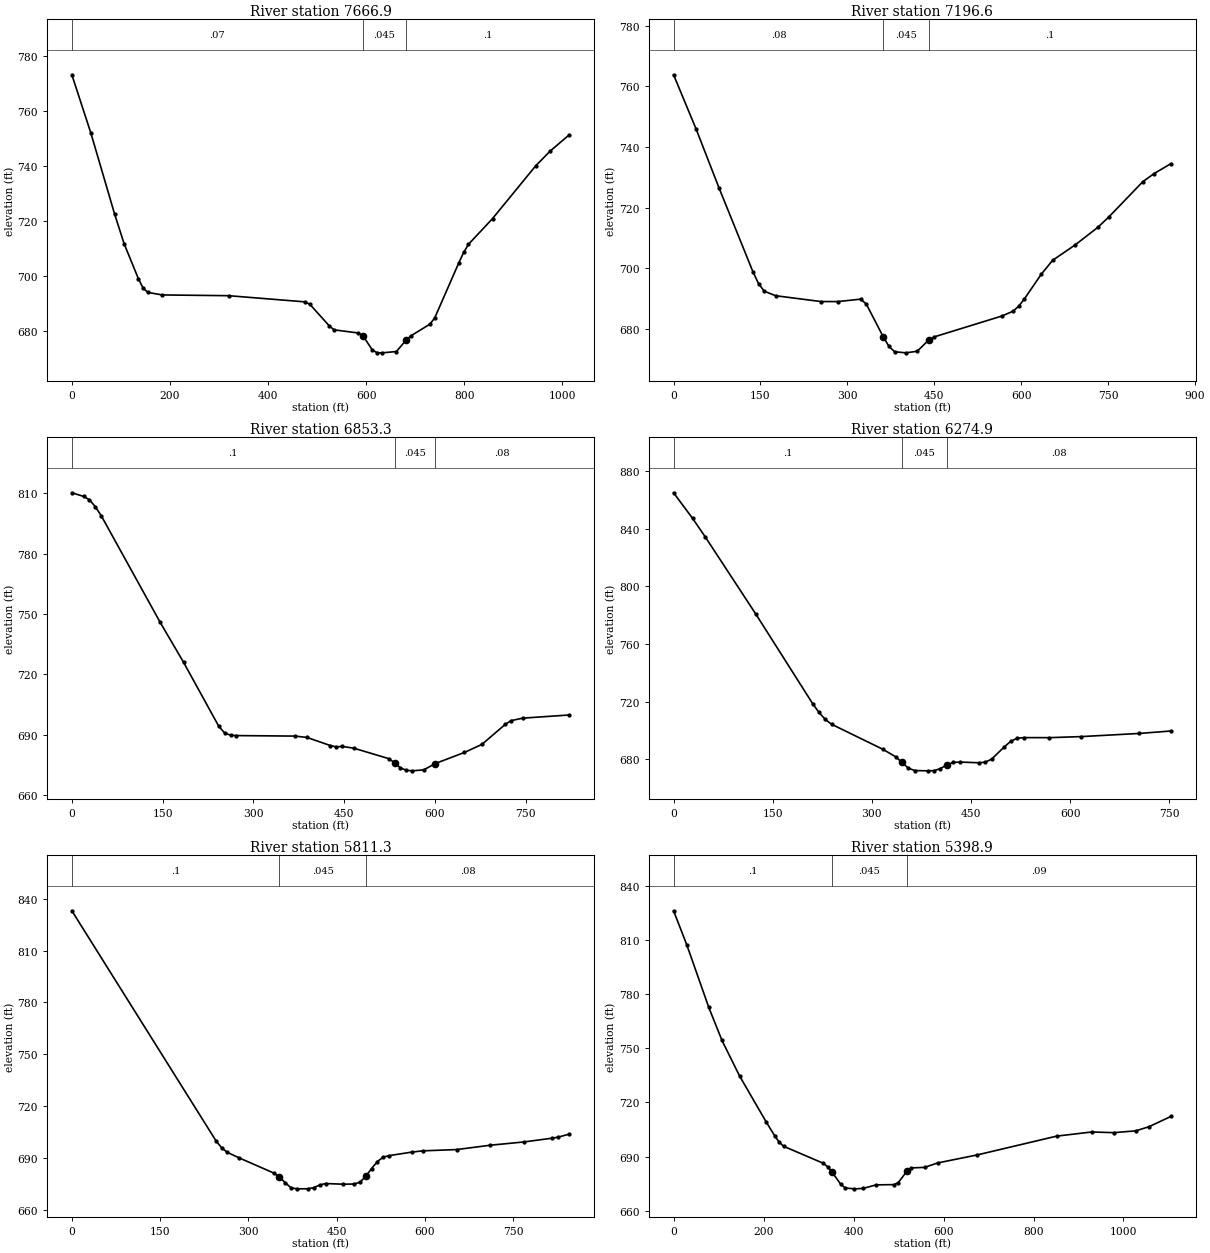
Type RM Length L Ch R = 1 ,7666.9  ,479.1,470.3,459.3
XS GIS Cut Line= 3
     1577707.989      352717.621     1577957.332      352988.164
     1578031.326      353630.117
#Sta/Elev= 30
       0   773.1    38.7  751.96    87.1  722.54   106.5  711.76   135.6  699.03
   145.2  695.62   154.9  694.06     184  693.13   319.5  692.86   475.6  690.61
   485.4  689.68   524.6  681.93   534.4  680.46   583.3  679.32  593.11678.3774
   612.7  673.09   622.5  672.12   632.3   672.1   661.6  672.58  681.23676.6848
     691  678.25   730.2  682.55     740  684.91   788.9  704.83   798.7  708.58
   808.5  711.52   857.5  720.85   945.6  740.04     975  745.38  1014.1  751.31
#Mann= 3 , 0 , 0
       0     .07       0  593.11    .045       0  681.23      .1       0
Bank Sta=593.11,681.23
XS Rating Curve= 0 ,0
Exp/Cntr=0.3,0.1

Type RM Length L Ch R = 1 ,7196.6  ,341.1,343.3,347.7
XS GIS Cut Line= 3
     1577333.103      352985.949     1577527.864      353336.521
     1577786.985      353713.491
#Sta/Elev= 30
       0  763.82    39.1  745.82    78.2  726.61   136.9  698.87   146.7   694.9
   156.5  692.44   176.1  690.94   254.3  689.02   283.7  689.01   322.8  689.81
   332.6  688.19  361.91677.3568   371.7  674.23   381.5  672.46     401   672.1
   420.5  672.63  439.97 676.274   449.7  677.36   566.5  684.24     586  685.84
   595.7  687.52   605.4  689.89   634.6  698.05   654.1  702.61     693   707.7
     732  713.47   751.4  716.97   809.8  728.56   829.3  731.24   858.5  734.54
#Mann= 3 , 0 , 0
       0     .08       0  361.91    .045       0  439.97      .1       0
Bank Sta=361.91,439.97
XS Rating Curve= 0 ,0
Exp/Cntr=0.3,0.1

Type RM Length L Ch R = 1 ,6853.3  ,608.5,578.4,548.4
XS GIS Cut Line= 3
     1576874.655       353262.76     1577267.384      353454.695
     1577431.947       353802.69
#Sta/Elev= 30
       0  810.18    19.4  808.38    29.1   806.7    38.9  803.22    48.6  798.77
   145.7  745.98   184.6     726   242.8  694.24   252.6  690.88   262.3  689.81
     272  689.63   369.1  689.37   388.6  688.69   427.4  684.66   437.1  684.01
   446.7  684.25     466  683.36   523.7  678.18  533.36676.1086     543  673.58
   552.6  672.41   562.2  672.12   581.5  672.59  600.72675.7625   648.8  681.26
   677.7  685.26   716.2  695.19   725.8  697.04   745.1  698.28   822.1  699.86
#Mann= 3 , 0 , 0
       0      .1       0  533.36    .045       0  600.72     .08       0
Bank Sta=533.36,600.72
XS Rating Curve= 0 ,0
Exp/Cntr=0.3,0.1

Type RM Length L Ch R = 1 ,6274.9  ,473.5,463.6,453.6
XS GIS Cut Line= 3
     1576706.252      354085.676     1576949.308      354033.593
     1577445.836      353946.788
#Sta/Elev= 30
       0  864.92    28.7   847.2    47.8  834.41   124.3  780.89   210.3  718.78
   219.9  712.64   229.4   707.8     239  704.41   316.4  687.09   335.8  681.92
  345.51677.9559   355.2  673.92   364.9   672.3   384.3   672.1     394  672.23
   403.7  673.68  413.36676.2991   423.1   677.9   432.8  678.19   461.8   677.7
   471.5  678.11   481.2  680.24   500.6  688.82   510.3   692.7     520  694.69
   529.7  695.15   568.5  695.11   616.9  695.85   704.2  698.02   752.6  699.74
#Mann= 3 , 0 , 0
       0      .1       0  345.51    .045       0  413.36     .08       0
Bank Sta=345.51,413.36
XS Rating Curve= 0 ,0
Exp/Cntr=0.3,0.1

Type RM Length L Ch R = 1 ,5811.3  ,414.6,412.4,410.2
XS GIS Cut Line= 3
      1576977.95      354645.801     1577426.739      354330.468
       1577569.1      354070.051
#Sta/Elev= 30
       0  833.09   244.9  699.91   254.7  695.76   264.4  693.19     284  690.06
   342.8  681.29   352.6  679.04   362.4  675.68   372.2  672.76     382   672.1
   401.6  672.15   411.4  672.87   421.2   674.3     431  675.18   460.3  674.79
   479.9  674.89   489.7  675.97  499.52679.3991   509.3  683.84   519.1  687.89
   528.9  690.41   538.7  691.31   577.2  693.35   596.4   694.1   653.8  694.84
   711.2  697.36   768.7  699.27   816.6  701.45   826.1  702.02   845.3  703.78
#Mann= 3 , 0 , 0
       0      .1       0   352.6    .045       0  499.52     .08       0
Bank Sta=352.6,499.52
XS Rating Curve= 0 ,0
Exp/Cntr=0.3,0.1

Type RM Length L Ch R = 1 ,5398.9  ,264.5,266.7,269
XS GIS Cut Line= 3
     1577217.032       355027.18     1577640.592       354664.26
     1577829.516      354149.912
#Sta/Elev= 30
       0  826.33    29.4  807.42    78.3  772.71   107.6   754.4   146.8  734.66
   205.5  709.35   225.1  701.36   234.8  697.98   244.6   695.7   332.7  686.29
   342.5  684.34  352.28681.3661   371.8  674.52   381.6   672.6   401.2   672.1
   420.8   672.3   450.1   674.3   489.3  674.44   499.1  675.43  518.63681.8956
   528.4  683.71   557.8     684   587.1  686.47   675.2  690.93   851.3  701.33
   929.6  703.64   978.5  703.26  1027.4  704.27  1056.8  706.58  1105.7  712.29
#Mann= 3 , 0 , 0
       0      .1       0  352.28    .045       0  518.63     .09       0
Bank Sta=352.28,518.63
XS Rating Curve= 0 ,0
Exp/Cntr=0.3,0.1

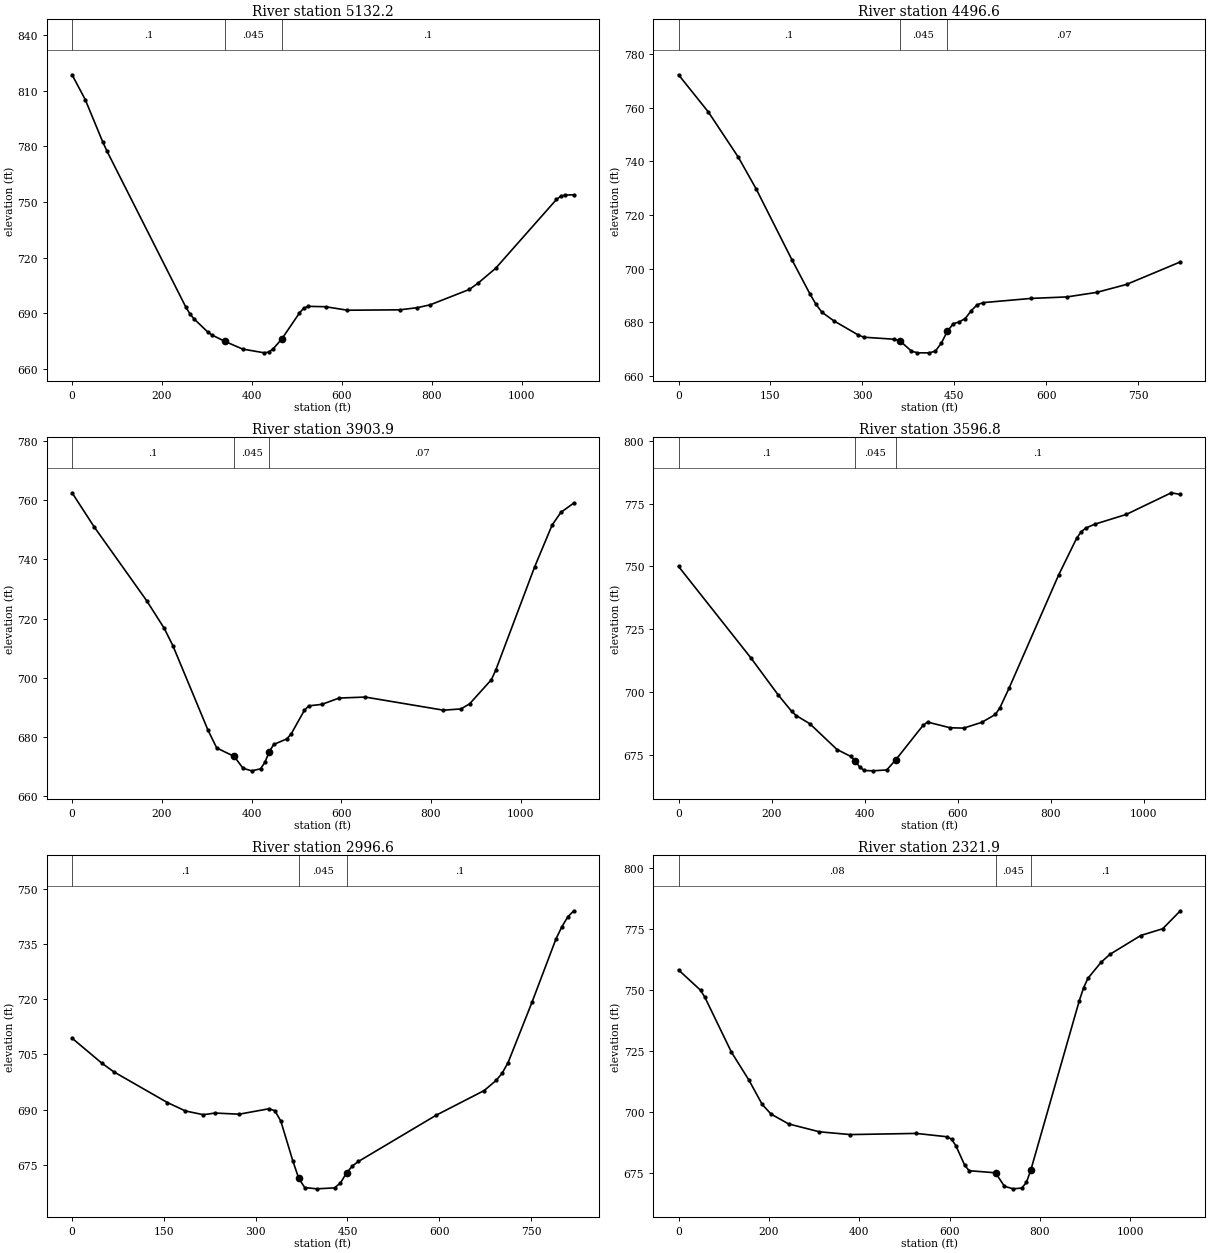
Type RM Length L Ch R = 1 ,5132.2  ,633.9,635.6,637.2
XS GIS Cut Line= 3
     1577359.014      355202.664     1577877.488      354841.479
     1578188.892      354471.093
#Sta/Elev= 30
       0  818.63    29.2   805.3      68  782.54    77.8  777.37   252.8  693.45
   262.5  689.55   272.2  686.78   301.4  680.01   311.1   678.3  340.24674.8356
   379.1  670.74   427.7   668.7   437.4  669.14   447.2  670.86  466.62676.2669
   505.5  690.15   515.2   692.8     525  693.77   563.8  693.56   612.4  691.68
   728.7  691.89   767.4  693.04   796.4   694.6   883.5  702.89   902.9   706.3
   941.6  714.22  1077.1   751.4  1086.7  753.13  1096.4  753.78  1115.8  753.91
#Mann= 3 , 0 , 0
       0      .1       0  340.24    .045       0  466.62      .1       0
Bank Sta=340.24,466.62
XS Rating Curve= 0 ,0
Exp/Cntr=0.3,0.1

Type RM Length L Ch R = 1 ,4496.6  ,595.7,592.7,589.6
XS GIS Cut Line= 3
     1577704.601      355699.813      1578056.84      355490.963
     1578409.079      355282.114
#Sta/Elev= 30
       0  772.39    48.8  758.45    97.5  741.62   126.8   729.7   185.2  703.21
   214.5   690.5   224.2  686.68     234  683.68   253.5  680.46   292.5  675.28
   302.2  674.34     351   673.6  360.75673.1025   380.2  669.14     390   668.5
   409.5   668.5   419.2  669.14     429  672.16   438.8   676.6   448.5  679.38
   458.2  680.07     468  681.33   477.8  684.26   487.5  686.47   497.2  687.26
   575.2  688.83   633.8  689.39   682.5  691.09   731.2  694.06     819  702.47
#Mann= 3 , 0 , 0
       0      .1       0  360.75    .045       0   438.8     .07       0
Bank Sta=360.75,438.8
XS Rating Curve= 0 ,0
Exp/Cntr=0.3,0.1

Type RM Length L Ch R = 1 ,3903.9  ,307.6,307.1,306.6
XS GIS Cut Line= 3
     1578057.876      356242.552     1578478.822      355908.593
     1578643.752      355351.301
#Sta/Elev= 30
       0  762.54    48.8  751.11   166.1  726.08   205.2  716.76   224.7  710.83
   302.9  682.29   322.4  676.24  361.48673.3716     381  669.36   400.6   668.5
   420.1  669.18   429.9   671.4  439.63674.9675   449.4  677.41   478.7  679.31
   488.5  681.01   517.8  688.96   527.6  690.48   556.7  690.98   595.4  693.12
   653.6  693.45   827.9  689.01   866.7  689.44     886  691.14   934.5  699.29
   944.2  702.48  1031.3  737.56  1070.1  751.65  1089.5   755.9  1118.5  759.08
#Mann= 3 , 0 , 0
       0      .1       0  361.48    .045       0  439.63     .07       0
Bank Sta=361.48,439.63
XS Rating Curve= 0 ,0
Exp/Cntr=0.3,0.1

Type RM Length L Ch R = 1 ,3596.8  ,602.3,600.2,599.6
XS GIS Cut Line= 3
     1578263.913      356482.864       1578840.1      356003.238
     1579074.308       355771.44
#Sta/Elev= 30
       0  750.02   155.8  713.49   214.2  698.81   243.4  692.21   253.1  690.54
   282.4  687.28   340.8  677.01     370  674.29  379.71672.5175   389.4  670.06
   399.2  668.65   417.2   668.5   447.9  668.86  467.34672.9292   525.8  686.62
   535.5  687.95   584.2  685.68   613.4  685.54   652.3  687.86   681.5  690.99
   691.3   693.7   710.7   701.4   817.5  746.62   856.3  761.29     866  763.84
   875.7   765.3   895.1  766.86   962.9  770.76  1059.8   779.4  1079.2  778.72
#Mann= 3 , 0 , 0
       0      .1       0  379.71    .045       0  467.34      .1       0
Bank Sta=379.71,467.34
XS Rating Curve= 0 ,0
Exp/Cntr=0.3,0.1

Type RM Length L Ch R = 1 ,2996.6  ,664.4,674.7,683.5
XS GIS Cut Line= 3
     1578633.372      356999.046     1578922.797      356709.621
     1579231.634      356439.068
#Sta/Elev= 30
       0  709.39    48.7   702.6    68.2  700.26   155.9  691.91   185.2  689.64
   214.4  688.62   233.9  689.07   272.9  688.76   321.6  690.23   331.4   689.7
   341.1  686.88   360.6  676.15  370.33671.3523   380.1  668.86   399.6   668.5
   428.9  668.76   438.6  670.11  448.41 672.802   458.2  674.74     468  675.94
     595  688.49   673.3  695.17   692.8  697.91   702.6  699.85   712.4  702.76
   751.5  719.15   790.6   736.3   800.3  739.63   810.1  742.35   819.9  743.97
#Mann= 3 , 0 , 0
       0      .1       0  370.33    .045       0  448.41      .1       0
Bank Sta=370.33,448.41
XS Rating Curve= 0 ,0
Exp/Cntr=0.3,0.1

Type RM Length L Ch R = 1 ,2321.9  ,224,225.3,226.6
XS GIS Cut Line= 3
     1578633.766      357428.254     1579307.347      357231.994
     1579693.873      357098.197
#Sta/Elev= 30
       0  758.28    48.7  749.97    58.5     747   116.9  724.62   155.9  713.06
   185.1  703.15   204.6  699.18   243.6  695.13   311.8  691.89     380  690.76
   526.2  691.23   594.4  689.86   604.2  688.86   613.9  686.17   633.4  678.17
   643.1  675.94   701.6  675.08   721.1  669.58   740.6   668.5     760  668.84
   769.8  671.13   779.5  676.08   886.6  745.42   896.4  750.94   906.1  754.86
   935.3  761.44   954.8  764.68    1023  772.41  1071.7  775.19  1110.6  782.55
#Mann= 3 , 0 , 0
       0     .08       0   701.6    .045       0   779.5      .1       0
Bank Sta=701.6,779.5
XS Rating Curve= 0 ,0
Exp/Cntr=0.3,0.1

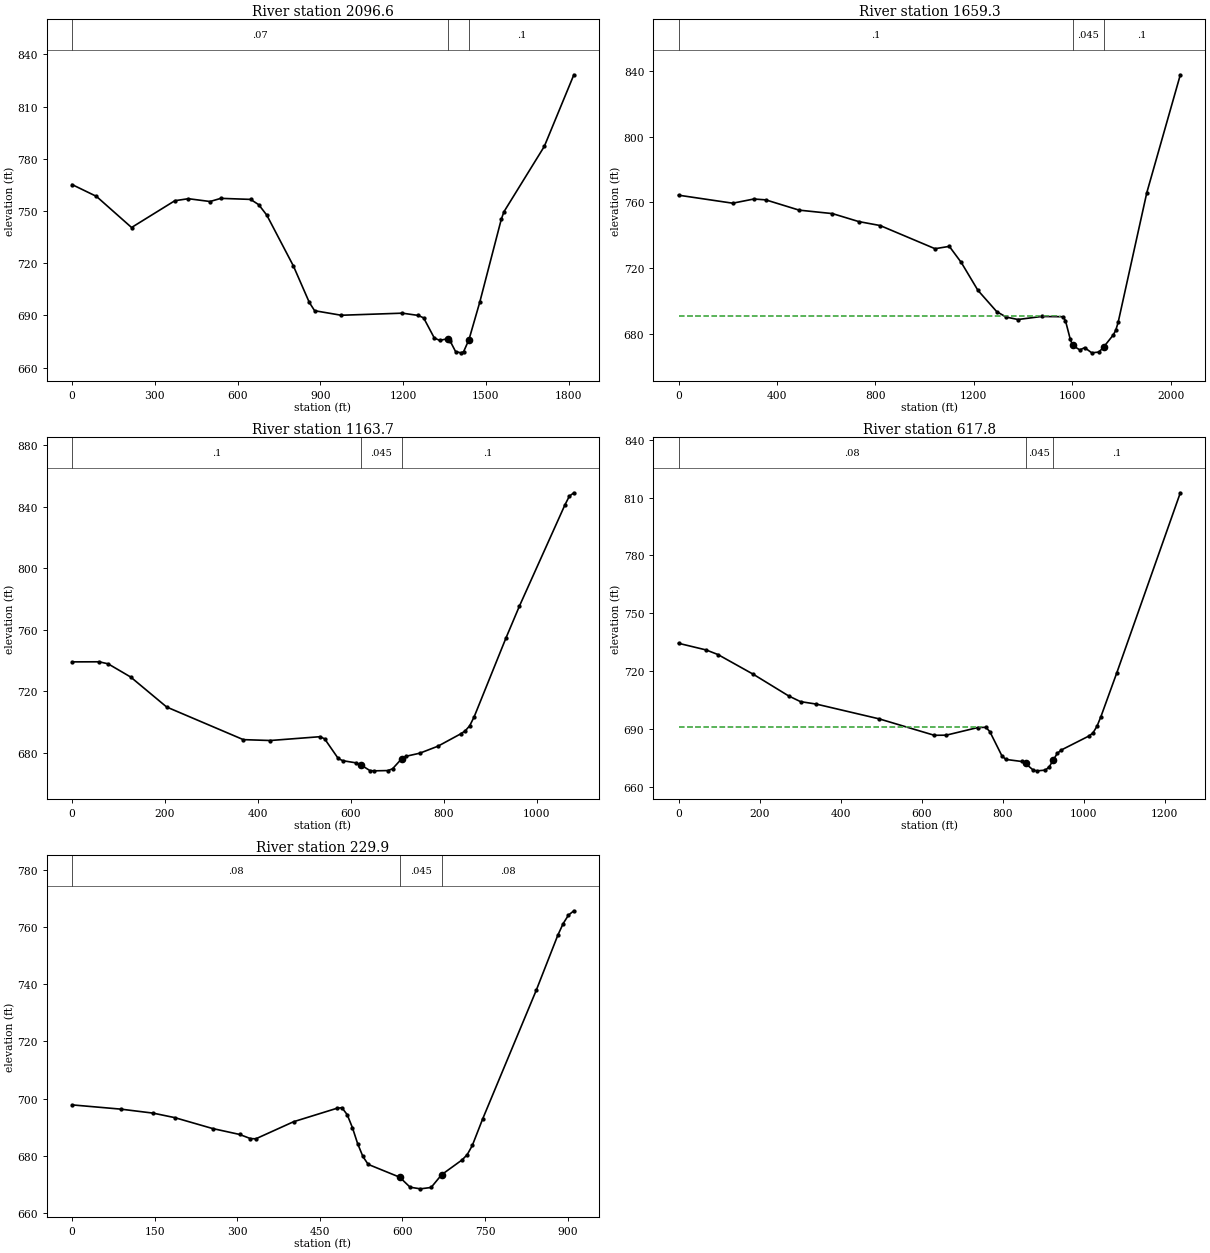
Type RM Length L Ch R = 1 ,2096.6  ,435.6,437.3,438.9
XS GIS Cut Line= 5
     1578087.412       357228.96      1578711.86      357536.765
     1579087.448      357525.485     1579412.212      357433.758
     1579806.295      357322.452
#Sta/Elev= 30
       0  765.23    88.2  758.45   215.7  740.55   372.6  755.95   421.6   757.1
   500.1  755.49   539.3   757.3   647.2   756.7   676.6  753.66   705.8  747.67
   802.2  718.47     860  697.47   879.2  692.73   975.6  690.12  1197.3  691.32
  1255.1  690.01  1274.4   688.6    1313  677.06  1332.3   675.7  1361.2   676.6
  1370.8  675.19  1390.1  669.25  1409.4  668.52  1419.2  669.16  1438.7  676.14
  1477.7  697.57  1555.7   745.2  1565.4  749.58  1711.7  787.14  1818.9  828.32
#Mann= 3 , 0 , 0
       0     .07       0  1361.2    .045       0  1438.7      .1       0
#XS Ineff= 2 , 0
         1198.69  691.17
Permanent Ineff=
       F       F
Bank Sta=1361.2,1438.7
XS Rating Curve= 0 ,0
Exp/Cntr=0.3,0.1

Type RM Length L Ch R = 1 ,1659.3  ,492.2,495.6,499
XS GIS Cut Line= 6
     1577813.107      357893.891      1578118.61      357914.975
     1578554.432      358005.427     1578990.768      357999.197
     1579272.599      357905.121     1579815.627       357794.01
#Sta/Elev= 30
       0  764.33   220.1  759.46   306.2  762.01   354.6  761.48   490.1  755.24
   625.6  753.13     732   748.3   819.2  745.88  1042.3   731.8  1100.4  733.22
  1148.9  723.43  1216.5  706.51  1293.2  693.52  1331.5  690.24  1379.4  688.76
  1475.2   690.6  1562.6  690.46  1572.4  688.01  1591.8  676.79  1601.5     673
  1630.7  670.28  1650.2  671.66  1679.3   668.5  1708.5  668.99  1727.9  672.11
  1766.8  679.42  1776.6  682.19  1786.3  686.95    1903  765.93  2039.1  837.52
#Mann= 3 , 0 , 0
       0      .1       0  1601.5    .045       0  1727.9      .1       0
#XS Ineff= 2 , 0
         1551.53  690.73
Permanent Ineff=
       F       F
Bank Sta=1601.5,1727.9
XS Rating Curve= 0 ,0
Exp/Cntr=0.3,0.1

Type RM Length L Ch R = 1 ,1163.7  ,537.9,546,554
XS GIS Cut Line= 3
     1578860.766      358261.024     1579303.475      358368.663
     1579926.739      358337.413
#Sta/Elev= 30
       0   739.2    58.2  739.26    77.6  737.93     126  729.39   203.6   709.9
   368.4  688.75   426.5  688.18   533.6  690.66   543.4  689.27   572.6  676.53
   582.4  675.08   611.6  673.65  621.37672.3539   640.9  668.64   650.6   668.5
   679.9  668.69   689.6  669.86  709.12676.3434   718.9  677.98   748.1  679.95
   787.1  684.48   835.9  692.46   845.6  694.38   855.4  697.69   865.1  703.56
   933.4  754.61   962.6  775.49  1060.2  840.95  1069.9  846.73  1079.6  848.93
#Mann= 3 , 0 , 0
       0      .1       0  621.37    .045       0  709.12      .1       0
#XS Ineff= 2 , 0
          532.87  690.52
Permanent Ineff=
       F       F
Bank Sta=621.37,709.12
XS Rating Curve= 0 ,0
Exp/Cntr=0.3,0.1

Type RM Length L Ch R = 1 ,617.8   ,375.8,387.9,399.9
XS GIS Cut Line= 3
     1578825.234      358329.426     1579236.345      358821.093
      1579805.79      359001.649
#Sta/Elev= 30
       0  734.53      68  731.09    97.1  728.72   184.5  718.49   271.9  707.26
     301  704.33   339.9  703.06   495.2   695.4   631.2   686.9   660.5  686.96
   738.8  690.93   758.4  691.03   768.2   688.8   797.6  676.44   807.4  674.42
   846.6  673.35  856.35672.3253   875.9  668.75   885.7   668.5   905.3  668.88
   915.1  670.63   924.9  674.22   934.7  677.53   944.5  679.28    1013  686.56
  1022.8  688.15  1032.6  691.56  1042.4   696.6  1081.6  719.29  1238.3  812.45
#Mann= 3 , 0 , 0
       0     .08       0  856.35    .045       0   924.9      .1       0
#XS Ineff= 2 , 0
          748.21  691.12
Permanent Ineff=
       F       F
Bank Sta=856.35,924.9
XS Rating Curve= 0 ,0
Exp/Cntr=0.3,0.1

Type RM Length L Ch R = 1 ,229.9   ,231.2,229.9,228.7
XS GIS Cut Line= 5
     1578867.967      358778.603     1579194.467      359118.014
     1579335.043      359273.591     1579376.458      359310.303
     1579551.581      359314.523
#Sta/Elev= 30
       0  697.84    88.3  696.36   147.2  694.96   186.4  693.39   255.1  689.58
   304.2  687.51   323.8  686.07   333.6  685.98   402.3  691.96   480.5  696.63
     490  696.87   499.6  694.42   509.1  689.88   518.6  684.28   528.1  679.81
   537.7  677.05  594.86672.5736   613.9  669.06   632.6   668.5     652  668.98
  671.11673.4417   708.3  678.62   717.5  680.43   726.8  683.66   745.7  692.98
     843  737.94     882  757.11   891.7  761.18   901.4  764.16   911.2  765.68
#Mann= 3 , 0 , 0
       0     .08       0  594.86    .045       0  671.11     .08       0
Bank Sta=594.86,671.11
XS Rating Curve= 0 ,0
Exp/Cntr=0,0

Chan Stop Cuts=-1
Use User Specified Reach Order=0
Composite Channel Slope=5